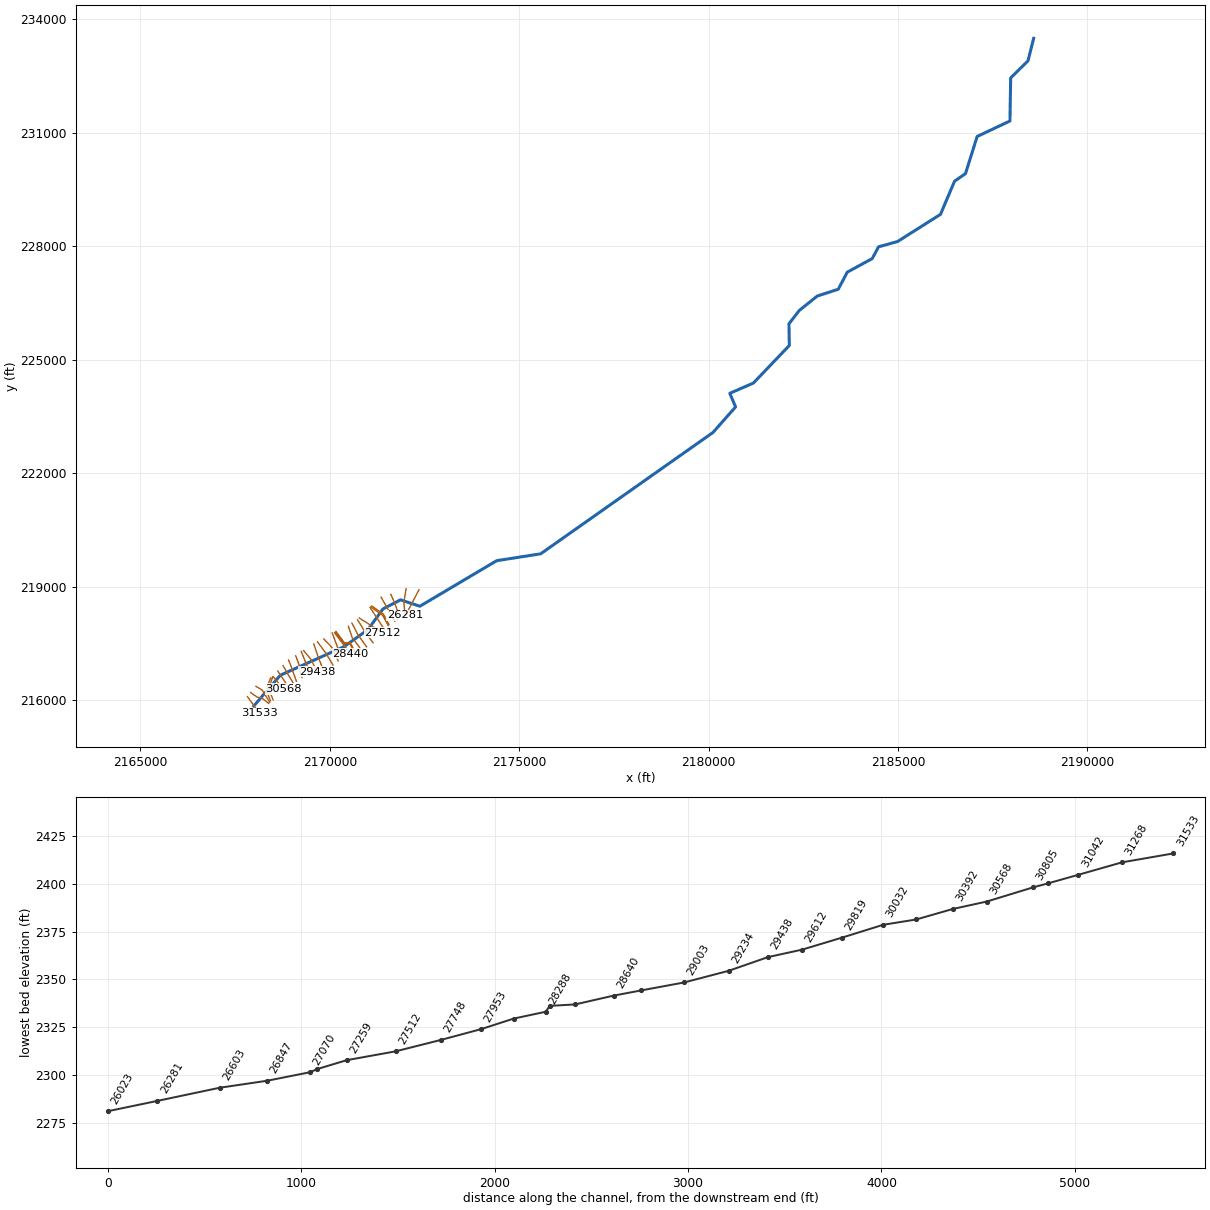
--- SWTSPRNGSCK.prj (project) ---

Proj Title=SWTSPRNGSCK
Current Plan=p01
Default Exp/Contr=0,0
English Units
Geom File=g01
Flow File=f01
Plan File=p01
Background Map Layer=Inundation Boundary (01pct Value_0)
Y Axis Title=Elevation
X Axis Title(PF)=Main Channel Distance
X Axis Title(XS)=Station
BEGIN DESCRIPTION:
Stream Name: Sweet Spring Creek
Flood Zone:Approximate
Monroe County, West Virginia
HEC-RAS Version: 5.0.7
Vertical Datum: NAVD88
Projection: NAD 1983 StatePlane West Virginia S FIPS 4702 (US Feet)
LiDAR: 2016, 1-meter
Land Use: 2016 NLCD
Hydrologic Method:
Regression
Model Notes:
Model extends beyond county boundary into Allegany county.
END DESCRIPTION:
DSS Export Rating Curves= 0
DSS Export Rating Curve Sorted= 0
DSS Export Volume Flow Curves= 0
DXF OffsetX= 0
DXF OffsetY= 0
DXF ScaleX= 0
DXF ScaleY= 0

--- SWTSPRNGSCK.p01 (plan) ---

Plan Title=Floodplain
Program Version=5.07
Short Identifier=Floodplain
Geom File=g01
Flow File=f01
Subcritical Flow
K Sum by GR= 0
Std Step Tol= 0.01
Critical Tol= 0.01
Num of Std Step Trials= 20
Max Error Tol= 0.3
Flow Tol Ratio= 0.001
Split Flow NTrial= 30
Split Flow Tol= 0.02
Split Flow Ratio= 0.02
Log Output Level= 0
Friction Slope Method= 1
Unsteady Friction Slope Method= 2
Unsteady Bridges Friction Slope Method= 1
Parabolic Critical Depth
Global Vel Dist= 0 , 0 , 0
Global Log Level= 0
CheckData=True
Encroach Param=-1 ,0,0, 0
Mapping Interval=1HOUR
Computation Time Step Use Courant=        0
Computation Time Step Use Time Series=    0
Computation Time Step Count To Double=0
Computation Time Step Max Doubling=0
Computation Time Step Max Halving=0
Computation Time Step Residence Courant=0
Run HTab= 0
Run UNet= 0
Run Sediment= 0
Run PostProcess= 0
Run WQNet= 0
Run RASMapper= 0
UNET Theta= 0
UNET Theta Warmup= 0
UNET ZTol= 0
UNET ZSATol= 0
UNET MxIter= 0
UNET Max Iter WO Improvement= 0
UNET MaxInSteps= 0
UNET DtIC= 0
UNET DtMin= 0
UNET MaxCRTS= 0
UNET WFStab= 0
UNET SFStab= 0
UNET WFX= 1
UNET SFX= 1
UNET 1D Methodology=Finite Difference
UNET DSS MLevel= 1
UNET Pardiso=0
UNET DZMax Abort= 0
UNET Use Existing IB Tables= 0
UNET Froude Reduction=False
UNET Froude Limit= 0
UNET Froude Power= 0
UNET D1 Cores= 0
UNET D2 Coriolis=0
UNET D2 Cores= 0
UNET D2 Theta= 1
UNET D2 Theta Warmup= 1
UNET D2 Z Tol= 0.01
UNET D2 Volume Tol= 0.01
UNET D2 Max Iterations= 20
UNET D2 Equation= 0
UNET D2 RampUpFraction=0.1
UNET D2 TimeSlices= 1
UNET D2 BCVolumeCheck=0
UNET D1D2 MaxIter= 0
UNET D1D2 ZTol=0.01
UNET D1D2 QTol=0.1
UNET D1D2 MinQTol=1
Write IC File= 0
Write IC File at Fixed DateTime=0
Write IC File at Sim End=0
Echo Input=False
Echo Parameters=False
Echo Output=False
Write Detailed= 0
HDF Write Warmup=0
HDF Write Time Slices=0
HDF Flush=0
HDF Face Node Velocities=0
HDF Compression= 1
HDF Chunk Size= 1
HDF Spatial Parts= 1
HDF Use Max Rows=0
HDF Fixed Rows= 1
Calibration Method= 0
Calibration Iterations= 20
Calibration Max Change=0.05
Calibration Tolerance=0.2
Calibration Maximum=1.5
Calibration Minimum=0.5
Calibration Optimization Method= 1
WQ AD Non Conservative
WQ ULTIMATE=-1
WQ Max Comp Step=1HOUR
WQ Output Interval=15MIN
WQ Output Selected Increments= 0
WQ Output face flow=0
WQ Output face velocity=0
WQ Output face area=0
WQ Output face dispersion=0
WQ Output cell volume=0
WQ Output cell surface area=0
WQ Output cell continuity=0
WQ Output cumulative cell continuity=0
WQ Output face conc=0
WQ Output face dconc_dx=0
WQ Output face courant=0
WQ Output face peclet=0
WQ Output face adv mass=0
WQ Output face disp mass=0
WQ Output cell mass=0
WQ Output cell source sink temp=0
WQ Output nsm pathways=0
WQ Output nsm derived pathways=0
WQ Output MaxMinRange=-1
WQ Daily Max Min Mean=-1
WQ Daily Range=0
WQ Daily Time=0
WQ Create Restart=0
WQ Fixed Restart=0
WQ System Summary=0
WQ Write To DSS=0
WQ Use Fixed Temperature=0
Sorting and Armoring Iterations= 10
XS Update Threshold= 0.02
Bed Roughness Predictor= 0
Hydraulics Update Threshold= 0.02
Energy Slope Method= 1
Volume Change Method= 1
Sediment Retention Method= 0
XS Weighting Method= 0
Number of US Weighted Cross Sections= 1
Number of DS Weighted Cross Sections= 1
Upstream XS Weight=0
Main XS Weight=1
Downstream XS Weight=0
Number of DS XS's Weighted with US Boundary= 1
Upstream Boundary Weight= 1
Weight of XSs Associated with US Boundary= 0
Number of US XS's Weighted with DS Boundary= 1
Downstream Boundary Weight= 0.5
Weight of XSs Associated with DS Boundary= 0.5
Percentile Method= 0
Sediment Output Level= 3
Mass or Volume Output= 0
Output Increment Type= 1
Profile and TS Output Increment= 1
XS Output Flag= 0
XS Output Increment= 10
Write Gradation File= 0
Read Gradation Hotstart= 0
Write HDF5 File= 1
Write Binary Output= 1
Write DSS Sediment File= 0
SV Curve= 0
Specific Gage Flag= 0

--- SWTSPRNGSCK.f01 (steady flow) ---

Flow Title=Flow
Program Version=5.07
Number of Profiles= 6
Profile Names=01pct,10pct,04pct,02pct,0_2pct,01plus
River Rch & RM=SWTSPRNGSCK,Main            ,31533
     528     278     370     447     739     781
River Rch & RM=SWTSPRNGSCK,Main            ,30883
     583     308     410     494     814     863
River Rch & RM=SWTSPRNGSCK,Main            ,30204
     609     322     428     515     849     900
River Rch & RM=SWTSPRNGSCK,Main            ,29003
     665     353     468     563     926     983
River Rch & RM=SWTSPRNGSCK,Main            ,26603
     767     410     542     651    1070    1130
River Rch & RM=SWTSPRNGSCK,Main            ,26281
     779     417     551     661    1080    1150
River Rch & RM=SWTSPRNGSCK,Main            ,26023
     870     467     616     739    1210    1290
River Rch & RM=SWTSPRNGSCK,Main            ,25427
     902     485     640     766    1250    1330
River Rch & RM=SWTSPRNGSCK,Main            ,24252
     995     537     707     846    1380    1470
River Rch & RM=SWTSPRNGSCK,Main            ,23106
    1070     579     762     911    1480    1580
River Rch & RM=SWTSPRNGSCK,Main            ,20783
    1190     646     847    1010    1640    1760
River Rch & RM=SWTSPRNGSCK,Main            ,19004
    1270     690     904    1080    1740    1870
River Rch & RM=SWTSPRNGSCK,Main            ,17526
    1390     759     993    1180    1910    2050
River Rch & RM=SWTSPRNGSCK,Main            ,14764
    1540     845    1100    1310    2110    2280
River Rch & RM=SWTSPRNGSCK,Main            ,12276
    1700     938    1220    1460    2330    2520
River Rch & RM=SWTSPRNGSCK,Main            ,10982
    1880    1040    1350    1610    2570    2780
River Rch & RM=SWTSPRNGSCK,Main            ,5937
    2050    1140    1480    1760    2800    3040
River Rch & RM=SWTSPRNGSCK,Main            ,5344
    2180    1210    1570    1870    2970    3230
River Rch & RM=SWTSPRNGSCK,Main            ,4424
    2320    1300    1680    1990    3160    3430
Boundary for River Rch & Prof#=SWTSPRNGSCK,Main            , 1
Up Type= 0
Dn Type= 3
Dn Slope=0.00267
Boundary for River Rch & Prof#=SWTSPRNGSCK,Main            , 2
Up Type= 0
Dn Type= 3
Dn Slope=0.00267
Boundary for River Rch & Prof#=SWTSPRNGSCK,Main            , 3
Up Type= 0
Dn Type= 3
Dn Slope=0.00267
Boundary for River Rch & Prof#=SWTSPRNGSCK,Main            , 4
Up Type= 0
Dn Type= 3
Dn Slope=0.00267
Boundary for River Rch & Prof#=SWTSPRNGSCK,Main            , 5
Up Type= 0
Dn Type= 3
Dn Slope=0.00267
Boundary for River Rch & Prof#=SWTSPRNGSCK,Main            , 6
Up Type= 0
Dn Type= 3
Dn Slope=0.00267
DSS Import GetInterval= 0
DSS Import GetPeak= 0
DSS Import FillOption= 0

--- SWTSPRNGSCK.g01 (geometry) ---

Geom Title=Geometry
Program Version=5.07

River Reach=SWTSPRNGSCK     ,Main
Reach XY= 30
     2167990.115      215850.588     2168693.457      216665.041
     2170376.617      217419.381     2171005.089      217869.034
     2171402.658      218415.909     2171865.332      218655.493
     2172375.749      218486.222     2174402.659      219689.347
     2175564.985      219871.638     2180113.596      223077.368
     2180709.733      223751.413     2180557.824      224111.656
     2181180.653      224382.923     2182129.004      225375.762
     2182119.238      225947.593     2182390.506      226299.156
     2182866.851      226682.185     2183421.322      226861.222
     2183660.037      227313.696     2184317.589      227670.684
     2184483.605      227981.013     2184987.077      228122.072
     2186119.889      228839.303     2186490.983      229716.039
     2186779.612      229915.692     2187087.771      230896.595
     2187953.657      231306.751     2187972.103      232443.904
     2188429.264      232894.6422188579.34705143233489.839242437

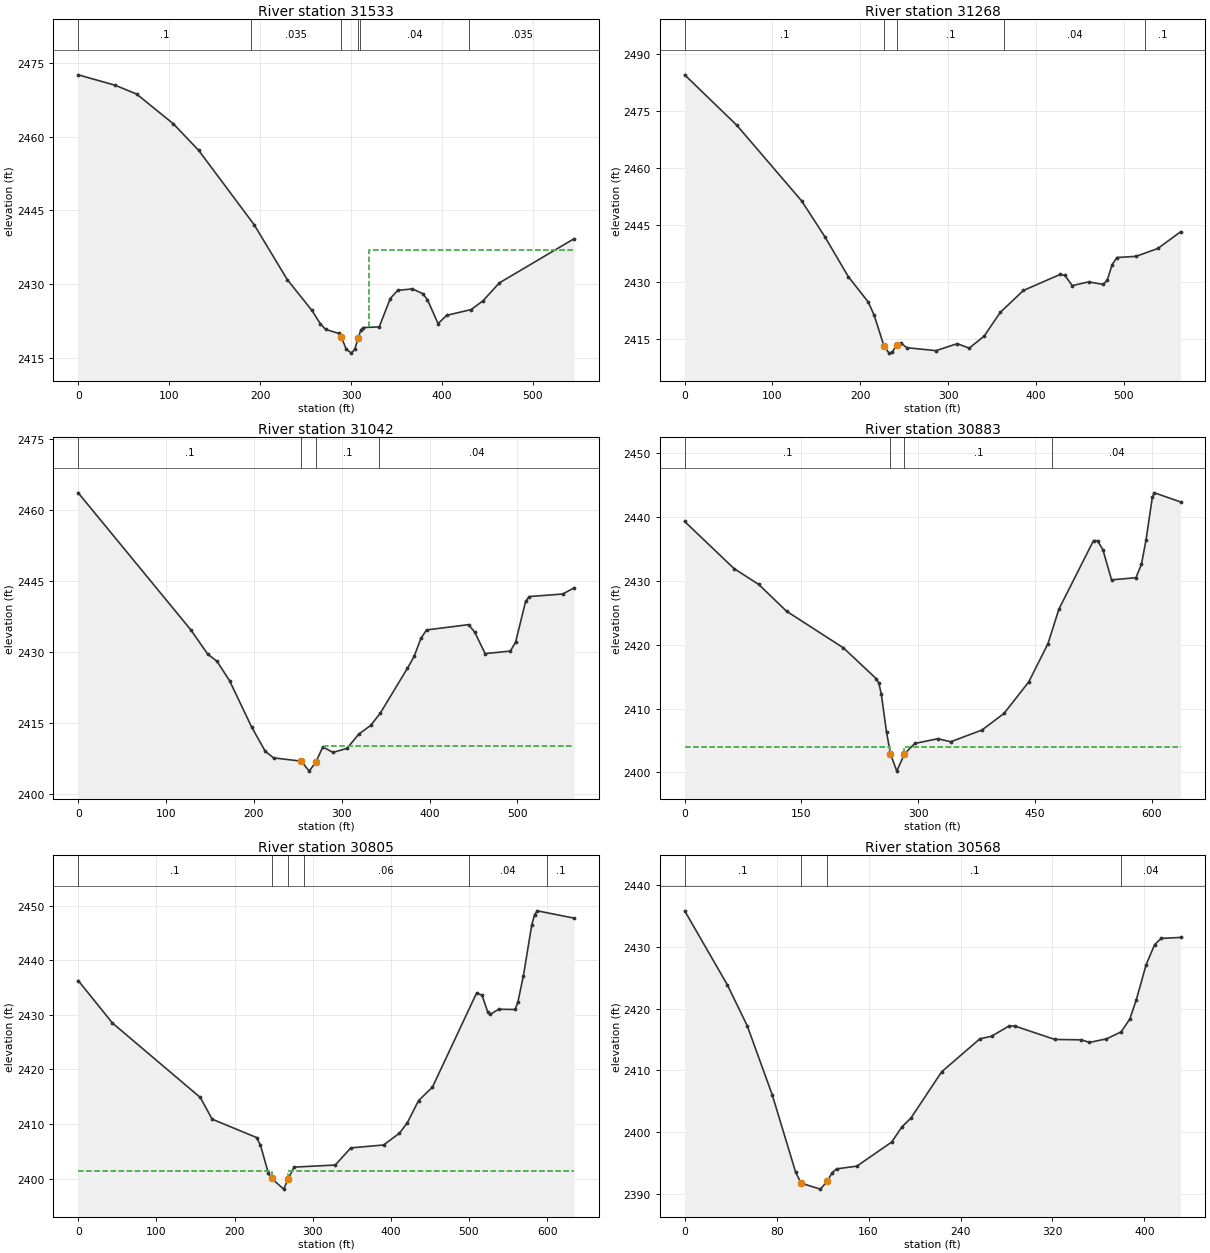
Type RM Length L Ch R = 1 ,31533   ,265.3,265.3,265.3
XS GIS Cut Line= 2
     2167823.058      216098.477     2168141.726      215655.966
#Sta/Elev= 30
       0 2472.63    40.8  2470.5    64.2 2468.71   104.6 2462.65   132.5 2457.23
   193.4  2442.1   229.9  2430.9     257 2424.61   266.4 2421.85   272.2 2420.74
   286.5 2419.94  289.292419.196   294.6 2416.77   300.3 2415.92   304.1 2416.72
  307.982419.102   310.8 2420.65   313.5 2421.13     331 2421.27   343.1 2427.05
   351.2  2428.7   367.4 2429.01   378.9 2428.04     384 2426.81   395.7 2421.93
   405.1 2423.62   432.1  2424.8   445.1 2426.59   463.1 2430.24   545.3 2439.24
#Mann= 6 ,-1 , 0
       0      .1       0     190    .035       0  289.29    .045       0
  307.98    .035       0     310     .04       0     430    .035       0
#XS Ineff= 2 , 0
                          320.05         2436.96
Permanent Ineff=
       F       F
Bank Sta=289.29,307.98
XS Rating Curve= 0 ,0
Exp/Cntr=0.3,0.1

Type RM Length L Ch R = 1 ,31268   ,233,226.1,214.2
XS GIS Cut Line= 4
     2167906.123      216207.217     2168075.274      216087.905
     2168208.178      216054.679      2168383.37      215920.264
#Sta/Elev= 30
       0 2484.43    59.3 2471.19   133.2 2451.29   159.5 2441.92   186.4 2431.35
   209.1 2424.69   215.8 2421.23  227.012413.113   232.7 2411.26   236.1 2411.49
  241.522413.283   246.3 2413.86     253 2412.69   286.2 2411.91   310.5 2413.75
     324 2412.57     341 2415.72   359.5    2422   385.8 2427.74   427.7 2431.96
     433 2431.71   441.4 2429.01     460 2429.99   476.7 2429.33   481.2 2430.41
   486.9 2434.56   492.3  2436.4     514  2436.7   538.8 2438.77   564.8 2443.16
#Mann= 5 ,-1 , 0
       0      .1       0  227.01    .045       0  241.52      .1       0
  363.99     .04       0  523.99      .1       0
Bank Sta=227.01,241.52
XS Rating Curve= 0 ,0
Exp/Cntr=0.3,0.1

Type RM Length L Ch R = 1 ,31042   ,167.5,158.6,149.7
XS GIS Cut Line= 3
     2168049.599      216370.327     2168214.219      216270.648
     2168409.045       215953.49
#Sta/Elev= 30
       0 2463.61   128.3 2434.61   147.4 2429.51   158.1 2427.97   172.4 2423.85
   197.6 2414.03     213 2408.94   222.5 2407.55   253.82406.862   263.1 2404.75
   270.8 2406.75   278.5 2409.87   290.1 2408.71     306 2409.56   319.5 2412.58
   333.1 2414.43     344 2417.03   374.8 2426.49   382.5    2429   390.2 2432.83
   396.6 2434.61   444.4 2435.73   451.5 2434.14   463.3 2429.61   492.1 2430.14
     498 2432.02   509.5 2440.69   513.5 2441.67   551.7 2442.21   564.7 2443.52
#Mann= 4 ,-1 , 0
       0      .1       0   253.8    .045       0   270.8      .1       0
  342.45     .04       0
#XS Ineff= 2 , 0
                          281.46         2410.09
Permanent Ineff=
       F       F
Bank Sta=253.8,270.8
XS Rating Curve= 0 ,0
Exp/Cntr=0.5,0.3

Type RM Length L Ch R = 1 ,30883   ,81.1,77.6,78.5
XS GIS Cut Line= 4
      2168434.72      216590.827     2168348.634      216376.368
     2168333.531      216235.912     2168431.699      215989.737
#Sta/Elev= 30
       0  2439.3    63.4 2431.93    95.2 2429.44   130.9 2425.25   204.1  2419.5
   246.2 2414.68   249.5 2414.01   252.8 2412.21   259.4 2406.32  264.482402.911
   272.6  2400.2   282.5 2402.91   295.7 2404.53   325.4 2405.28   341.9  2404.8
   382.1 2406.64   410.4 2409.23   442.2 2414.17   466.9 2420.16     481 2425.58
   525.5 2436.32   530.6 2436.28   537.5 2434.89   548.6 2430.16   579.9 2430.49
     587 2432.57   592.9 2436.38   601.1 2443.13   603.8 2443.79   637.4 2442.36
#Mann= 4 ,-1 , 0
       0      .1       0  264.48    .045       0   282.5      .1       0
  472.36     .04       0
#XS Ineff= 2 , 0
          264.48    2404   282.5            2404
Permanent Ineff=
       F       F
Bank Sta=264.48,282.5
XS Rating Curve= 0 ,0
Exp/Cntr=0.5,0.3

Type RM Length L Ch R = 1 ,30805   ,221.1,236.9,246.1
XS GIS Cut Line= 4
     2168487.579      216616.502     2168418.107      216399.022
     2168403.004      216258.566     2168501.172      216012.391
#Sta/Elev= 30
       0 2436.28    43.8  2428.5   156.2 2414.88   171.4  2410.9   228.3 2407.54
   233.2 2406.15   243.1 2401.12   247.62400.058   262.9  2398.1   268.52399.905
   276.1 2402.13   328.9 2402.51   348.8 2405.65   390.8 2406.18     411 2408.33
   421.1 2410.24   435.5 2414.31   453.2 2416.75   509.7 2433.97   516.7 2433.62
   523.8 2430.61   527.1 2430.07   537.9 2431.03   559.1 2430.98   562.7 2432.42
   569.7 2437.18   580.3 2446.43   583.9 2448.31   587.4 2449.04   634.6  2447.7
#Mann= 6 ,-1 , 0
       0      .1       0   247.6    .045       0   268.5      .1       0
  288.31     .06       0  499.57     .04       0  599.57      .1       0
#XS Ineff= 2 , 0
          247.53 2401.38   268.6         2401.36
Permanent Ineff=
       F       F
Bank Sta=247.6,268.5
XS Rating Curve= 0 ,0
Exp/Cntr=0.5,0.3

Type RM Length L Ch R = 1 ,30568   ,177.2,176.9,173.6
XS GIS Cut Line= 2
     2168499.661      216625.563     2168782.083      216299.344
#Sta/Elev= 30
       0 2435.85      37  2423.9    54.4 2417.24    76.1 2406.09    96.5 2393.53
   101.32391.722   118.1 2390.76   124.2 2392.07   128.1 2393.38   132.1 2394.04
   149.8 2394.48   180.2  2398.4   188.9 2400.82   196.8 2402.26   223.6 2409.77
   256.9 2415.12     267 2415.53     282 2417.17     287  2417.2   322.1 2415.01
   345.1 2414.95   352.2 2414.53     367 2415.11   379.8 2416.24   387.3 2418.33
   392.9 2421.41   401.5 2427.12   408.9 2430.38   414.5 2431.38   431.5 2431.54
#Mann= 4 ,-1 , 0
       0      .1       0   101.3    .045       0   124.2      .1       0
     380     .04       0
Bank Sta=101.3,124.2
XS Rating Curve= 0 ,0
Exp/Cntr=0.3,0.1

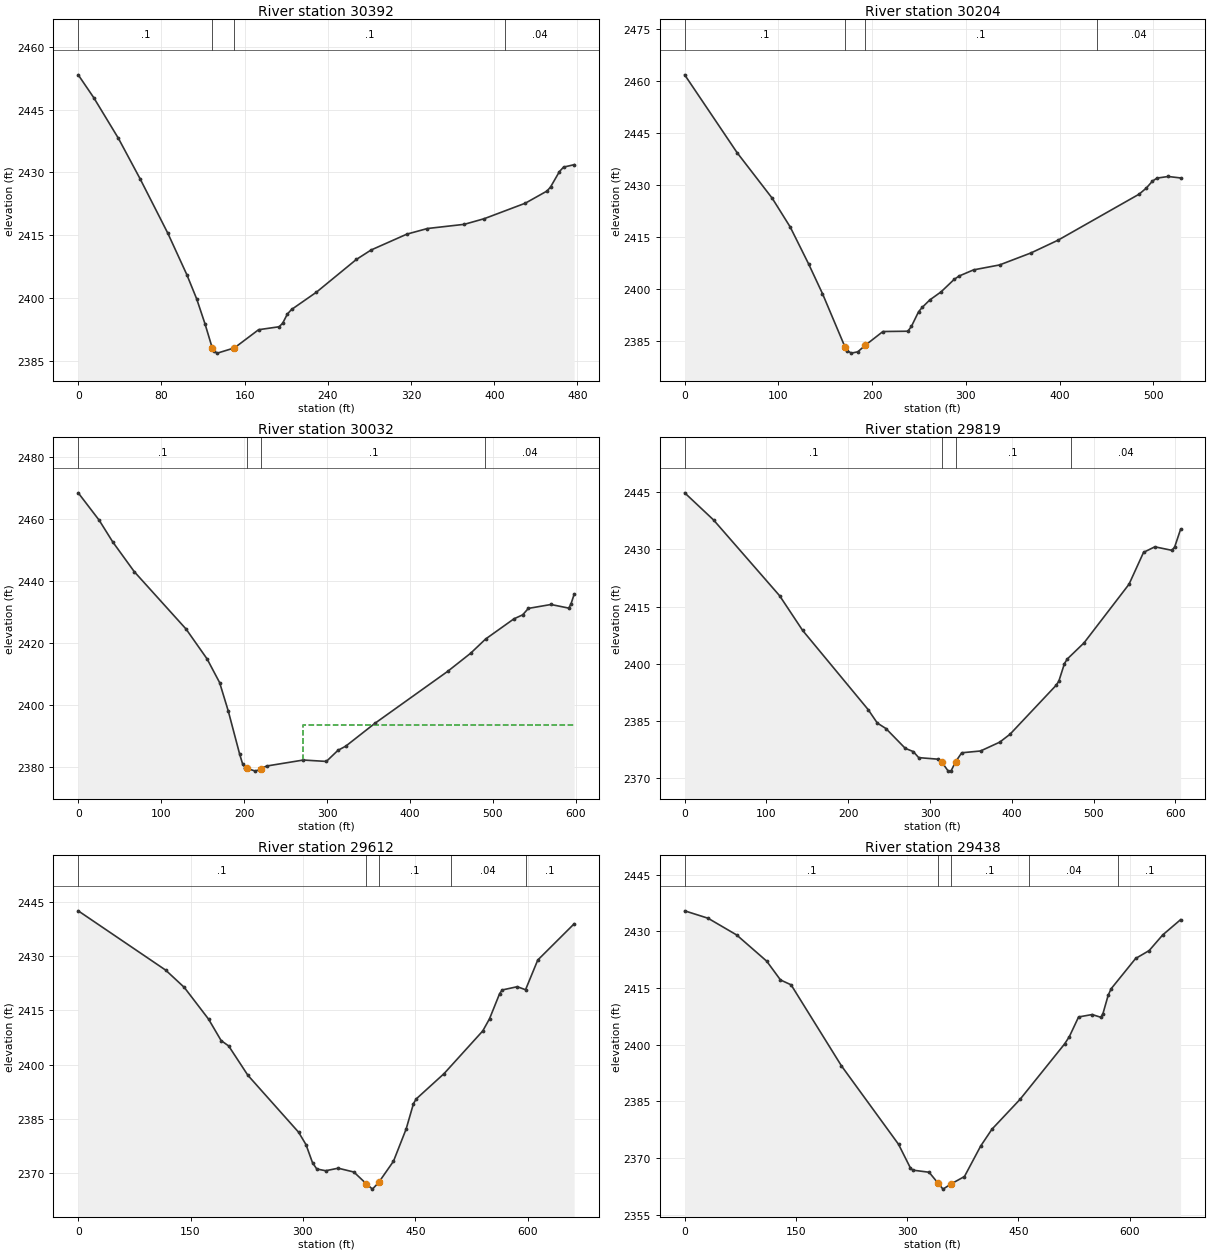
Type RM Length L Ch R = 1 ,30392   ,188.4,187.9,185.9
XS GIS Cut Line= 2
     2168620.429      216777.234     2168887.802      216382.409
#Sta/Elev= 30
       0  2453.3    14.9 2447.86    38.7 2438.11    59.6 2428.42    86.2 2415.45
   104.4 2405.59   113.9 2399.79   121.9 2393.83     1292387.966   130.4 2387.23
   133.8 2386.84   150.22388.094   173.4 2392.43   193.2 2393.14   196.6    2394
   201.1 2396.18   205.1 2397.26   228.9 2401.37   267.4 2409.21   281.6 2411.47
     316 2415.26   335.8  2416.6   371.2  2417.6   390.3 2418.94   429.8 2422.64
   450.7 2425.55   454.1 2426.51   462.6 2430.18   466.6 2431.26   476.8 2431.84
#Mann= 4 ,-1 , 0
       0      .1       0     129    .045       0   150.2      .1       0
     410     .04       0
Bank Sta=129,150.2
XS Rating Curve= 0 ,0
Exp/Cntr=0.3,0.1

Type RM Length L Ch R = 1 ,30204   ,172.9,171.3,168.8
XS GIS Cut Line= 2
     2168762.111      216918.175     2169028.258      216460.943
#Sta/Elev= 30
       0 2461.64    55.9  2439.2    93.5 2426.01   112.6 2417.75   132.2 2407.11
     147 2398.55   171.22383.045   173.5  2382.1   177.8 2381.38   184.7 2381.76
   192.72383.651   211.5 2387.61   238.1  2387.7   241.9 2389.09   249.5  2393.3
   253.3 2394.54   261.5 2396.72   273.5 2399.04   287.4 2402.62   292.7 2403.61
   308.2 2405.39   335.9 2406.81   369.5 2410.28   398.3 2413.95   484.8 2427.22
   492.4 2428.95     499 2430.97   503.8 2431.85   515.8 2432.32   529.1  2431.9
#Mann= 4 ,-1 , 0
       0      .1       0   171.2    .045       0   192.7      .1       0
     440     .04       0
Bank Sta=171.2,192.7
XS Rating Curve= 0 ,0
Exp/Cntr=0.3,0.1

Type RM Length L Ch R = 1 ,30032   ,215.6,212.8,207.4
XS GIS Cut Line= 3
      2168909.68      217064.009      2168987.26      216867.838
     2169116.251       216502.89
#Sta/Elev= 30
       0  2468.4    25.3 2459.55    41.6 2452.57    67.6 2442.95   130.1 2424.42
   155.4 2414.79   170.5 2407.16     181 2397.92   194.6 2384.13   198.2 2380.93
   201.7 2379.55   203.5 2379.48   213.6 2378.58   220.82379.389   227.1 2380.22
   271.4 2382.16   299.2 2381.71   313.2 2385.29   322.6 2386.64   357.5 2393.96
   445.4 2410.76   473.2 2416.63   491.2 2421.21   525.4 2427.73   535.9 2429.02
   542.8  2431.1   570.1 2432.36   591.5 2431.19   594.1 2432.47     598 2435.67
#Mann= 4 ,-1 , 0
       0      .1       0   203.5    .045       0   220.8      .1       0
  490.95     .04       0
#XS Ineff= 2 , 0
                          271.26         2393.35
Permanent Ineff=
       F       F
Bank Sta=203.5,220.8
XS Rating Curve= 0 ,0
Exp/Cntr=0.3,0.1

Type RM Length L Ch R = 1 ,29819   ,202.4,207,211.2
XS GIS Cut Line= 4
      2169097.18      217178.592     2169188.326      216938.647
      2169195.27      216813.647     2169265.583      216600.467
#Sta/Elev= 30
       0 2444.81    35.4 2437.68   116.1 2417.83   144.2 2408.75   224.4 2387.97
   235.5 2384.47     246 2383.04   269.7 2377.84   279.5 2376.99   286.1 2375.41
   309.1 2375.01   314.4 2374.22   322.2 2371.87   325.5 2371.87   331.32374.355
   338.7 2376.68   361.7 2377.15   385.1 2379.46   397.7 2381.53   453.9 2394.32
   457.4 2395.44   464.3 2400.07   467.8 2401.27   488.2 2405.48   543.2 2420.85
     561 2429.21   574.8 2430.66   595.6 2429.74     599  2430.6   606.3 2435.28
#Mann= 4 ,-1 , 0
       0      .1       0   314.4    .045       0   331.3      .1       0
  471.87     .04       0
Bank Sta=314.4,331.3
XS Rating Curve= 0 ,0
Exp/Cntr=0.3,0.1

Type RM Length L Ch R = 1 ,29612   ,172.9,174.4,174.7
XS GIS Cut Line= 3
     2169243.013      217293.175     2169399.263      216906.023
     2169456.555      216668.175
#Sta/Elev= 30
       0 2442.56   116.8 2426.15   141.6 2421.38     174  2412.6   190.8 2406.67
   200.9 2405.17   226.5 2397.07   294.2 2381.32   304.1 2377.88   312.8 2372.88
   318.5 2371.14   330.4 2370.66   347.1 2371.36     368  2370.3   384.42367.093
   392.8 2365.57   401.22367.433   420.9 2373.29   437.8  2382.2   447.6 2389.24
   451.3 2390.53   488.4 2397.52   540.1 2409.34   549.1 2412.69   562.6 2419.65
     566 2420.66   586.2 2421.57   597.2 2420.73   613.5 2428.94   662.1 2438.97
#Mann= 5 ,-1 , 0
       0      .1       0   384.4    .045       0   401.2      .1       0
  497.49     .04       0  597.49      .1       0
Bank Sta=384.4,401.2
XS Rating Curve= 0 ,0
Exp/Cntr=0.3,0.1

Type RM Length L Ch R = 1 ,29438   ,204.9,204.2,202.2
XS GIS Cut Line= 3
      2169307.25      217314.009     2169496.486      217088.314
     2169663.152      216753.245
#Sta/Elev= 30
       0  2435.4    31.5 2433.44    70.1 2429.01   110.6 2422.08   129.2  2417.1
   143.5 2415.81   211.4 2394.36   288.4 2373.59   304.3 2367.36   307.6 2366.75
   329.6 2366.19   341.82363.272   348.4 2361.72   359.62363.131   377.3 2365.06
   399.2 2373.14   414.4 2377.59   452.4 2385.52   512.3 2400.15   518.7 2402.08
   531.2  2407.3   549.5 2407.94   561.3 2407.21   564.1 2408.21   571.1 2413.04
   575.1 2414.77   608.1 2422.78   626.4 2424.88   644.7 2429.03   668.8 2433.07
#Mann= 5 ,-1 , 0
       0      .1       0   341.8    .045       0   359.6      .1       0
  464.53     .04       0  584.53      .1       0
Bank Sta=341.8,359.6
XS Rating Curve= 0 ,0
Exp/Cntr=0.3,0.1

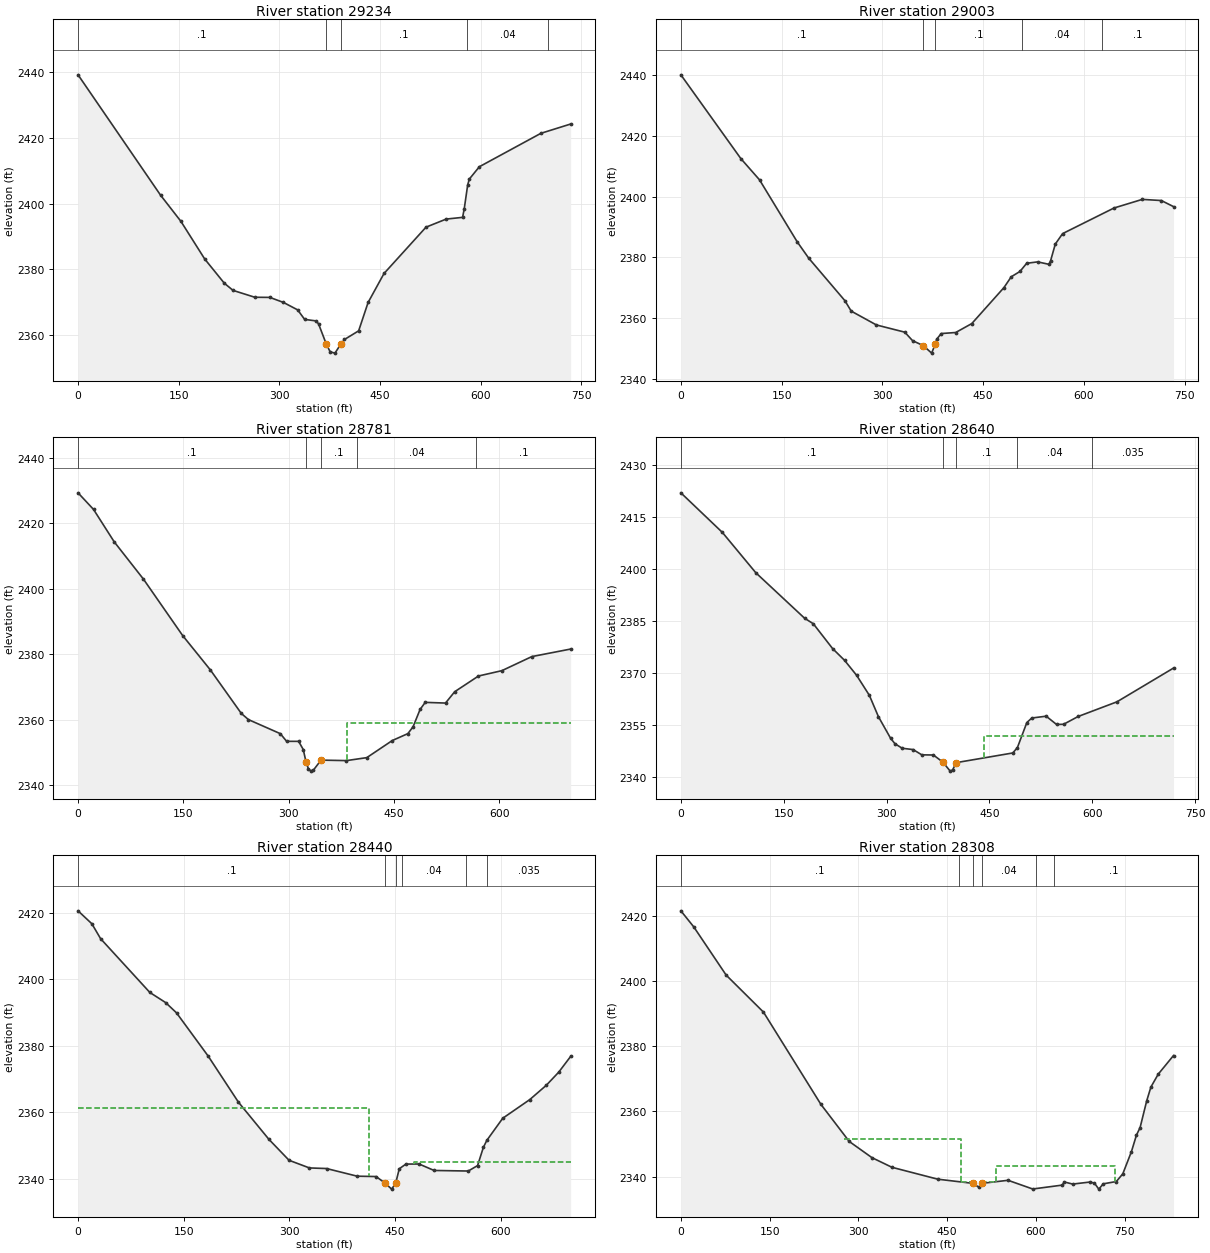
Type RM Length L Ch R = 1 ,29234   ,226.1,230.8,232.8
XS GIS Cut Line= 3
     2169574.478       217491.74     2169692.587      217141.294
     2169826.444      216802.357
#Sta/Elev= 30
       0 2439.17     123 2402.56   153.3 2394.61   188.8 2383.15     218 2375.79
     231 2373.61   263.5 2371.52   285.8 2371.48   306.1 2369.95   327.3 2367.68
   337.7 2364.79     355 2364.32   358.5  2363.4  370.122357.202   375.8 2354.92
   382.9 2354.53   391.5 2357.24   397.1 2358.68   418.2 2361.31   432.3 2369.94
     456 2378.75   518.6 2392.84   548.7  2395.3   573.1 2395.82   575.6 2398.45
   580.7 2405.69   583.2 2407.48   598.1 2411.22   689.8 2421.38   734.2 2424.21
#Mann= 5 ,-1 , 0
       0      .1       0  370.12    .045       0   391.5      .1       0
  579.81     .04       0  699.81      .1       0
Bank Sta=370.12,391.5
XS Rating Curve= 0 ,0
Exp/Cntr=0.3,0.1

Type RM Length L Ch R = 1 ,29003   ,222.9,222.1,218.5
XS GIS Cut Line= 3
     2169674.021      217544.929     2169891.811      217248.973
     2170079.966      216935.043
#Sta/Elev= 30
       0 2440.07    89.3 2412.48   117.1 2405.49   173.3 2385.04   190.4 2379.68
   244.2  2365.7   253.6 2362.26   291.1  2357.7   333.4 2355.32   344.9 2352.54
     361 2350.88   373.4 2348.42   378.82351.425     381 2353.04   387.7 2354.87
   409.2 2355.21   433.2 2358.16     481 2369.99   491.9 2373.56   504.9 2375.32
   514.9 2378.01   531.2 2378.47     548 2377.67   550.4 2378.76   557.5 2384.34
   568.4 2387.78   644.9 2396.21     687 2399.05   715.4 2398.67   733.5 2396.67
#Mann= 5 ,-1 , 0
       0      .1       0     361    .045       0   378.8      .1       0
  507.45     .04       0  627.45      .1       0
Bank Sta=361,378.8
XS Rating Curve= 0 ,0
Exp/Cntr=0.3,0.1

Type RM Length L Ch R = 1 ,28781   ,141.3,140.7,138.5
XS GIS Cut Line= 3
     2169840.236      217623.037     2170052.041      217400.814
     2170218.314      217042.855
#Sta/Elev= 30
       0 2429.22    22.1 2424.14    51.5 2414.26    93.2 2402.86     149 2385.65
   188.6 2375.12   232.5 2361.89   242.7 2359.99   288.1  2355.7   297.1 2353.36
   314.2 2353.35   320.8 2350.85  324.612347.177   328.1    2345   331.7 2344.26
   335.3 2344.58   346.12347.622   382.3 2347.47   411.3 2348.38   447.6  2353.6
   469.8 2355.71   477.2  2357.8   487.2 2363.09   494.5 2365.25   523.4 2365.04
   536.5  2368.5   570.4  2373.3   603.7 2374.93   646.4 2379.23   701.7 2381.53
#Mann= 5 ,-1 , 0
       0      .1       0  324.61    .045       0   346.1      .1       0
  396.99     .04       0  566.99      .1       0
#XS Ineff= 2 , 0
                          383.78         2358.99
Permanent Ineff=
       F       F
Bank Sta=324.61,346.1
XS Rating Curve= 0 ,0
Exp/Cntr=0.3,0.1

Type RM Length L Ch R = 1 ,28640   ,197.4,200.7,203.6
XS GIS Cut Line= 2
     2170060.722      217782.759     2170310.722      217109.148
#Sta/Elev= 30
       0 2422.01    60.5 2410.57   109.3 2398.91   180.4 2385.77   193.2 2384.16
   221.3 2376.99   238.8 2373.58   256.3 2369.27   274.9 2363.48   288.2 2357.28
   305.9 2351.06   312.3 2349.48   322.8 2348.18   338.7  2347.8   351.4 2346.28
   368.3 2346.23   382.1 2344.18   392.8 2341.57   396.3 2341.92   401.72344.026
   484.1 2346.82   490.8 2348.36   504.6 2355.61   511.8 2356.92   532.8 2357.45
   547.9 2355.06   558.2 2355.11   579.4 2357.36     636  2361.6   718.5 2371.36
#Mann= 5 ,-1 , 0
       0      .1       0   382.1    .045       0   401.7      .1       0
     490     .04       0     600    .035       0
#XS Ineff= 2 , 0
                          442.61         2351.85
Permanent Ineff=
       F       F
Bank Sta=382.1,401.7
XS Rating Curve= 0 ,0
Exp/Cntr=0.3,0.1

Type RM Length L Ch R = 1 ,28440   ,111.9,131.3,142
XS GIS Cut Line= 2
     2170124.958      217784.495     2170546.833      217227.203
#Sta/Elev= 30
       0 2420.59    19.6  2416.7      32 2412.22   101.9 2396.05   124.3 2393.01
   139.7 2389.93   184.7 2376.91   227.6 2363.07   270.8 2351.91   299.4 2345.61
   328.3 2343.31   352.6 2343.13   396.1 2340.83   422.9 2340.72   434.9 2338.87
     445 2336.94   450.72338.734   455.8 2343.06   465.2 2344.47   483.9 2344.49
   505.2 2342.55   553.7 2342.38   566.9 2344.02   575.1 2349.48     580 2351.59
   602.6 2358.24   640.9 2363.84   664.3 2368.13   682.1 2372.11     699 2376.84
#Mann= 6 ,-1 , 0
       0      .1       0   434.9    .045       0   450.7      .1       0
     460     .04       0     550     .06       0     580    .035       0
#XS Ineff= 2 , 0
          413.11 2361.33  476.67          2345.1
Permanent Ineff=
       F       F
Bank Sta=434.9,450.7
XS Rating Curve= 0 ,0
Exp/Cntr=0.3,0.1

Type RM Length L Ch R = 1 ,28308   ,26.2,19.8,20
XS GIS Cut Line= 4
     2170147.527      217801.856     2170374.958      217498.037
        2170526.      217506.717      2170659.68      217235.884
#Sta/Elev= 30
       0 2421.56    21.8 2416.63    76.6 2401.83   139.6 2390.49   236.8 2362.16
   284.6  2350.8   322.9 2345.84   356.8 2342.87   434.3 2339.22   494.22337.931
   503.3  2336.8   509.22337.946   553.1 2338.88   594.8 2336.21   644.6  2337.4
   648.3 2338.36   662.4 2337.72   691.8 2338.35   699.2    2338   706.5 2336.17
   714.1  2337.8   736.1  2338.5   747.1 2340.87   761.7 2347.69   770.2 2352.76
   776.3 2355.04   787.5 2363.26   794.6 2367.49     807 2371.45   832.8 2377.16
#Mann= 6 ,-1 , 0
       0      .1       0  469.51     .04       0   494.2    .045       0
   509.2     .04       0  600.81     .06       0  630.81      .1       0
#XS Ineff= 4 ,-1
   275.6  473.61 2351.56  473.61   494.2 2338.23   509.2     532 2338.23
  532.21  734.442343.149
Permanent Ineff=
       F       F       F       F
Bank Sta=494.2,509.2
XS Rating Curve= 0 ,0
Exp/Cntr=0.3,0.1

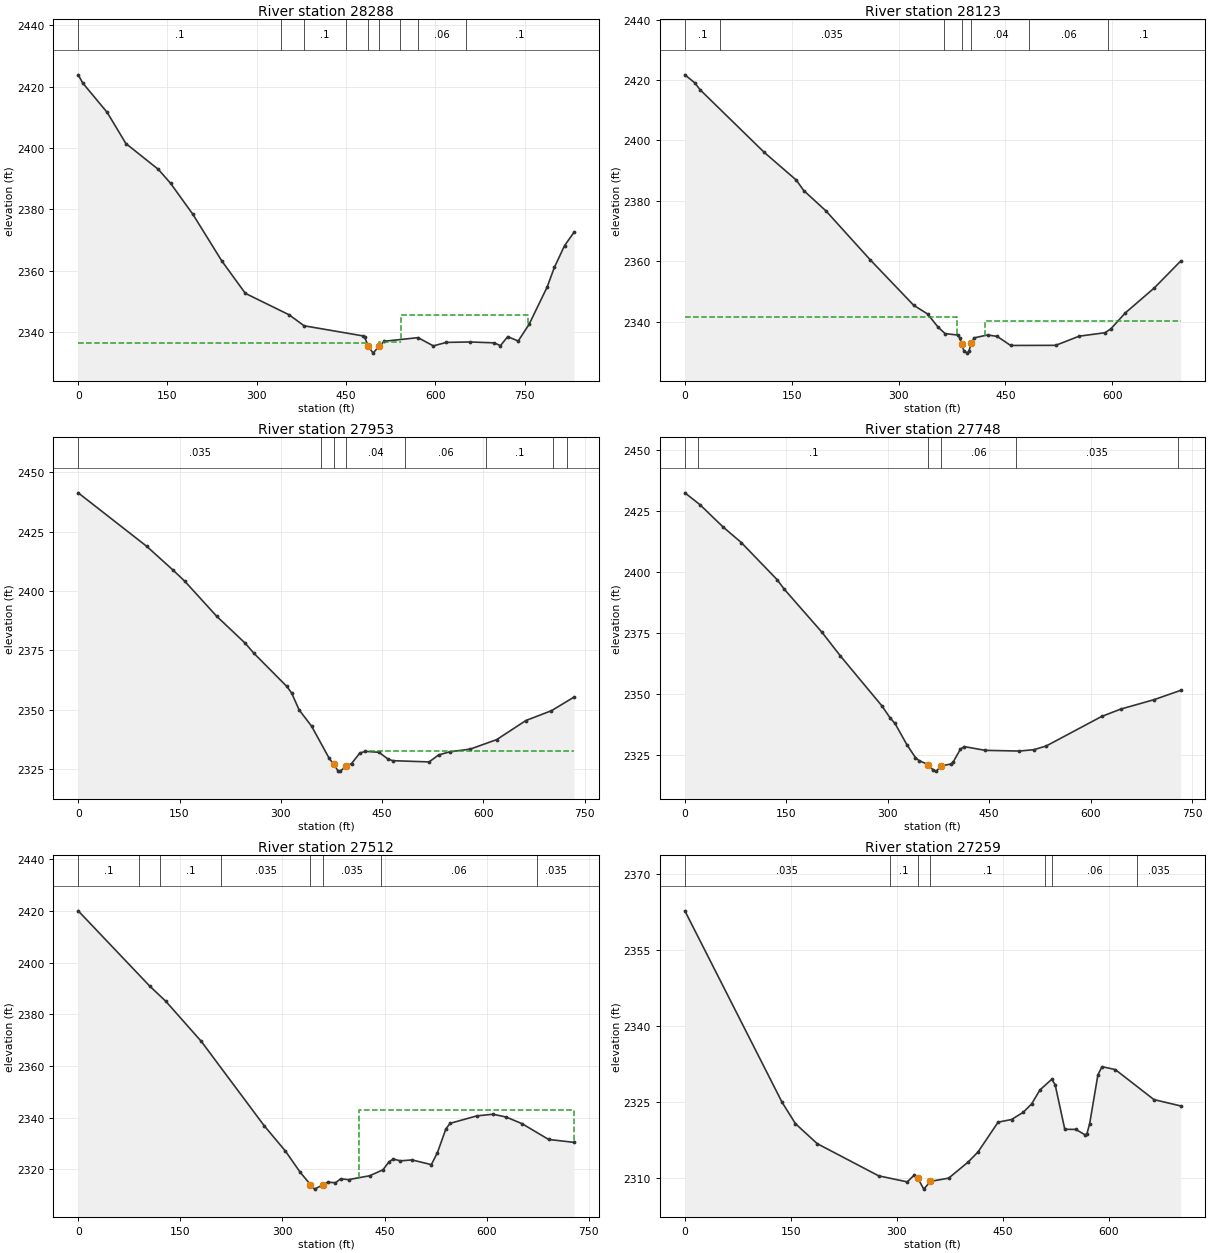
Type RM Length L Ch R = 1 ,28288   ,177.3,165.8,152.8
XS GIS Cut Line= 4
      2170159.68      217820.953     2170387.111      217517.134
     2170538.152      217525.814     2170671.833      217254.981
#Sta/Elev= 30
       0 2423.88     7.7 2421.19    48.7 2411.62    80.1 2401.48   134.8 2393.02
   155.3 2388.47   192.6  2378.4   241.3 2363.16   280.8 2352.61   354.3 2345.62
   379.5 2342.04     478 2338.75   481.3 2338.25  487.292335.362   495.4 2333.12
     5052335.309   514.1 2336.99   570.8 2338.17   596.6 2335.48   618.3 2336.62
   658.6 2336.76   698.8 2336.47   709.3 2335.56   721.5  2338.5   739.1 2337.07
   757.4 2342.51   787.7 2354.65   799.9 2361.09     817 2368.18   832.8 2372.52
#Mann= 9 ,-1 , 0
       0      .1       0     340     .06       0  379.51      .1       0
  449.51     .04       0  487.29    .045       0     505     .06       0
   540.8     .04       0   570.8     .06       0   650.8      .1       0
#XS Ineff= 3 ,-1
       0  486.082336.416   505.9     5422336.647  542.41  755.052345.714
Permanent Ineff=
       F       F       F
Bank Sta=487.29,505
XS Rating Curve= 0 ,0
Exp/Cntr=0.3,0.1

Type RM Length L Ch R = 1 ,28123   ,168.9,169.4,168.4
XS GIS Cut Line= 3
     2170487.805       217956.37       2170588.5      217659.495
      2170815.93      217352.203
#Sta/Elev= 30
       0 2421.69    14.1 2419.01    21.3 2416.77   111.4 2396.02   156.5 2386.81
   166.8 2383.38     198 2376.64   259.8 2360.53   321.1  2345.4   340.7  2342.5
   355.3 2338.17   365.2 2336.01   382.9 2335.52   385.6  2334.7   388.62332.451
   391.5 2330.41   396.2 2329.54   398.5 2330.12     4022332.779     406 2334.59
   424.9 2335.56   438.4 2335.08   457.2 2332.08   520.5 2332.12   553.3 2335.15
   589.7  2336.3   597.9 2337.59   618.3 2342.88   658.9 2351.14   695.8 2360.01
#Mann= 7 ,-1 , 0
       0      .1       0      50    .035       0  363.49     .04       0
   388.6    .045       0     402     .04       0  483.49     .06       0
  593.49      .1       0
#XS Ineff= 2 , 0
          382.16 2341.58   420.6         2340.05
Permanent Ineff=
       F       F
Bank Sta=388.6,402
XS Rating Curve= 0 ,0
Exp/Cntr=0.3,0.1

Type RM Length L Ch R = 1 ,27953   ,205.6,205.7,204.4
XS GIS Cut Line= 3
     2170582.234      218039.255     2170750.329      217716.656
     2170968.058      217417.047
#Sta/Elev= 30
       0 2441.42   101.5 2418.84   140.9  2408.7   157.9  2404.1     205 2389.36
   246.7 2378.14     260 2373.78   308.8 2359.76     316 2356.99   327.1 2349.85
   345.6 2342.96   371.6 2329.43   378.1 2326.93   384.4 2324.26   388.1    2324
   396.52326.023   404.7 2327.19   416.9 2331.57     425 2332.35   445.3 2331.95
   458.5 2329.15   465.6 2328.41   519.6 2327.89   533.7 2330.84   550.1 2332.13
   580.7 2333.31   619.7  2337.3   662.9 2345.35   700.8  2349.5   734.1 2355.22
#Mann= 8 ,-1 , 0
       0    .035       0     360     .04       0   378.1    .045       0
   396.5     .04       0  483.77     .06       0  603.77      .1       0
  703.77     .06       0  723.77    .035       0
#XS Ineff= 2 , 0
                          432.79          2332.5
Permanent Ineff=
       F       F
Bank Sta=378.1,396.5
XS Rating Curve= 0 ,0
Exp/Cntr=0.3,0.1

Type RM Length L Ch R = 1 ,27748   ,227.7,235.2,239.6
XS GIS Cut Line= 3
     2170729.662      218128.522      2170923.82      217813.643
     2171138.772      217520.756
#Sta/Elev= 30
       0 2432.36    22.2 2427.55    56.4 2418.41    83.4 2412.02   136.3 2396.85
   147.2 2392.84   202.9 2375.23   229.8 2365.65   291.5  2345.1   303.2 2340.34
   310.8 2337.92   328.5 2329.17     341 2323.97   346.2 2322.76   360.12321.022
   367.6 2318.72     372 2318.41     3792320.583   394.2 2321.34     397 2322.23
   407.6 2327.44   413.3 2328.45   444.1 2326.92   494.7 2326.63   516.2 2327.19
   534.3 2328.69   616.4  2340.8   644.6 2343.81   693.9 2347.67   733.2 2351.47
#Mann= 6 ,-1 , 0
       0    .035       0      20      .1       0   360.1    .045       0
     379     .06       0  489.93    .035       0  729.93     .08       0
Bank Sta=360.1,379
XS Rating Curve= 0 ,0
Exp/Cntr=0.3,0.1

Type RM Length L Ch R = 1 ,27512   ,258.7,252.9,246.8
XS GIS Cut Line= 3
     2170776.642      218175.183     2171083.895      217979.865
     2171393.087      217787.548
#Sta/Elev= 30
       0 2419.98   104.8 2390.96   128.6 2385.04   180.8 2369.52     273 2336.98
   304.4 2327.11   325.8 2319.02   341.1 2314.17   347.2 2312.41   359.12314.019
   366.3 2315.09   377.9  2314.9   385.7  2316.4   397.2 2316.08   428.1 2317.58
   447.5 2319.86   456.8 2323.03   462.9 2324.02   473.4 2323.34   490.3  2323.7
   518.7 2321.88   527.6 2326.49     540 2335.64   546.2 2337.84   585.4 2340.71
   609.2 2341.36   628.3  2340.3   652.1 2337.69   690.9 2331.62   728.2 2330.48
#Mann= 8 ,-1 , 0
       0      .1       0      90    .035       0     120      .1       0
     210    .035       0   341.1    .045       0   359.1    .035       0
  444.08     .06       0  674.08    .035       0
#XS Ineff= 2 , 0
                          412.61         2342.86
Permanent Ineff=
       F       F
Bank Sta=341.1,359.1
XS Rating Curve= 0 ,0
Exp/Cntr=0.3,0.1

Type RM Length L Ch R = 1 ,27259   ,147.3,152.4,158
XS GIS Cut Line= 2
     2171064.194      218449.425     2171446.864      217860.956
#Sta/Elev= 30
       0 2362.68   137.6 2324.93   156.6 2320.69   187.4 2316.76   274.4 2310.41
   314.8 2309.22     325 2310.58   329.92309.903   338.3 2307.79   347.72309.317
   373.5 2309.96   400.9 2313.11   415.1 2315.13   443.5    2321   462.5 2321.52
   479.2 2322.96     491 2324.61   502.7 2327.36   519.4 2329.45   524.2 2328.41
   537.9 2319.59   553.5 2319.57   566.8 2318.48   569.2 2318.68   573.1  2320.7
   584.8 2330.34   590.6 2331.95   609.5 2331.36   664.1 2325.45   701.9  2324.2
#Mann= 7 ,-1 , 0
       0    .035       0     290      .1       0   329.9    .045       0
   347.7      .1       0     510     .04       0     520     .06       0
     640    .035       0
Bank Sta=329.9,347.7
XS Rating Curve= 0 ,0
Exp/Cntr=0.3,0.1

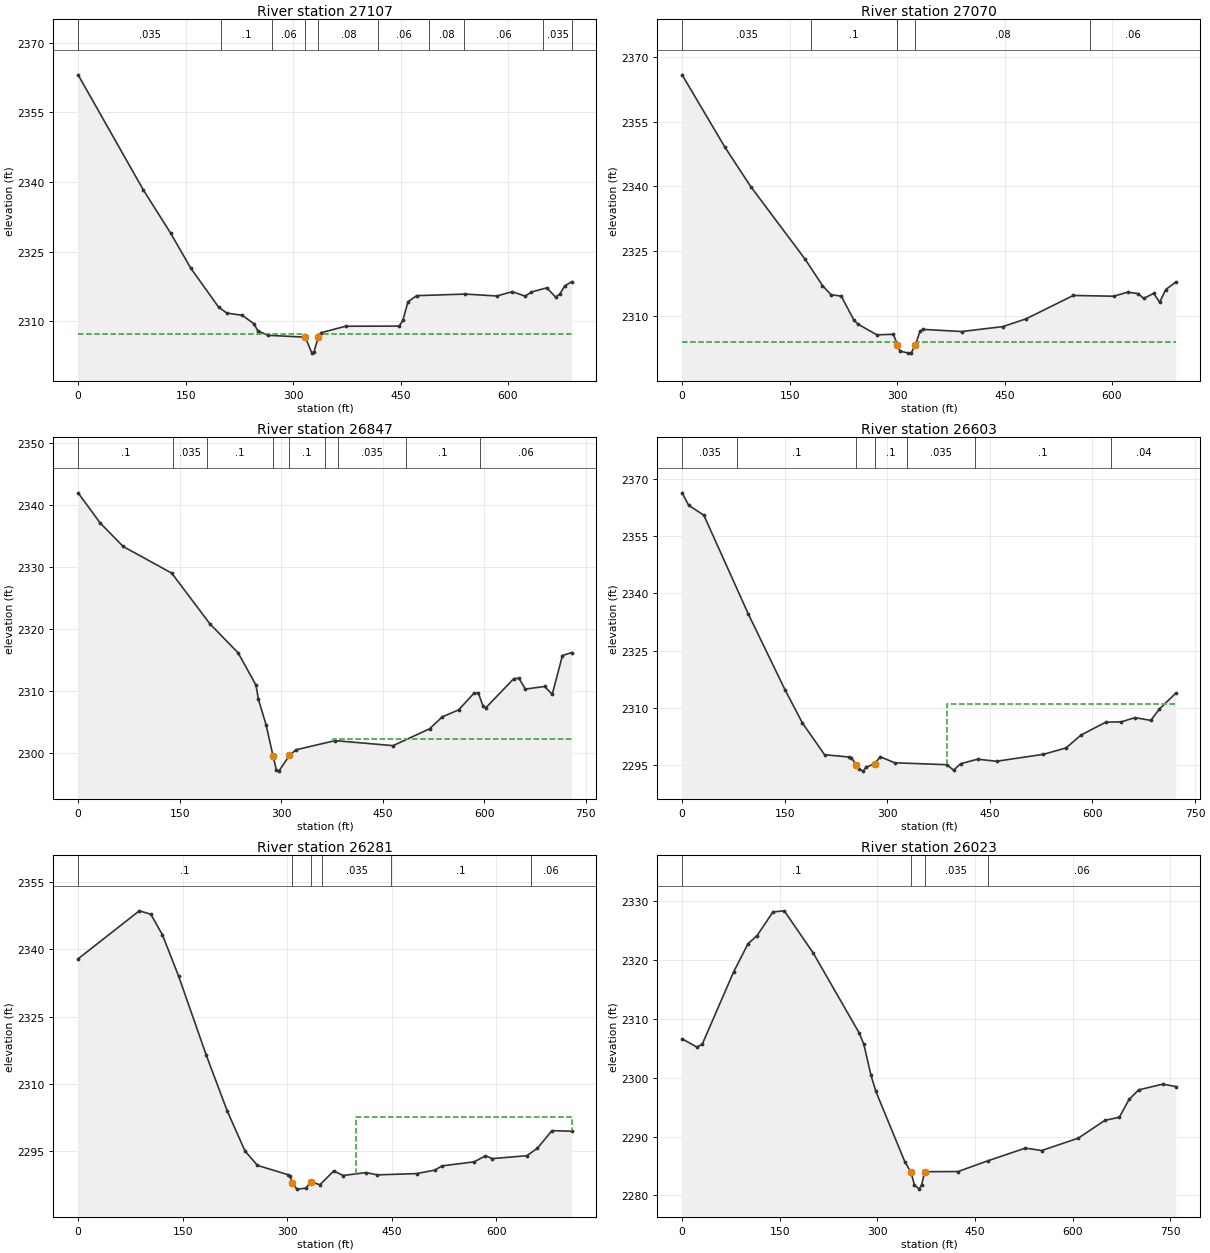
Type RM Length L Ch R = 1 ,27107   ,39.7,37.5,37.4
XS GIS Cut Line= 3
     2171081.555       218465.05     2171392.319      218248.037
     2171539.888      217975.467
#Sta/Elev= 30
       0 2363.05    90.7 2338.36   129.2 2328.95   157.2 2321.44     196 2313.06
   207.5 2311.77   229.3 2311.28   245.3 2309.46   250.9 2307.94   265.1 2306.97
     3172306.583   326.3 2303.14   329.3 2303.44  335.292306.664   339.3 2307.55
   373.3 2308.93   448.3 2308.96   453.2 2310.19   460.4  2314.2   472.5 2315.51
   540.3 2315.85   584.5 2315.44   605.7 2316.37   624.2 2315.41   632.3 2316.29
   654.1  2317.2   666.5 2315.19   672.4  2315.9   679.3 2317.64     689 2318.51
#Mann= 10 ,-1 , 0
       0    .035       0     200      .1       0     270     .06       0
     317    .045       0  335.29     .08       0  419.04     .06       0
  489.04     .08       0  539.04     .06       0  649.04    .035       0
  688.99     .06       0
#XS Ineff= 2 , 0
             317  2307.2  335.29          2307.2
Permanent Ineff=
       F       F
Bank Sta=317,335.29
XS Rating Curve= 0 ,0
Exp/Cntr=0.3,0.1

Type RM Length L Ch R = 1 ,27070   ,228.9,222.4,213.9
XS GIS Cut Line= 3
     2171102.388      218494.564     2171413.152       218277.55
     2171560.722      218004.981
#Sta/Elev= 30
       0 2365.79    59.8 2349.06    95.8 2339.96   171.9 2323.14   195.9  2317.1
   207.7    2315   222.1 2314.64   239.9 2309.08   245.4 2308.18   271.9 2305.71
   294.9 2305.83   300.6 2303.35   303.9 2301.97   315.9 2301.48   319.9  2301.6
  325.572303.307   331.9  2306.5   335.9 2306.97   390.4 2306.47   447.5 2307.61
     480  2309.4     546 2314.81   602.4 2314.63   621.8 2315.57   636.7 2315.23
   644.1 2314.12   658.1 2315.27   666.5 2313.24     675 2316.17     689 2317.92
#Mann= 6 ,-1 , 0
       0    .035       0     180      .1       0     300     .06       0
   300.6    .045       0  325.57     .08       0  569.04     .06       0
#XS Ineff= 2 , 0
           299.9 2303.99  325.92         2303.99
Permanent Ineff=
       F       F
Bank Sta=300.6,325.57
XS Rating Curve= 0 ,0
Exp/Cntr=0.3,0.1

Type RM Length L Ch R = 1 ,26847   ,244.3,243.8,239.4
XS GIS Cut Line= 3
     2171351.925      218725.812     2171531.215      218408.815
     2171711.779      218091.484
#Sta/Elev= 30
       0    2342    32.6 2337.13    66.4 2333.34   138.3 2329.02   194.8 2320.81
   236.3 2316.14   262.7 2310.93   266.4  2308.6   277.7 2304.49  287.892299.505
   292.8 2297.25   296.6 2297.01   312.22299.556   321.6 2300.45   379.5 2301.94
   465.3 2301.13   519.2 2303.85   537.8 2305.77   562.2 2306.92   584.7  2309.6
   591.3 2309.64   598.3 2307.48   602.2 2307.24   643.8 2311.98   651.3 2312.01
   660.8 2310.27   689.1  2310.7   700.4 2309.42   715.5  2315.7   729.3 2316.18
#Mann= 9 ,-1 , 0
       0      .1       0     140    .035       0     190      .1       0
  287.89    .045       0   312.2      .1       0  364.19     .06       0
  384.19    .035       0  484.19      .1       0  594.19     .06       0
#XS Ineff= 2 , 0
                          376.29         2302.17
Permanent Ineff=
       F       F
Bank Sta=287.89,312.2
XS Rating Curve= 0 ,0
Exp/Cntr=0.3,0.1

Type RM Length L Ch R = 1 ,26603   ,318.6,322.7,311.8
XS GIS Cut Line= 5
     2171607.597      218801.8562171691.76349363218615.445986908
 2171720.6092172 218547.469282162171790.89648967218340.372854345
        2171776.      218116.092
#Sta/Elev= 30
       0 2366.39     9.5 2363.14    31.8 2360.52    96.7 2334.64   150.8  2314.6
   175.9 2306.02   208.3 2297.68   243.9 2297.09   247.5 2296.88 254.5912295.073
   258.2 2293.94   264.8 2293.38   268.8 2294.35   281.42295.349   289.9 2297.14
   310.7 2295.57   386.9 2295.07   396.9 2293.64   407.3 2295.33     432 2296.51
   459.7 2295.97   528.3 2297.79   561.5 2299.48   583.2 2302.84   619.4 2306.22
   642.3 2306.31   662.1 2307.42   685.2 2306.69   697.8 2309.67   721.8 2313.84
#Mann= 7 ,-1 , 0
       0    .035       0      80      .1       0 254.591    .045       0
   281.4      .1       0  328.37    .035       0  428.37      .1       0
  627.07     .04       0
#XS Ineff= 2 , 0
                          387.39         2310.92
Permanent Ineff=
       F       F
Bank Sta=254.591,281.4
XS Rating Curve= 0 ,0
Exp/Cntr=0.3,0.1

Type RM Length L Ch R = 1 ,26281   ,262,257.2,244.5
XS GIS Cut Line= 3
     2172012.111      218951.162     2171953.083      218586.578
     2171984.289       218249.26
#Sta/Elev= 30
       0 2337.88    87.8 2348.59   104.3 2347.83   120.9 2343.25   144.2    2334
     184 2316.31   213.9 2303.93   239.4    2295   257.2 2291.79   300.4 2289.74
   303.7 2289.37   307.22287.957   313.8 2286.49   326.9  2286.7   333.4  2288.1
   346.9 2287.48   366.8 2290.56     380 2289.53     413 2290.18   429.4 2289.67
   485.5 2289.96   511.8 2290.73   521.7 2291.67   568.1 2292.58   584.3 2293.92
   594.2  2293.3   643.6 2293.95   658.6 2295.59   679.7 2299.54   708.1 2299.41
#Mann= 6 ,-1 , 0
       0      .1       0   307.2    .045       0   333.4      .1       0
     350    .035       0  449.33      .1       0  649.33     .06       0
#XS Ineff= 2 , 0
                          398.37         2302.49
Permanent Ineff=
       F       F
Bank Sta=307.2,333.4
XS Rating Curve= 0 ,0
Exp/Cntr=0.3,0.1

Type RM Length L Ch R = 1 ,26023   ,336.6,350.6,360.9
XS GIS Cut Line= 2
     2172352.388      218921.648     2171999.958      218249.773
#Sta/Elev= 30
       0 2306.59    22.9 2305.18      31 2305.69    79.2 2317.95   101.4 2322.74
   115.3 2324.12   139.6 2328.12     157 2328.31   201.5 2321.15   271.8 2307.65
   279.3 2305.65   290.2 2300.44   297.8 2297.65   342.2 2285.75  351.762283.927
   357.1 2281.77   364.5 2281.08   368.2 2281.86   372.82284.031   424.2 2284.07
     470 2285.89   527.5 2288.04   552.7 2287.63     609 2289.74   649.7 2292.75
     672 2293.28   686.8  2296.3   701.6 2297.92   738.7  2298.9   758.7 2298.48
#Mann= 4 ,-1 , 0
       0      .1       0  351.76    .045       0   372.8    .035       0
     470     .06       0
Bank Sta=351.76,372.8
XS Rating Curve= 0 ,0
Exp/Cntr=0.3,0.1