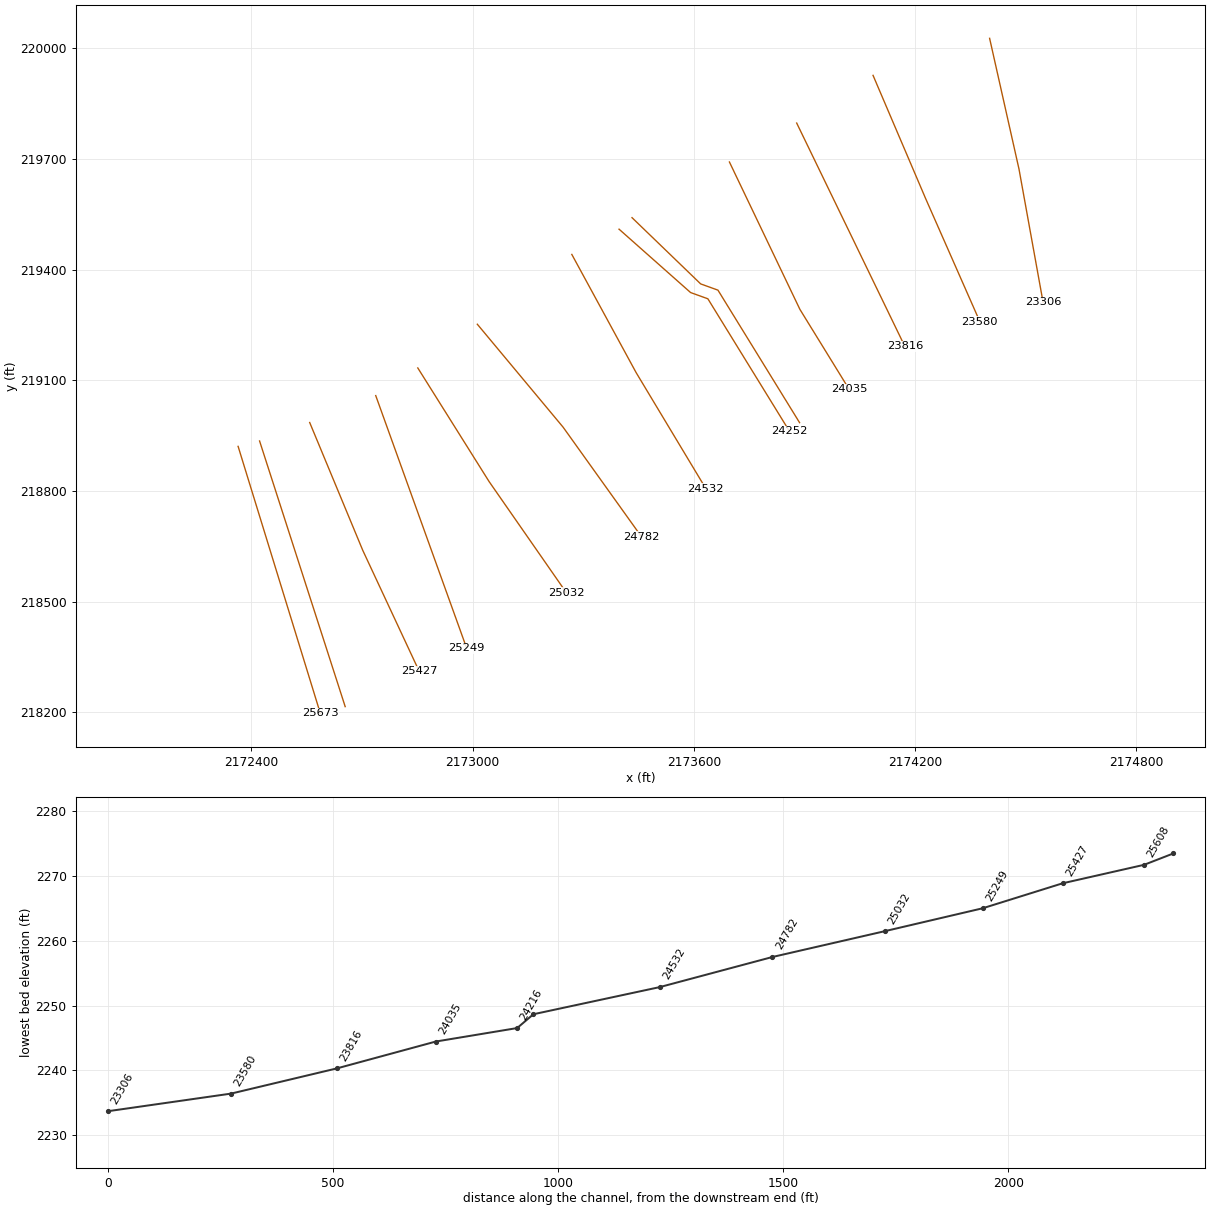
HEC-RAS study SWTSPRNGSCK.prj: SWTSPRNGSCK

--- SWTSPRNGSCK.g01 (geometry) --- (continued)

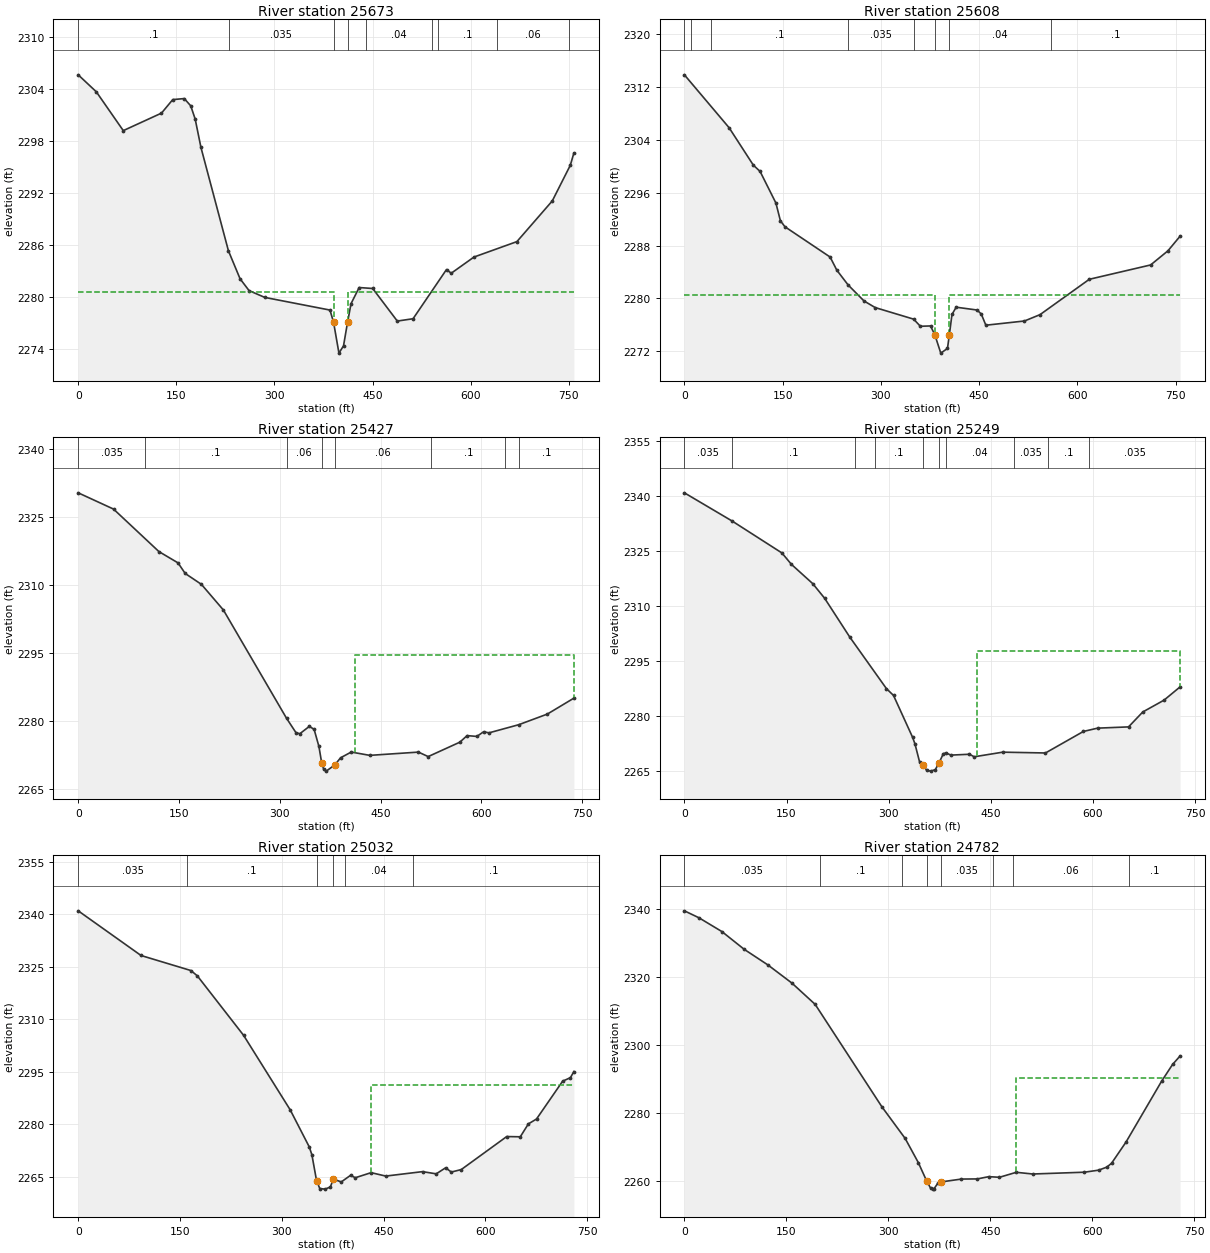
Type RM Length L Ch R = 1 ,25673   ,65.1,65.2,65.4
XS GIS Cut Line= 2
     2172364.018      218920.672      2172586.98      218196.604
#Sta/Elev= 30
       0 2305.59    27.7 2303.63    68.9 2299.15   127.3 2301.17   144.5 2302.73
   162.1 2302.85     172 2302.01   178.8 2300.48   187.6 2297.21   229.6 2285.28
   247.4 2282.05   261.2 2280.68   285.2  2279.9   384.8 2278.44   390.3 2277.03
   398.5 2273.47   405.5 2274.31  411.652277.026     417 2279.18   429.4 2281.04
   450.1 2280.93   487.7 2277.17   511.8 2277.44   562.9 2283.12   570.1 2282.69
   604.9 2284.56   670.5 2286.34   724.6 2291.04   752.1 2295.15   757.6 2296.57
#Mann= 9 ,-1 , 0
       0      .1       0     230    .035       0   390.3    .045       0
  411.65    .035       0     440     .04       0     540     .06       0
     550      .1       0     640     .06       0     750      .1       0
#XS Ineff= 2 , 0
           390.3  2280.5  411.65          2280.5
Permanent Ineff=
       F       F
Bank Sta=390.3,411.65
XS Rating Curve= 0 ,0
Exp/Cntr=0.3,0.1

Type RM Length L Ch R = 1 ,25608   ,178.3,180.9,181.6
XS GIS Cut Line= 2
2172422.22681204218935.3044106152172654.42583717 218214.85986779
#Sta/Elev= 30
       0 2313.88    68.3 2305.86   105.3 2300.19   115.6 2299.24   139.7 2294.46
   146.6 2291.77   153.5 2290.86   222.5 2286.27   232.8 2284.27     250 2282.04
   274.2 2279.62   291.4 2278.61     350 2276.86   360.3 2275.78   375.8 2275.83
   382.42274.489   391.5 2271.71   401.7 2272.42 404.5772274.497   408.6 2277.57
     415 2278.67     447 2278.24   453.4 2277.62   460.3 2275.94   519.3 2276.58
     543 2277.54   618.3  2282.9   711.9 2285.07   738.3 2287.21   756.9 2289.43
#Mann= 8 ,-1 , 0
       0      .1       0      10    .035       0      40      .1       0
     250    .035       0     350     .04       0   382.4    .045       0
 404.577     .04       0     560      .1       0
#XS Ineff= 2 , 0
           382.4  2280.5 404.577          2280.5
Permanent Ineff=
       F       F
Bank Sta=382.4,404.577
XS Rating Curve= 0 ,0
Exp/Cntr(USF)=0,0
Exp/Cntr=0.3,0.1

Type RM Length L Ch R = 1 ,25427   ,178.3,177.4,176
XS GIS Cut Line= 3
      2172558.15      218985.391     2172702.129       218638.59
     2172855.201      218310.579
#Sta/Elev= 30
       0 2330.29    52.6  2326.7   120.1 2317.32   148.5 2314.83   159.2 2312.49
   183.3 2310.09     216 2304.43     310 2280.52   323.9 2277.37   329.7 2277.11
   343.9 2278.74     351 2278.08   358.1 2274.33   362.4 2270.57   365.2  2269.3
   369.1 2268.86     3822270.258   390.3  2271.8   406.2 2273.07   433.8 2272.34
   506.2 2273.06   520.7 2272.07   567.8 2275.25   578.6  2276.7   593.1 2276.52
   603.2 2277.55   611.2 2277.31   655.5 2279.11   698.1 2281.46   737.5 2284.97
#Mann= 8 ,-1 , 0
       0    .035       0     100      .1       0     310     .06       0
   362.4    .045       0     382     .06       0   525.5      .1       0
   635.5     .06       0   655.5      .1       0
#XS Ineff= 2 , 0
                          411.27         2294.42
Permanent Ineff=
       F       F
Bank Sta=362.4,382
XS Rating Curve= 0 ,0
Exp/Cntr=0.3,0.1

Type RM Length L Ch R = 1 ,25249   ,213.1,217.1,221
XS GIS Cut Line= 3
     2172737.223       219058.43     2172860.517      218715.947
      2172983.81      218373.463
#Sta/Elev= 30
       0 2340.89      70 2333.21   143.2  2324.5   157.2 2321.38   188.5 2316.13
     206 2312.13   242.8 2301.58   296.7 2287.51   307.1 2285.65     335 2274.29
   338.5 2272.51   345.4 2267.52   350.92266.579   355.9 2265.21   361.9 2265.01
   368.5 2265.42   373.8 2267.19   380.3 2269.77     384 2269.97   391.6 2269.38
   418.7 2269.61   425.6 2268.92   467.5 2270.18   530.3 2269.96     586 2275.83
   606.8 2276.73   652.3 2277.07   673.2 2281.14   704.4 2284.36     728 2287.98
#Mann= 10 ,-1 , 0
       0    .035       0      70      .1       0     250    .035       0
     280      .1       0   350.9    .045       0   373.8      .1       0
     384     .04       0     484    .035       0     534      .1       0
     594    .035       0
#XS Ineff= 2 , 0
                          429.42         2297.82
Permanent Ineff=
       F       F
Bank Sta=350.9,373.8
XS Rating Curve= 0 ,0
Exp/Cntr=0.3,0.1

Type RM Length L Ch R = 1 ,25032   ,247.9,250,250.1
XS GIS Cut Line= 3
     2172851.334      219133.374     2173044.454      218825.605
     2173254.069      218524.131
#Sta/Elev= 30
       0 2341.04    92.6 2328.27   166.1 2323.97   175.6 2322.44   243.7 2305.46
   312.4 2284.15   340.5 2273.56   344.4 2271.29  351.292263.879     356 2261.65
   363.8 2261.48   371.7  2262.1  375.842264.361   387.7 2263.54   401.3 2265.42
   408.4 2264.74   431.7 2266.19   453.2 2265.21   507.4 2266.48   527.6 2265.85
   541.5 2267.58   549.8 2266.36   564.5 2267.07   631.5 2276.51   651.5 2276.44
   663.4 2280.13   675.4 2281.52   713.9 2292.34   725.4 2293.35   730.5 2295.09
#Mann= 6 ,-1 , 0
       0    .035       0     160      .1       0  351.29    .045       0
  375.84      .1       0  393.34     .04       0  493.34      .1       0
#XS Ineff= 2 , 0
                          432.16         2291.17
Permanent Ineff=
       F       F
Bank Sta=351.29,375.84
XS Rating Curve= 0 ,0
Exp/Cntr=0.3,0.1

Type RM Length L Ch R = 1 ,24782   ,251.9,250,247.5
XS GIS Cut Line= 3
     2173012.738      219251.922     2173245.581      218972.511
      2173458.34      218675.155
#Sta/Elev= 30
       0 2339.57    21.5 2337.51    55.2 2333.45    87.9 2328.23   122.8 2323.62
   158.2 2318.26   192.4 2311.98   290.5 2281.79   324.8 2272.44   344.1 2265.34
   356.22259.996   362.2 2257.78   365.1 2257.49   367.3 2257.62   373.3 2259.35
   376.8 2259.59   407.6 2260.46   430.9  2260.5   447.9 2261.17   463.5 2260.98
   488.3 2262.45   512.5 2261.95   588.5 2262.48   609.3 2263.08   621.5 2263.98
   628.5 2265.13   649.7 2271.36   702.1 2289.32   718.2 2294.25   729.3 2296.77
#Mann= 8 ,-1 , 0
       0    .035       0     200      .1       0     320    .035       0
   356.2    .045       0   376.8    .035       0  453.71     .04       0
  483.71     .06       0  653.71      .1       0
#XS Ineff= 2 , 0
                          488.27         2290.26
Permanent Ineff=
       F       F
Bank Sta=356.2,376.8
XS Rating Curve= 0 ,0
Exp/Cntr=0.3,0.1

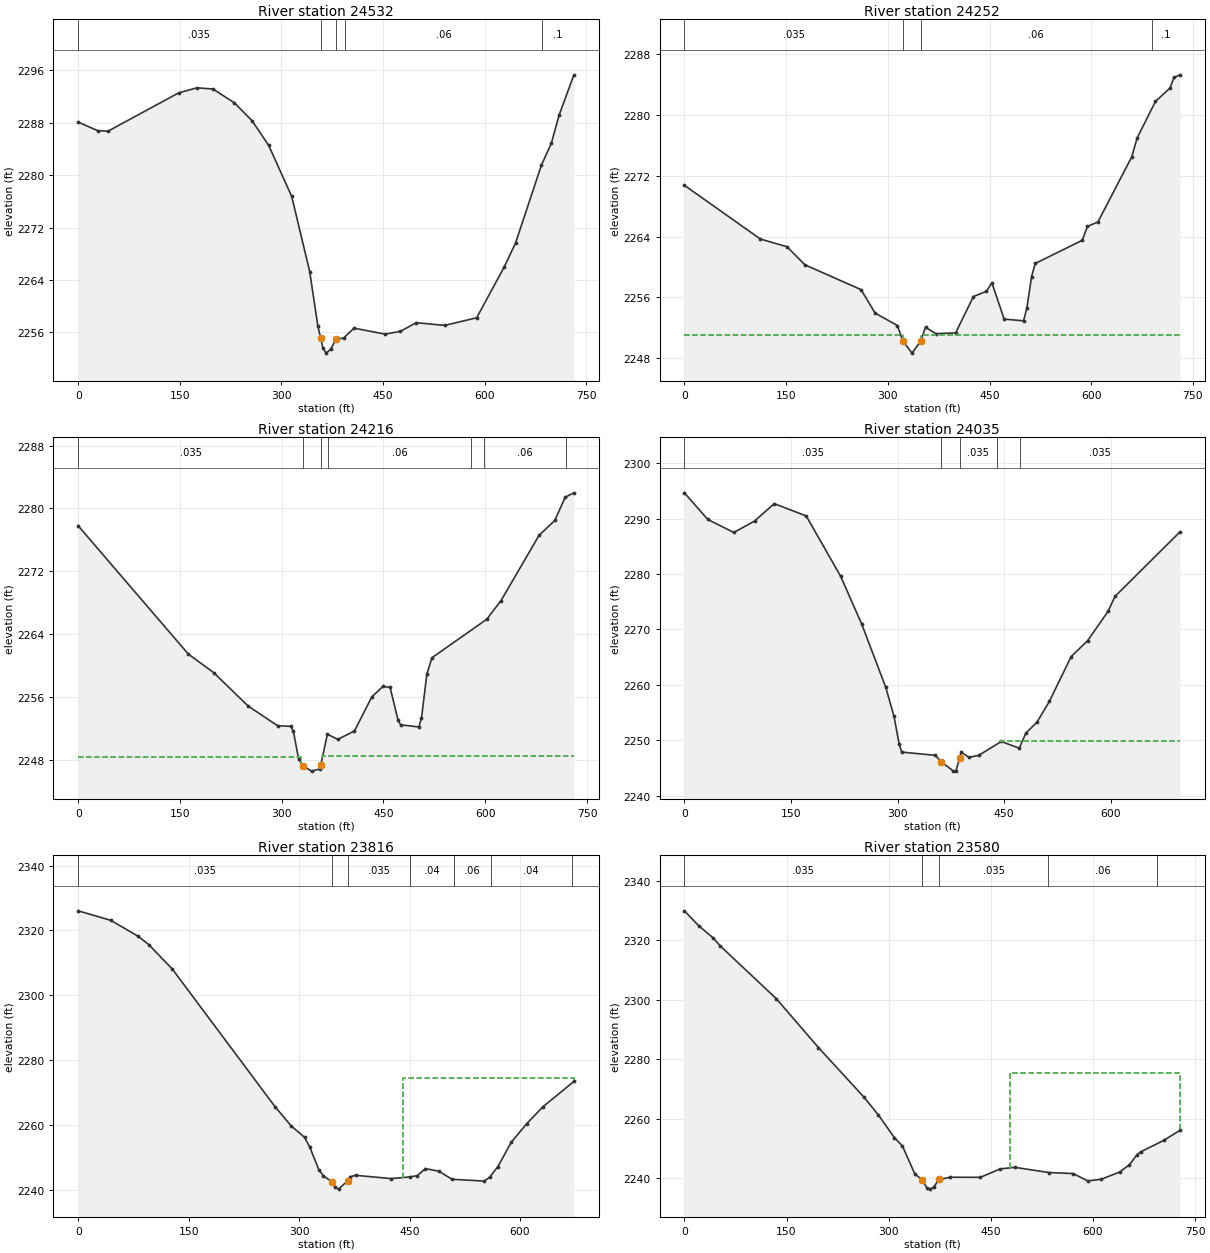
Type RM Length L Ch R = 1 ,24532   ,280.5,280.8,279.8
XS GIS Cut Line= 3
     2173269.029       219441.23     2173443.178      219121.147
      2173632.51      218806.148
#Sta/Elev= 30
       0 2288.08    28.9 2286.77    43.9 2286.69   148.4 2292.54   175.4 2293.31
   199.1 2293.12   230.5 2291.03   256.8 2288.28   281.3 2284.52   315.2 2276.76
   341.8 2265.29   353.8 2257.02   357.92255.156   361.3 2253.65     366 2252.85
   372.8 2253.44   380.62254.965   391.9 2255.15   407.2 2256.66   453.1 2255.75
   475.7 2256.17   499.1 2257.49   541.2 2257.08   588.3 2258.24     629 2265.98
   645.7 2269.63   683.9  2281.5   698.6 2284.86   710.2 2289.18   731.9 2295.29
#Mann= 5 ,-1 , 0
       0    .035       0   357.9    .045       0   380.6    .035       0
  394.39     .06       0  684.39      .1       0
Bank Sta=357.9,380.6
XS Rating Curve= 0 ,0
Exp/Cntr=0.3,0.1

Type RM Length L Ch R = 1 ,24252   ,35.8,36,36.2
XS GIS Cut Line= 4
     2173397.093      219509.755     2173591.104       219337.88
     2173637.979      219320.953     2173859.333      218961.578
#Sta/Elev= 30
       0 2270.75     112 2263.68   151.4 2262.66   177.6 2260.29   260.5 2257.02
   281.3 2253.93   314.2 2252.29   322.1 2250.28   335.7 2248.66   348.32250.235
   355.6 2252.06     371 2251.22   400.1 2251.33   426.3 2256.11   445.4 2256.79
   453.5 2257.92   471.6 2253.14   500.2 2252.91     505 2254.54   512.1 2258.74
   517.4 2260.46   586.8 2263.51   594.5 2265.34   609.9 2265.92     660 2274.53
   667.7 2276.97   694.7 2281.78   716.3 2283.56     722 2284.94   731.1 2285.29
#Mann= 4 ,-1 , 0
       0    .035       0   322.1    .045       0   348.3     .06       0
  689.03      .1       0
#XS Ineff= 2 , 0
           322.1 2251.06   348.3         2251.06
Permanent Ineff=
       F       F
Bank Sta=322.1,348.3
XS Rating Curve= 0 ,0
Exp/Cntr=0.3,0.1

Type RM Length L Ch R = 1 ,24216   ,180.9,180.7,176.7
XS GIS Cut Line= 4
      2173432.25      219541.005     2173618.447      219361.318
     2173665.322      219344.391     2173886.677      218985.016
#Sta/Elev= 30
       0 2277.78   162.3 2261.44   199.7 2259.08   250.5 2254.82   293.8 2252.32
   313.3 2252.23   317.2  2251.6   324.9 2248.09   331.52247.161   344.2 2246.53
   355.7  2246.8   357.72247.347   367.3 2251.23   382.7 2250.58   407.2 2251.64
   432.8 2255.99   449.3 2257.32   459.8 2257.19   471.3 2253.08   475.2 2252.43
   502.1 2252.16     506 2253.25   513.9 2258.84   521.4 2260.97   602.3 2265.88
   623.3 2268.26   679.4 2276.57   702.5 2278.46   717.9 2281.42   730.7 2281.98
#Mann= 7 ,-1 , 0
       0    .035       0   331.5    .045       0   357.7    .035       0
   368.6     .06       0   578.6    .035       0   598.6     .06       0
   718.6      .1       0
#XS Ineff= 2 , 0
          328.56 2248.32  359.66         2248.52
Permanent Ineff=
       F       F
Bank Sta=331.5,357.7
XS Rating Curve= 0 ,0
Exp/Cntr=0.3,0.1

Type RM Length L Ch R = 1 ,24035   ,216.8,219,217.6
XS GIS Cut Line= 3
     2173696.442      219691.897     2173887.545      219292.307
     2174021.225      219075.293
#Sta/Elev= 30
       0 2294.64      33 2289.83    69.6 2287.49    98.7 2289.55   126.5 2292.69
   171.5 2290.47     220 2279.58   249.5    2271   283.5 2259.55   295.1 2254.31
   302.4 2249.29     306 2247.88   353.3  2247.3   361.52246.141   378.8 2244.45
   382.4 2244.55   387.62246.904   389.7 2247.89   400.6 2246.93   414.4  2247.3
   446.2  2249.8   471.3 2248.59   480.6 2251.29   496.4 2253.29   513.7 2257.01
   544.5 2265.12   567.6 2267.97   596.5 2273.29   606.1 2275.95   697.8 2287.62
#Mann= 5 ,-1 , 0
       0    .035       0   361.5    .045       0   387.6    .035       0
     440     .04       0  472.94    .035       0
#XS Ineff= 2 , 0
                          444.89          2249.8
Permanent Ineff=
       F       F
Bank Sta=361.5,387.6
XS Rating Curve= 0 ,0
Exp/Cntr=0.3,0.1

Type RM Length L Ch R = 1 ,23816   ,235.4,235.6,232.6
XS GIS Cut Line= 2
     2173878.864      219797.516     2174172.267      219191.613
#Sta/Elev= 30
       0 2326.05    44.2 2323.12    81.1 2318.26    95.8 2315.66   127.8 2308.12
   267.7  2265.6   289.2 2259.82   307.4 2256.28   314.4 2253.32   326.7 2246.36
     333 2244.43   344.42242.591   348.8 2240.86   353.7 2240.32     366 2242.91
   369.4 2244.11   376.7 2244.58   424.9 2243.57     450 2244.07   460.5 2244.47
   471.6 2246.65   489.7 2245.83   507.9 2243.35   551.7  2242.8     559 2244.06
   569.7 2247.17   588.1 2254.74   609.1 2260.49   631.2  2265.7   673.2 2273.49
#Mann= 7 ,-1 , 0
       0    .035       0   344.4    .045       0     366    .035       0
     450     .04       0     510     .06       0     560     .04       0
     670    .035       0
#XS Ineff= 2 , 0
                          440.48         2274.57
Permanent Ineff=
       F       F
Bank Sta=344.4,366
XS Rating Curve= 0 ,0
Exp/Cntr=0.3,0.1

Type RM Length L Ch R = 1 ,23580   ,276.2,273.8,270.6
XS GIS Cut Line= 3
     2174085.916      219926.906     2174228.819      219592.098
     2174375.603      219259.011
#Sta/Elev= 30
       0 2329.86    21.4 2324.77      42 2320.82    52.7 2318.06   134.8  2300.4
   196.9 2283.95   263.2 2267.43   284.6 2261.42   308.4 2253.71   320.3 2250.86
   338.4 2241.52   349.12239.574   355.9 2236.92   360.9 2236.42   365.9 2237.04
   373.92239.663   390.8 2240.41   434.8 2240.38   463.5  2243.2   485.3 2243.74
   535.2    2242     571 2241.65   592.5 2239.17   612.2 2239.73   639.1 2242.15
   653.5 2244.59   664.2 2247.81   669.9 2248.91   703.7 2252.75     728 2256.18
#Mann= 5 ,-1 , 0
       0    .035       0   349.1    .045       0   373.9    .035       0
  534.03     .06       0  694.03    .035       0
#XS Ineff= 2 , 0
                          478.18         2275.41
Permanent Ineff=
       F       F
Bank Sta=349.1,373.9
XS Rating Curve= 0 ,0
Exp/Cntr=0.3,0.1

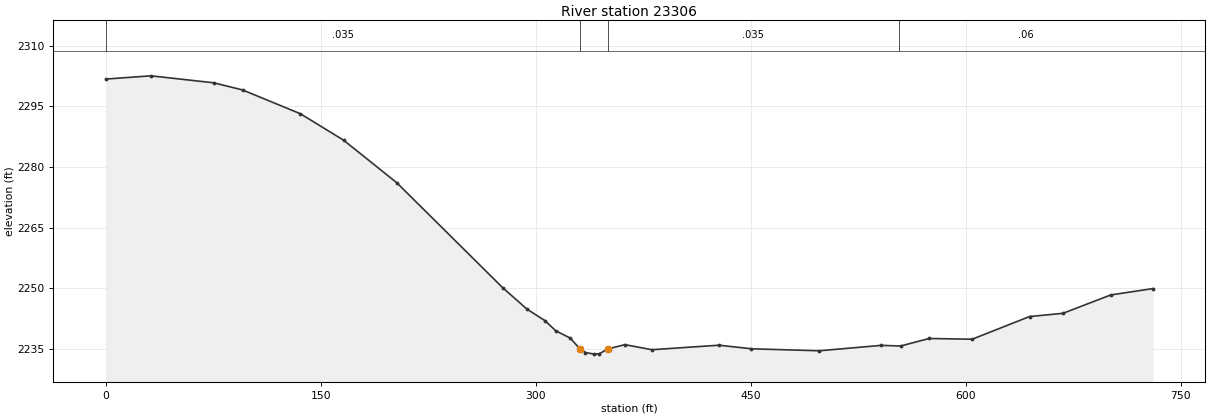
Type RM Length L Ch R = 1 ,23306   ,202.1,200.6,197.8
XS GIS Cut Line= 3
      2174402.05      220027.292     2174481.715      219672.862
     2174547.091      219311.322
#Sta/Elev= 30
       0 2301.79    31.5 2302.59    75.2 2300.87    95.4  2299.1   135.8  2293.2
     166 2286.64     203 2276.14     277 2250.12   293.8 2244.87   306.4 2241.99
     314 2239.47   324.1 2237.66   330.6 2235.09   334.7 2234.09   340.9  2233.7
   344.3 2233.79   350.22234.973   362.2 2236.05     381 2234.79   427.8 2235.91
   450.5 2235.02   497.8 2234.53   541.1 2235.87   554.5 2235.71   574.5 2237.57
   604.5 2237.39   644.5    2243   667.8  2243.8   701.2 2248.35   730.7 2249.93
#Mann= 4 ,-1 , 0
       0    .035       0   330.6    .045       0   350.2    .035       0
  553.27     .06       0
Bank Sta=330.6,350.2
XS Rating Curve= 0 ,0
Exp/Cntr=0.3,0.1