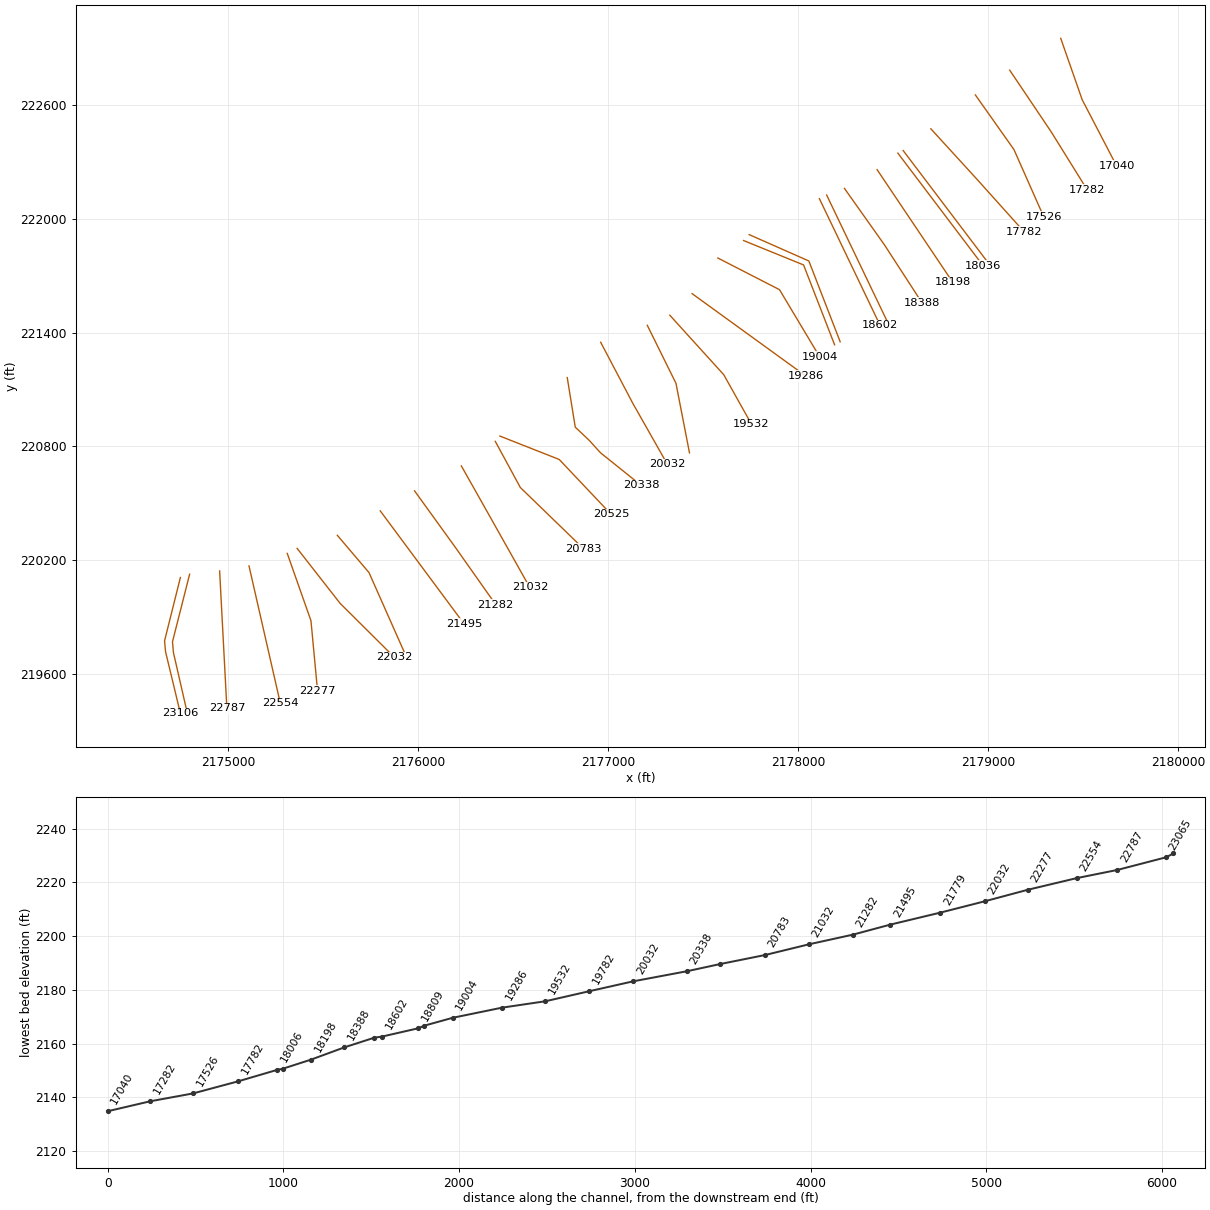
HEC-RAS study SWTSPRNGSCK.prj: SWTSPRNGSCK

--- SWTSPRNGSCK.g01 (geometry) --- (continued)

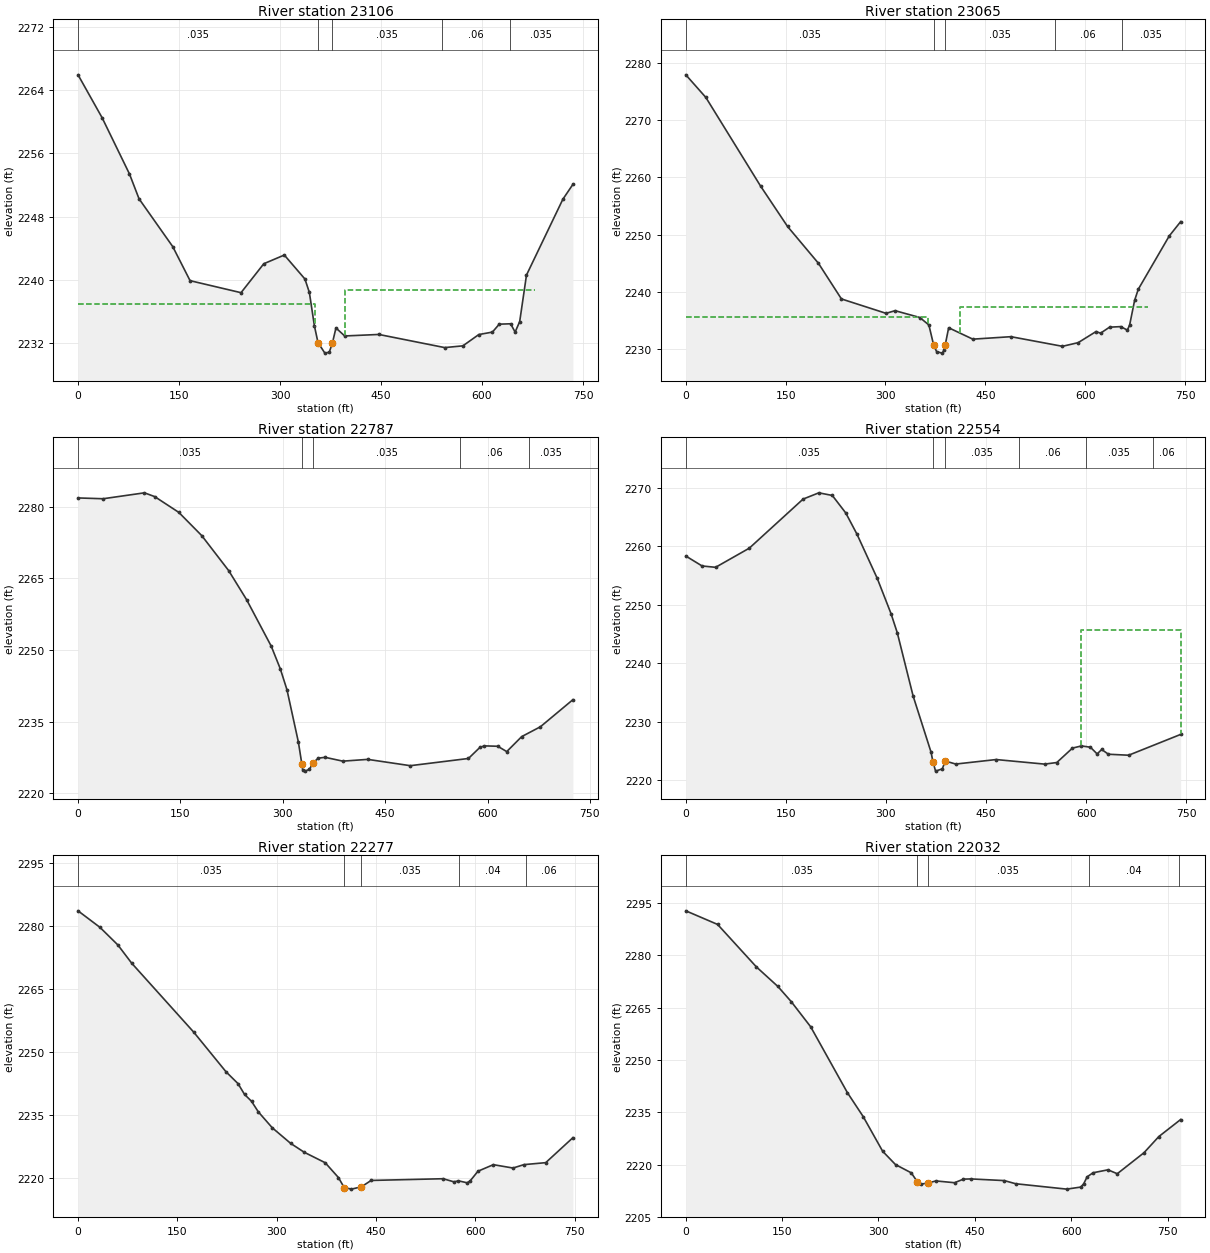
Type RM Length L Ch R = 1 ,23106   ,41.1,41.1,41.1
XS GIS Cut Line= 4
      2174746.92      220110.016     2174663.586      219776.682
     2174668.795      219719.391      2174746.92      219394.738
#Sta/Elev= 30
       0 2265.94    35.8 2260.51    76.4 2253.41    90.6 2250.27   140.7 2244.22
   166.4 2239.92   242.1  2238.4   275.9 2242.06   306.4 2243.16     337 2240.13
   343.6 2238.43   351.1  2234.2   356.42232.103   366.6 2230.76   373.2 2230.88
  377.862232.057   383.1 2233.94   396.1 2232.93   446.8 2233.12   544.6 2231.46
   571.6 2231.68   595.3 2233.11   615.5 2233.42   625.6 2234.42   642.5 2234.47
   649.2 2233.42     656 2234.75   666.1 2240.63   720.1 2250.21     735 2252.09
#Mann= 5 ,-1 , 0
       0    .035       0   356.4    .045       0  377.86    .035       0
  541.12     .06       0  641.12    .035       0
#XS Ineff= 2 ,-1
       0  351.34 2236.95  396.98   678.62238.717
Permanent Ineff=
       F       F
Bank Sta=356.4,377.86
XS Rating Curve= 0 ,0
Exp/Cntr=0.3,0.1

Type RM Length L Ch R = 1 ,23065   ,276.4,277.3,274.9
XS GIS Cut Line= 4
     2174795.531      220127.377     2174705.253      219771.474
     2174710.461      219714.182     2174781.642      219403.418
#Sta/Elev= 30
       0 2277.92    30.1 2273.97   112.3  2258.5   152.8 2251.45   199.3 2245.01
   233.8 2238.79   300.8 2236.28   314.4 2236.74   351.6 2235.55   365.2 2234.24
   372.42230.715   376.8  2229.6     385 2229.33   388.3 2229.85   389.62230.681
   394.9 2233.76   431.2 2231.77   488.5  2232.2   565.9 2230.52   589.5 2231.16
   616.4  2233.1   623.1 2232.81   636.6 2233.86   653.4 2233.96   663.4 2233.35
   666.8 2234.23   674.3 2238.54   679.8 2240.48   726.3 2249.78   743.5 2252.29
#Mann= 5 ,-1 , 0
       0    .035       0   372.4    .045       0   389.6    .035       0
   554.7     .06       0   654.7    .035       0
#XS Ineff= 2 ,-1
       0  363.312235.715  412.07  694.892237.385
Permanent Ineff=
       F       F
Bank Sta=372.4,389.6
XS Rating Curve= 0 ,0
Exp/Cntr=0.3,0.1

Type RM Length L Ch R = 1 ,22787   ,229.7,233.2,234.3
XS GIS Cut Line= 2
     2174953.517      220144.738     2174991.711       219420.78
#Sta/Elev= 30
       0 2281.84    36.7 2281.67    97.3 2282.91   112.3 2282.12   147.6 2278.82
   181.3 2273.94   220.7 2266.62     247 2260.52   283.1 2250.78   296.3 2246.06
   306.1 2241.67   322.8 2230.73     3282226.015   329.1 2224.93   332.4 2224.62
     339 2224.99   344.42226.395   352.1 2227.34     362 2227.51   387.9 2226.71
   424.4 2227.08   486.8 2225.76     572 2227.27   588.7 2229.58   595.2 2229.91
   614.9 2229.83   628.1 2228.71     650 2231.85   677.4 2233.91     725 2239.58
#Mann= 5 ,-1 , 0
       0    .035       0     328    .045       0   344.4    .035       0
     560     .06       0     660    .035       0
Bank Sta=328,344.4
XS Rating Curve= 0 ,0
Exp/Cntr=0.3,0.1

Type RM Length L Ch R = 1 ,22554   ,277.5,277.2,273.3
XS GIS Cut Line= 2
     2175108.101       220171.22     2175273.049      219447.985
#Sta/Elev= 30
       0 2258.34    24.4 2256.64    44.6 2256.41    95.1 2259.68   175.8 2268.08
   199.4 2269.15   219.6  2268.7   239.8  2265.7   256.6 2262.07   286.9 2254.53
   307.6 2248.49   317.1 2245.17   340.7 2234.41   367.6  2224.8  370.492223.106
   374.4 2221.55   384.5 2221.94   388.92223.284   404.6 2222.76   465.2 2223.53
   537.8 2222.75   556.1 2223.02   579.6 2225.49   593.1 2225.86   606.5 2225.64
   616.6 2224.49   623.4 2225.25   633.5 2224.44   663.8 2224.27   741.8 2227.83
#Mann= 6 ,-1 , 0
       0    .035       0  370.49    .045       0   388.9    .035       0
     500     .06       0     600    .035       0     700     .06       0
#XS Ineff= 2 , 0
                          592.18         2245.77
Permanent Ineff=
       F       F
Bank Sta=370.49,388.9
XS Rating Curve= 0 ,0
Exp/Cntr=0.3,0.1

Type RM Length L Ch R = 1 ,22277   ,234.7,244.7,254.7
XS GIS Cut Line= 3
     2175309.601      220236.947      2175434.42      219882.585
     2175469.142      219512.793
#Sta/Elev= 30
       0 2283.58    33.1 2279.64    60.1 2275.45      81  2271.1   174.6 2254.67
   223.4 2245.21   241.5 2242.39   251.4 2239.81   261.9 2238.18   272.2 2235.65
   293.2 2231.86     321 2228.14   341.5 2226.02   373.2 2223.52   393.1    2220
   401.82217.612   412.8 2217.23   427.8 2217.78   442.5  2219.3   551.2 2219.71
   567.7 2218.96   574.3 2219.21   587.5 2218.74     592 2219.19   603.8  2221.5
     627 2223.06   656.7 2222.26   673.2 2223.07   706.1 2223.54   747.1 2229.49
#Mann= 5 ,-1 , 0
       0    .035       0   401.8    .045       0   427.8    .035       0
   575.7     .04       0   675.7     .06       0
Bank Sta=401.8,427.8
XS Rating Curve= 0 ,0
Exp/Cntr=0.3,0.1

Type RM Length L Ch R = 1 ,22032   ,251,253,242.7
XS GIS Cut Line= 3
      2175361.53       220263.59     2175587.744      219974.227
     2175873.667      219689.943
#Sta/Elev= 30
       0 2292.82    49.5 2288.91   109.9 2276.72   143.3 2271.12   164.1 2266.77
   194.4 2259.54   251.5 2240.66   276.2 2233.76   306.5 2223.81   326.5 2219.99
     351 2217.63   360.72214.993   366.3 2214.38   377.12214.717   389.5  2215.3
   418.4 2214.79   432.3 2215.82   443.9 2215.88   495.9  2215.4   513.5  2214.5
   593.1 2212.95   614.9 2213.54   619.5 2214.48   624.8 2216.47   634.1 2217.65
   657.3 2218.49   671.8 2217.37   713.4  2223.4   736.5 2228.04   770.5 2232.93
#Mann= 5 ,-1 , 0
       0    .035       0   360.7    .045       0   377.1    .035       0
  627.29     .04       0  767.29     .05       0
Bank Sta=360.7,377.1
XS Rating Curve= 0 ,0
Exp/Cntr=0.3,0.1

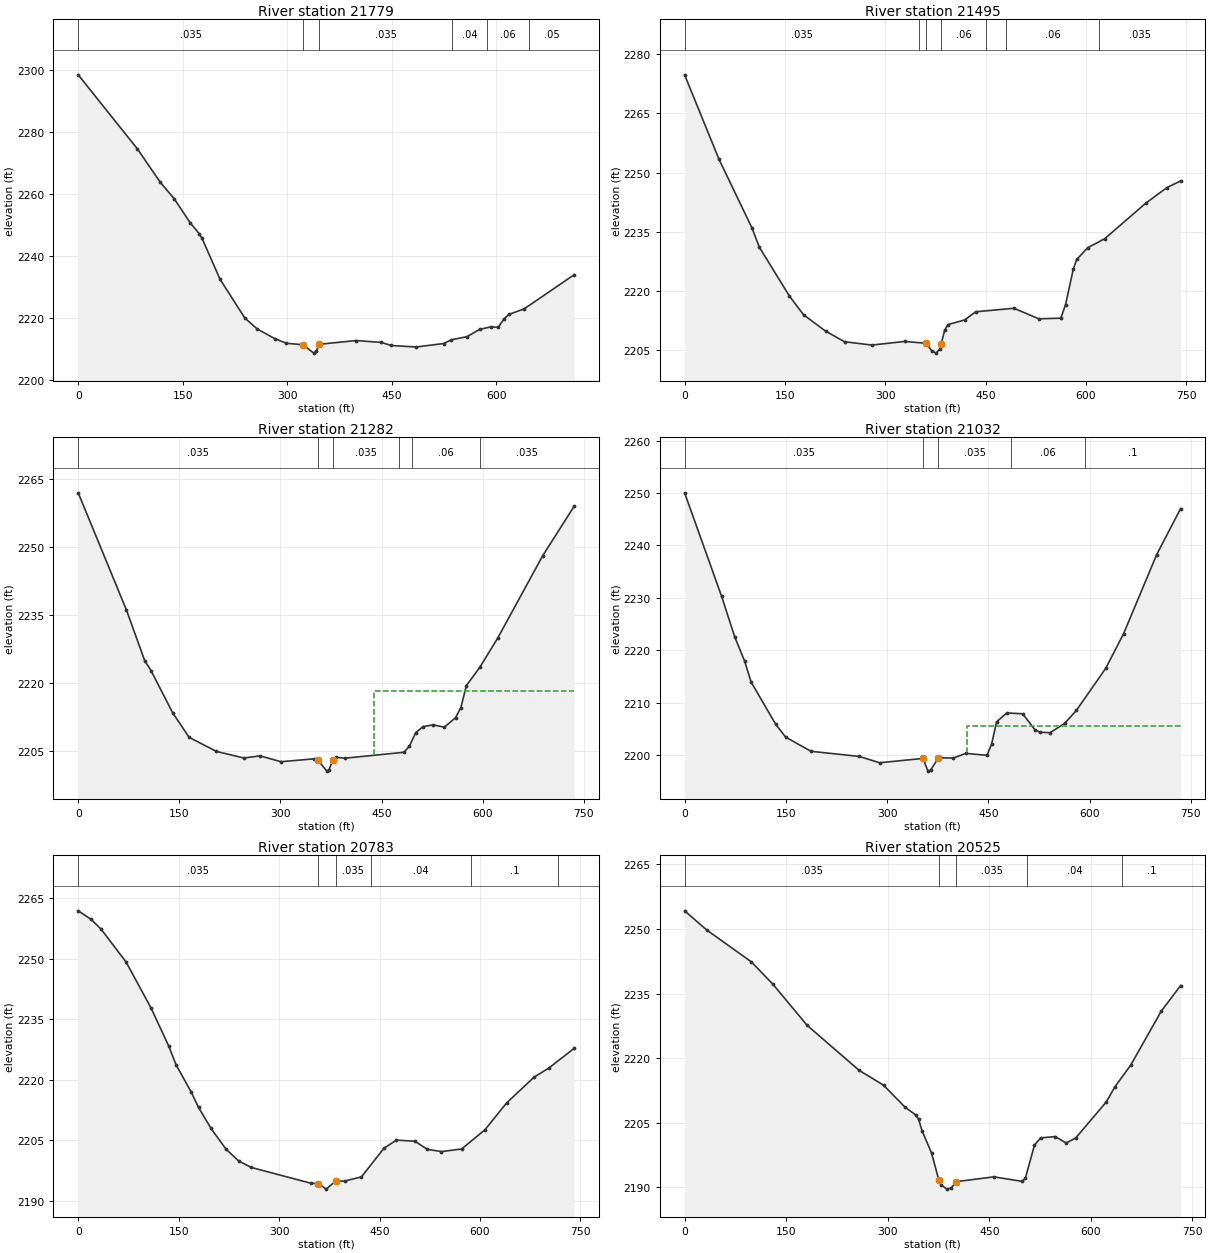
Type RM Length L Ch R = 1 ,21779   ,279,284.4,284.9
XS GIS Cut Line= 3
     2175573.309      220332.238     2175739.975      220136.057
      2175924.35      219720.359
#Sta/Elev= 30
       0 2298.47      85 2274.58   117.6  2263.9   137.9 2258.49   160.7 2250.79
   173.5  2247.3   177.9  2245.7   203.7 2232.53   239.2 2220.06   257.3 2216.48
   282.1 2213.43   298.8 2211.92   322.82211.417   338.3 2208.73   341.9  2209.3
   345.82211.582     399 2212.78   435.2 2212.19   449.5 2211.19   485.4 2210.71
   524.9 2211.83   535.8 2213.04   558.1 2214.03   576.3 2216.37   592.9 2217.23
   602.9 2217.02     611 2219.62   618.2 2221.21   640.2 2222.98   712.2 2234.02
#Mann= 6 ,-1 , 0
       0    .035       0   322.8    .045       0   345.8    .035       0
  537.42     .04       0  587.42     .06       0  647.42     .05       0
Bank Sta=322.8,345.8
XS Rating Curve= 0 ,0
Exp/Cntr=0.3,0.1

Type RM Length L Ch R = 1 ,21495   ,211.8,212.6,211.7
XS GIS Cut Line= 2
     2175799.361      220460.843     2176241.271      219865.231
#Sta/Elev= 30
       0 2274.74    51.2 2253.43   100.8 2235.93   111.8 2231.07   156.7 2218.72
   177.8 2213.98   210.9 2209.83   239.1 2207.16   279.9 2206.31     329 2207.23
  361.37 2206.76   369.8 2204.79   376.1 2204.27   381.6 2205.33  383.572206.622
   388.9 2210.09   393.6 2211.49   418.8 2212.68   435.2 2214.74   492.4 2215.63
   529.6 2212.96   562.5 2213.12   569.5 2216.52   581.2 2225.58   586.3 2227.99
   602.7 2230.96   628.1 2233.24   689.1 2242.18   721.1 2246.19   741.6 2247.87
#Mann= 7 ,-1 , 0
       0    .035       0     350     .06       0  361.37    .045       0
  383.57     .06       0     450    .035       0     480     .06       0
     620    .035       0
Bank Sta=361.37,383.57
XS Rating Curve= 0 ,0
Exp/Cntr=0.3,0.1

Type RM Length L Ch R = 1 ,21282   ,249.5,250,245.7
XS GIS Cut Line= 3
     2175979.841      220566.361     2176193.848      220269.959
     2176407.231      219967.465
#Sta/Elev= 30
       0 2261.95    71.6 2236.07    98.7 2224.89   108.1  2222.7   140.4 2213.33
   164.6 2207.99   205.1 2204.89   245.6 2203.44   269.9 2203.91   300.7 2202.62
   349.1 2203.24   355.82202.903   368.9 2200.54   371.7 2200.73  377.722202.987
     383 2203.61   395.1 2203.39   483.4  2204.7   491.4 2206.08   500.7 2209.04
   511.5 2210.35   526.6 2210.76   543.1 2210.23   559.7 2212.33   567.7 2214.58
   575.7 2219.37   595.8 2223.47   622.1 2229.84   689.1 2248.08   735.8 2259.01
#Mann= 6 ,-1 , 0
       0    .035       0   355.8    .045       0  377.72    .035       0
  475.59     .04       0  495.59     .06       0  595.59    .035       0
#XS Ineff= 2 , 0
                          438.84          2218.3
Permanent Ineff=
       F       F
Bank Sta=355.8,377.72
XS Rating Curve= 0 ,0
Exp/Cntr=0.3,0.1

Type RM Length L Ch R = 1 ,21032   ,245.2,249.4,254.7
XS GIS Cut Line= 3
      2176226.27      220697.723     2176404.505       220381.55
     2176586.754      220057.555
#Sta/Elev= 30
       0 2250.04    54.7 2230.33    74.4  2222.5    88.9 2217.94    98.5 2213.94
   134.8 2205.91   149.6 2203.44   187.3 2200.73   258.8 2199.75   288.8 2198.55
   353.1 2199.37   360.5 2196.95   364.3 2197.14     3762199.487   398.2 2199.45
   416.5 2200.34   447.8 2199.96   454.6 2202.06   462.2 2206.36   477.2 2208.05
   500.8 2207.89   518.6 2204.88   526.2 2204.37   541.2 2204.28   562.8 2206.04
   580.3 2208.53   623.7 2216.55   650.2 2223.16   699.3 2238.27   734.7 2247.03
#Mann= 5 ,-1 , 0
       0    .035       0   353.1    .045       0     376    .035       0
  482.95     .06       0  592.95      .1       0
#XS Ineff= 2 , 0
                           417.8         2205.57
Permanent Ineff=
       F       F
Bank Sta=353.1,376
XS Rating Curve= 0 ,0
Exp/Cntr=0.3,0.1

Type RM Length L Ch R = 1 ,20783   ,256.3,257.8,253.5
XS GIS Cut Line= 3
     2176404.906       220827.03      2176536.85      220583.974
     2176870.184      220261.057
#Sta/Elev= 30
       0 2261.81    19.2 2259.71    34.1 2257.29    71.4 2249.17   108.8 2237.76
   135.2 2228.35   146.1 2223.73   168.5 2217.07   179.7 2213.17   198.4 2207.97
   220.8 2202.84   239.4 2199.98   258.1 2198.35   347.4 2194.43   358.52194.356
   370.3 2192.97   384.42194.953   397.7 2194.96     423    2196   456.5 2203.07
   475.3  2205.1   502.8 2204.81   521.5 2202.81   542.4 2202.26   572.6  2202.9
   607.4 2207.65   639.8 2214.31   680.9 2220.68   702.5 2222.89   740.7  2227.8
#Mann= 6 ,-1 , 0
       0    .035       0   358.5    .045       0   384.4    .035       0
  436.56     .04       0  586.56      .1       0  716.56     .06       0
Bank Sta=358.5,384.4
XS Rating Curve= 0 ,0
Exp/Cntr=0.3,0.1

Type RM Length L Ch R = 1 ,20525   ,185.2,187.1,185.3
XS GIS Cut Line= 3
     2176429.211      220854.807     2176741.711      220731.543
     2177014.281      220443.349
#Sta/Elev= 30
       0 2254.22    32.9 2249.74    98.5 2242.38   130.6 2237.14     181 2227.62
   257.8 2217.16   293.9 2213.72   325.6 2208.61   341.1 2206.84   345.5 2205.87
   350.6 2203.18   364.9 2197.89   375.32191.768   379.3 2190.55   387.2 2189.58
   393.6 2189.85   401.52191.325   456.9 2192.43   498.6 2191.38   503.2 2192.08
   516.7 2199.77   525.7 2201.48   547.4 2201.78   563.6  2200.3   577.6 2201.45
   622.8 2209.83   635.6 2213.36   658.8 2218.36   703.9 2230.89   732.6 2236.87
#Mann= 5 ,-1 , 0
       0    .035       0   375.3    .045       0   401.5    .035       0
  505.93     .04       0  645.93      .1       0
Bank Sta=375.3,401.5
XS Rating Curve= 0 ,0
Exp/Cntr=0.3,0.1

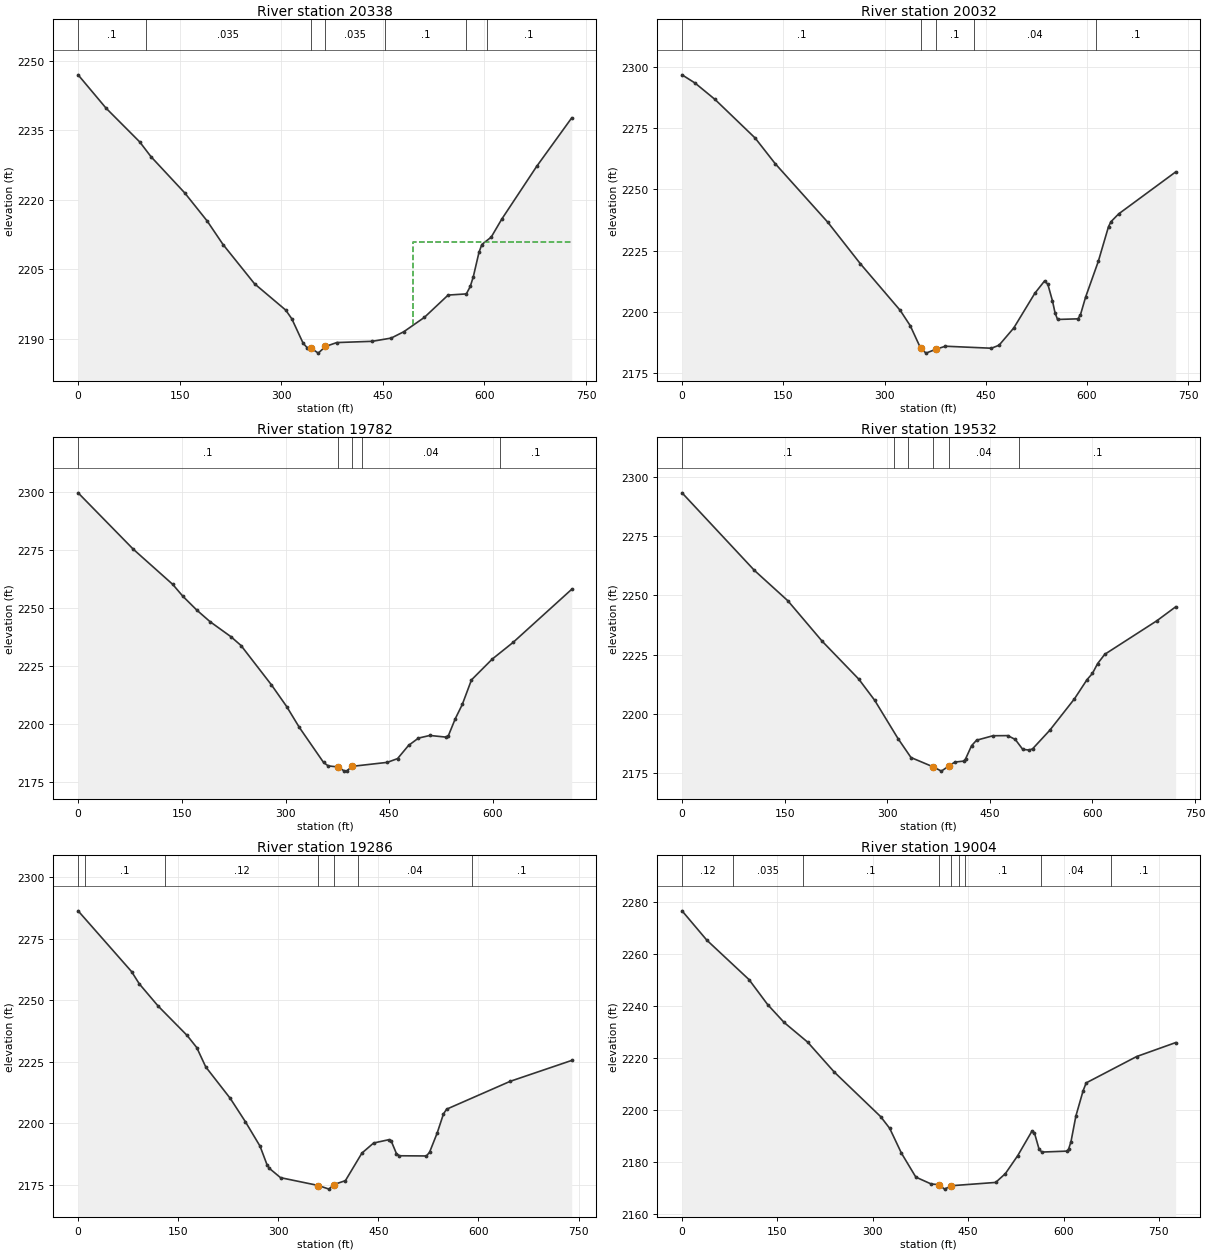
Type RM Length L Ch R = 1 ,20338   ,309.1,305.6,299.4
XS GIS Cut Line= 5
 2176783.9063114221162.5189090592176826.00258417220901.638000542
2176898.62237493220833.236485506 2176958.6050312220767.153898085
     2177173.537      220594.687
#Sta/Elev= 30
       0 2246.99    41.2 2239.81      91 2232.51   107.6 2229.33   157.5  2221.5
   190.7 2215.42     214 2210.37   260.5  2201.9   306.6 2196.21   315.6 2194.32
   332.2 2189.08   338.1 2188.12  343.78 2188.02   354.6 2186.93  365.242188.364
   381.9 2189.21   434.3 2189.48   462.3 2190.18   480.9 2191.55   511.3 2194.65
   546.3 2199.46   573.2 2199.71     579 2201.31   583.5 2203.42   591.9 2208.69
   596.1 2210.37   609.9 2211.96   625.6 2215.87     677 2227.22   728.8  2237.7
#Mann= 7 ,-1 , 0
       0      .1       0     100    .035       0  343.78    .045       0
  365.24    .035       0  453.26      .1       0  573.26     .04       0
  603.26      .1       0
#XS Ineff= 2 , 0
                          494.33         2210.98
Permanent Ineff=
       F       F
Bank Sta=343.78,365.24
XS Rating Curve= 0 ,0
Exp/Cntr=0.3,0.1

Type RM Length L Ch R = 1 ,20032   ,253.8,250,243.8
XS GIS Cut Line= 3
     2176959.772       221348.89     2177128.911      221027.402
     2177310.485      220707.201
#Sta/Elev= 30
       0 2296.81    19.3 2293.45    48.9 2286.75   108.3 2271.01   137.9 2260.59
   215.8 2236.68   264.3 2219.65   323.3 2200.62   338.1  2194.4   353.42185.261
   361.5 2183.18   376.32184.778   390.3    2186   458.4 2185.18   469.7  2186.4
   491.5 2193.44   522.8 2207.64   537.2 2212.67     542  2211.3   548.9 2204.48
   552.6 2199.73   556.4 2196.93   586.6 2197.18   590.4 2198.89   597.9    2206
   616.8 2220.66   631.9 2234.82   635.6 2236.86   646.9 2240.02   731.4 2257.16
#Mann= 5 ,-1 , 0
       0      .1       0   353.4    .045       0   376.3      .1       0
  433.27     .04       0  613.27      .1       0
Bank Sta=353.4,376.3
XS Rating Curve= 0 ,0
Exp/Cntr=0.3,0.1

Type RM Length L Ch R = 1 ,19782   ,243,250.7,259.6
XS GIS Cut Line= 3
     2177205.253      221438.141     2177356.295      221132.585
     2177427.475      220766.266
#Sta/Elev= 30
       0 2299.73    79.9 2275.35   136.9 2260.17   151.5 2255.06   171.9 2249.01
   190.9 2244.06   221.1 2237.57   235.7 2233.76   279.7 2216.75   301.7  2207.4
   319.9 2198.44   355.1 2183.23   361.8 2181.76   376.32181.292   385.2  2179.5
   388.5 2179.58   396.52181.568   447.3 2183.29   462.1 2184.91     478 2190.61
   492.3 2193.77   508.8 2194.91   532.3 2194.19   535.6 2194.82   545.6 2202.16
   555.7 2208.29     569 2218.92   599.1 2227.92   629.2 2235.11     714 2258.06
#Mann= 5 ,-1 , 0
       0      .1       0   376.3    .045       0   396.5      .1       0
  410.85     .04       0  610.85      .1       0
Bank Sta=376.3,396.5
XS Rating Curve= 0 ,0
Exp/Cntr=0.3,0.1

Type RM Length L Ch R = 1 ,19532   ,242.2,245.8,248.4
XS GIS Cut Line= 3
     2177323.765      221491.172     2177608.031      221177.724
     2177753.864      220917.307
#Sta/Elev= 30
       0 2293.39   105.8  2260.6   154.7 2247.76   204.9 2230.65   258.4 2214.63
   281.6  2205.7   315.8 2189.48   334.7  2181.5   367.42177.517   379.1 2175.75
   390.4    2178   398.8 2179.58   411.7 2179.99   414.4 2180.87   423.2 2186.48
   430.5 2188.81   454.6 2190.71   476.3 2190.76   487.2 2189.12     498 2184.97
   507.6 2184.64   512.5 2185.19   537.5    2193   573.7 2206.33     592 2214.41
     600 2217.07   607.5 2221.21     618 2225.14     694 2239.29   721.6  2245.2
#Mann= 6 ,-1 , 0
       0      .1       0     310     .12       0     330     .04       0
   367.4    .045       0   390.4     .04       0  493.15      .1       0
Bank Sta=367.4,390.4
XS Rating Curve= 0 ,0
Exp/Cntr=0.3,0.1

Type RM Length L Ch R = 1 ,19286   ,286.4,281.6,274.4
XS GIS Cut Line= 2
     2177441.147      221604.783     2178040.322       221170.78
#Sta/Elev= 30
       0 2286.24    80.1 2261.61    91.8  2256.6     120 2247.61   163.3 2235.73
   177.8  2230.8   191.3 2222.95   228.1 2210.16   250.7 2200.73   272.7 2190.79
   283.1 2183.31   286.8 2181.77   303.4 2178.03   360.1 2174.85   376.1 2173.38
     3832175.207   400.6 2176.81   425.4 2188.01   442.9 2192.08   465.4 2193.41
   469.5 2192.74   477.1  2187.8   481.6 2186.91   522.1 2186.83   526.8 2188.37
   538.2 2196.16   547.6 2203.89   552.3  2205.8   647.7 2217.11   739.8 2225.57
#Mann= 7 ,-1 , 0
       0     .12       0      10      .1       0     130     .12       0
   360.1    .045       0     383      .1       0     420     .04       0
     590      .1       0
Bank Sta=360.1,383
XS Rating Curve= 0 ,0
Exp/Cntr=0.3,0.1

Type RM Length L Ch R = 1 ,19004   ,164,161.6,158.9
XS GIS Cut Line= 3
     2177576.781      221792.307     2177901.434      221625.641
     2178112.572      221272.563
#Sta/Elev= 30
       0 2276.45    38.9 2265.21   105.3 2250.06   134.8 2240.41   160.6 2233.58
   197.5 2226.05   239.6  2214.5   312.2 2197.48   326.6 2192.93     345 2183.43
   367.7 2174.21   391.6  2171.6     4042171.286   412.9  2169.6   423.72170.908
   493.2 2172.17   508.5 2175.55     528 2182.49   550.5 2191.95   554.3 2191.13
   561.4 2185.02   565.8 2183.83   605.2 2184.19   607.9 2184.93   611.7 2187.83
   619.4 2197.68   630.8 2207.41   635.6 2210.39   714.9  2220.5   776.3 2225.86
#Mann= 9 ,-1 , 0
       0     .12       0      80    .035       0     190      .1       0
     404    .045       0   423.7      .1       0  434.93    .035       0
  444.93      .1       0  564.93     .04       0  674.93      .1       0
Bank Sta=404,423.7
XS Rating Curve= 0 ,0
Exp/Cntr=0.3,0.1

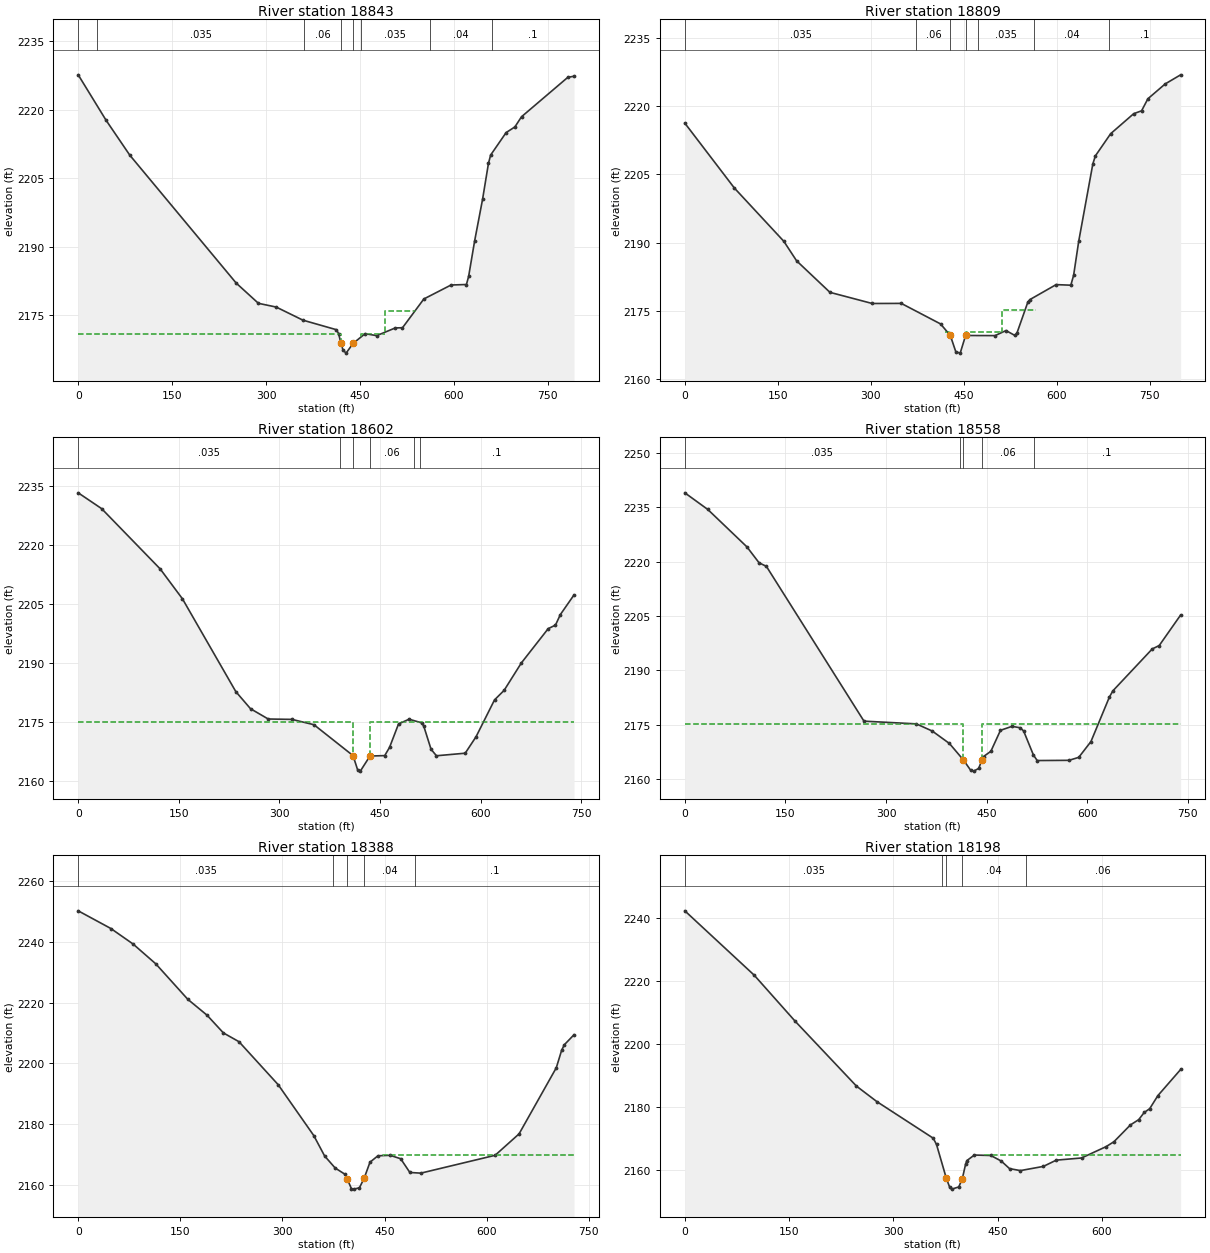
Type RM Length L Ch R = 1 ,18843   ,33.5,33.5,33.6
XS GIS Cut Line= 3
     2177712.197      221884.321      2178028.17      221755.849
     2178191.364       221335.71
#Sta/Elev= 30
       0 2227.63    44.5 2217.68    82.4 2210.03   252.4    2182   287.8 2177.58
   316.2 2176.76   358.9 2173.89   412.3  2171.8   415.9 2170.93   419.52168.857
   422.9 2167.34   427.8 2166.67   439.12168.807   458.2 2170.93   476.7  2170.5
   506.4 2172.19   517.9 2172.23     552 2178.53   595.4 2181.59     620  2181.7
   623.5 2183.46   633.1 2191.24   645.8 2200.38   655.2 2208.25   658.7 2210.06
   683.4 2214.98   697.4 2216.22     708 2218.45   781.9 2227.08   791.8 2227.32
#Mann= 8 ,-1 , 0
       0      .1       0      30    .035       0  361.09     .06       0
   419.5    .045       0   439.1     .06       0  451.09    .035       0
  561.09     .04       0  661.09      .1       0
#XS Ineff= 3 ,-1
       0  419.36 2170.85  452.04     4902170.849  490.24  539.97 2175.95
Permanent Ineff=
       F       F       F
Bank Sta=419.5,439.1
XS Rating Curve= 0 ,0
Exp/Cntr=0.3,0.1

Type RM Length L Ch R = 1 ,18809   ,206.6,206.9,209.2
XS GIS Cut Line= 3
     2177741.711      221915.571     2178055.947      221776.682
     2178220.878      221351.335
#Sta/Elev= 30
       0 2216.26    79.9    2202   159.7 2190.29   180.3    2186   234.1 2179.07
   302.3 2176.62   349.2 2176.64   412.5 2172.13   428.3 2169.59   437.1 2166.02
   444.2 2165.71  452.942169.585   500.5 2169.56   518.1 2170.67   532.1 2169.62
   535.7  2170.1   553.3 2176.91   556.8 2177.49     599 2180.77   622.7 2180.64
   627.2 2182.83   635.4 2190.29   658.2 2207.31   662.3 2209.07     687 2213.95
   724.1 2218.34   736.8 2218.97     747 2221.62   774.9 2224.88   799.8 2226.88
#Mann= 7 ,-1 , 0
       0    .035       0  373.56     .06       0   428.3    .045       0
  452.94     .06       0  473.56    .035       0  563.56     .04       0
  683.56      .1       0
#XS Ineff= 3 ,-1
  419.23  426.49 2170.42  454.36  509.09 2170.33  511.12  566.01 2175.26
Permanent Ineff=
       F       F       F
Bank Sta=428.3,452.94
XS Rating Curve= 0 ,0
Exp/Cntr=0.3,0.1

Type RM Length L Ch R = 1 ,18602   ,43.1,44,43.4
XS GIS Cut Line= 2
     2178111.503      222104.807     2178430.947      221438.141
#Sta/Elev= 30
       0 2233.25    34.9 2229.24   122.3 2213.92   155.4 2206.35     235 2182.79
   256.9 2178.45   283.3 2175.84   318.7 2175.74   351.5 2174.39   409.82166.541
   416.9 2162.77   420.6 2162.61     4352166.439     457 2166.55   464.2 2168.64
   477.6 2174.59   493.3 2175.79     512 2174.87   515.2 2174.03   526.1 2168.15
   534.1 2166.51     577 2167.16   593.2 2171.35   620.7 2180.69     635 2183.11
   660.7 2190.07   700.7 2198.77   711.6 2199.68   718.9 2202.36   739.2 2207.33
#Mann= 6 ,-1 , 0
       0    .035       0     390     .06       0   409.8    .045       0
     435     .06       0     500     .04       0     510      .1       0
#XS Ineff= 2 , 0
           409.8  2175.1     435          2175.1
Permanent Ineff=
       F       F
Bank Sta=409.8,435
XS Rating Curve= 0 ,0
Exp/Cntr=0.3,0.1

Type RM Length L Ch R = 1 ,18558   ,167.8,170.3,172.4
XS GIS Cut Line= 2
     2178149.697      222123.905     2178469.142      221457.238
#Sta/Elev= 30
       0    2239    34.3  2234.4    92.5  2224.1   110.7 2219.69   121.6 2218.71
   267.1 2175.99   345.2 2175.24     369 2173.25   394.5 2169.83   415.42165.273
   426.4 2162.38   430.8  2162.2   438.1 2162.95  443.282165.396   445.4 2166.23
   456.3 2167.68   470.6 2173.46   487.8 2174.56     500 2174.17   505.1 2173.29
   519.8 2166.62   525.4 2165.12   572.7 2165.18   587.3    2166   605.5 2170.36
     633 2182.64   638.2 2184.36   696.9 2195.92   707.3 2196.86   739.2 2205.28
#Mann= 5 ,-1 , 0
       0    .035       0     410     .06       0   415.4    .045       0
  443.28     .06       0     520      .1       0
#XS Ineff= 2 , 0
           415.4  2175.1  443.28          2175.1
Permanent Ineff=
       F       F
Bank Sta=415.4,443.28
XS Rating Curve= 0 ,0
Exp/Cntr=0.3,0.1

Type RM Length L Ch R = 1 ,18388   ,189.6,189.9,190.2
XS GIS Cut Line= 3
     2178243.442      222158.697     2178454.132      221861.412
     2178652.181      221556.086
#Sta/Elev= 30
       0 2250.18      48 2244.36    80.6 2239.26   113.9 2232.75     161 2221.06
   189.2 2215.85   213.3    2210   236.2 2207.11   293.7 2192.98     346 2176.24
     362  2169.5   377.5 2165.54   391.8  2163.5  394.872162.086   401.3 2158.78
   405.1  2158.6   413.1 2159.05   420.1 2162.21   428.6 2167.46   440.3 2169.57
   458.2 2169.73   473.7  2168.6   487.2 2164.08   503.3 2163.86   612.4 2169.73
   647.6 2176.78   702.3 2198.54   710.1 2204.26   714.1 2206.11   728.3  2209.4
#Mann= 5 ,-1 , 0
       0    .035       0  374.37     .04       0  394.87    .045       0
   420.1     .04       0  494.37      .1       0
#XS Ineff= 2 , 0
                          447.92         2169.69
Permanent Ineff=
       F       F
Bank Sta=394.87,420.1
XS Rating Curve= 0 ,0
Exp/Cntr=0.3,0.1

Type RM Length L Ch R = 1 ,18198   ,160.8,161.7,162.7
XS GIS Cut Line= 2
     2178415.322      222257.585     2178812.892      221665.571
#Sta/Elev= 30
       0 2242.21    99.8 2221.82   158.7 2207.23   246.9 2186.67   276.3 2181.75
   357.3 2170.17     362 2168.18   376.2 2157.41     381 2154.61     384 2154.04
     394 2154.73   399.12157.345   403.8 2161.91   405.8  2163.1   416.4 2164.84
   440.1  2164.7   455.2 2162.92     467 2160.54   482.6 2159.91   515.7 2161.24
   534.2 2163.22   570.6 2163.91   605.9  2167.5   617.2 2169.06   640.9 2174.38
   652.8 2176.05   660.7 2178.32   668.6 2179.52   680.4 2183.67   713.1 2191.94
#Mann= 5 ,-1 , 0
       0    .035       0     370     .04       0   376.2    .045       0
   399.1     .04       0     490     .06       0
#XS Ineff= 2 , 0
                          429.76         2164.95
Permanent Ineff=
       F       F
Bank Sta=376.2,399.1
XS Rating Curve= 0 ,0
Exp/Cntr=0.3,0.1

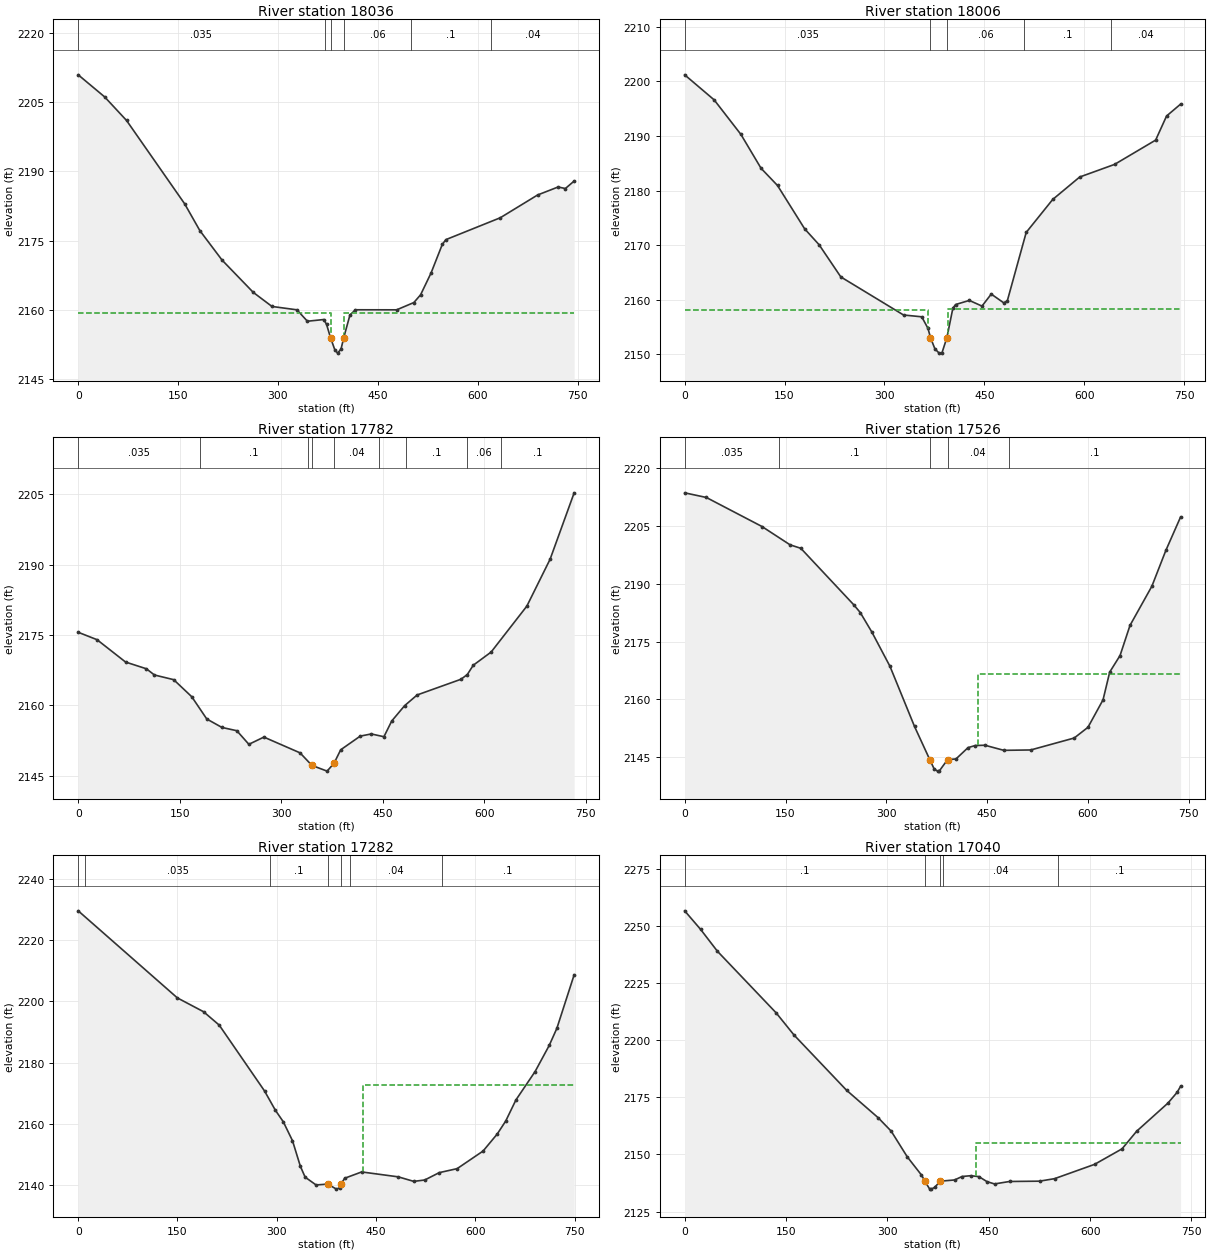
Type RM Length L Ch R = 1 ,18036   ,30.8,30.6,30.5
XS GIS Cut Line= 2
     2178524.697      222344.391      2178974.35      221750.641
#Sta/Elev= 30
       0 2210.92    39.6 2206.15    72.6 2201.03   159.8 2182.99   182.7 2177.17
     216 2170.79   262.9 2163.79     291 2160.74   328.5 2160.01   344.2 2157.54
   368.9 2157.91     373 2156.84   378.9 2153.98   385.3 2151.38   389.5 2150.63
   394.7 2151.51   398.82153.997   408.1 2158.89   416.4 2160.02   478.3 2160.01
   504.1 2161.59   514.2 2163.27   529.9 2167.99   546.8 2174.19   552.2 2175.22
   633.8 2179.95   689.9 2184.89   720.7 2186.62   731.6 2186.29   744.8 2187.91
#Mann= 6 ,-1 , 0
       0    .035       0     370     .06       0   378.9    .045       0
   398.8     .06       0     500      .1       0     620     .04       0
#XS Ineff= 2 , 0
           378.9  2159.3   398.8          2159.3
Permanent Ineff=
       F       F
Bank Sta=378.9,398.8
XS Rating Curve= 0 ,0
Exp/Cntr=0.3,0.1

Type RM Length L Ch R = 1 ,18006   ,221.2,223.3,224.1
XS GIS Cut Line= 2
     2178552.475       222358.28     2179002.128       221764.53
#Sta/Elev= 30
       0 2201.18    44.3 2196.59    84.4 2190.28   114.7 2184.07   139.4 2180.92
   180.2 2172.98   201.9 2170.07   234.5 2164.18   328.7 2157.21     356 2156.88
   365.4 2154.76   369.12153.089   375.8 2151.01   382.2 2150.23   386.3 2150.25
   393.82153.067   402.8 2158.47   406.9 2159.13   427.5 2159.88   446.5 2158.84
   460.4 2161.04   479.1 2159.44   484.5 2159.79   512.9 2172.33   552.7 2178.36
   593.2 2182.47   645.6 2184.78   707.3 2189.23   723.7 2193.64   744.8 2195.82
#Mann= 5 ,-1 , 0
       0    .035       0   369.1    .045       0   393.8     .06       0
     510      .1       0     640     .04       0
#XS Ineff= 2 , 0
          365.52 2158.14  394.82         2158.29
Permanent Ineff=
       F       F
Bank Sta=369.1,393.8
XS Rating Curve= 0 ,0
Exp/Cntr=0.3,0.1

Type RM Length L Ch R = 1 ,17782   ,259.7,256.5,247.3
XS GIS Cut Line= 3
     2178698.243      222472.712     2178944.507      222203.309
     2179190.235      221929.485
#Sta/Elev= 30
       0 2175.56    27.8 2173.98      70 2169.21   100.8 2167.77   112.6 2166.45
   141.1 2165.45   167.8 2161.81     190 2157.06   212.4 2155.26   234.4 2154.56
   252.2 2151.66   274.4  2153.2   327.8 2149.84   345.42147.157   367.8 2145.94
     3782147.607   387.9 2150.49   416.8 2153.41   433.1 2153.87   451.8 2153.28
   463.3 2156.63   482.4 2159.91   500.9 2162.19   565.5 2165.53     575 2166.54
   583.8 2168.53   610.2 2171.34     663 2181.14   697.4 2191.16   732.9 2205.31
#Mann= 9 ,-1 , 0
       0    .035       0     180      .1       0     340     .04       0
   345.4    .045       0     378     .04       0     445     .06       0
     485      .1       0     575     .06       0     625      .1       0
Bank Sta=345.4,378
XS Rating Curve= 0 ,0
Exp/Cntr=0.3,0.1

Type RM Length L Ch R = 1 ,17526   ,238.8,243.5,245.3
XS GIS Cut Line= 3
     2178932.788      222650.808     2179135.809      222363.488
      2179292.11      222010.579
#Sta/Elev= 30
       0 2213.48    32.2 2212.28     115 2204.76   156.8 2200.02   172.8 2199.12
   251.5 2184.51   261.2  2182.5   278.4 2177.46   305.4 2168.58   341.9 2153.02
   364.92144.322   371.2    2142   376.2 2141.45   378.7 2141.47   391.1 2144.43
   403.6  2144.6   421.6 2147.54   432.4 2148.08   446.7 2148.15   474.8 2146.83
   514.9 2146.93   579.5 2150.02     600  2152.8   622.4 2159.91   632.3 2167.08
   647.7 2171.37   662.5 2179.17     695 2189.29   715.8 2198.56   737.8 2207.25
#Mann= 5 ,-1 , 0
       0    .035       0     140      .1       0   364.9    .045       0
   391.1     .04       0  481.81      .1       0
#XS Ineff= 2 , 0
                          436.82         2166.63
Permanent Ineff=
       F       F
Bank Sta=364.9,391.1
XS Rating Curve= 0 ,0
Exp/Cntr=0.3,0.1

Type RM Length L Ch R = 1 ,17282   ,241,241.9,237.3
XS GIS Cut Line= 3
     2179113.386      222781.585     2179331.196      222457.816
     2179520.881      222152.778
#Sta/Elev= 30
       0 2229.69   149.8 2201.17   189.4 2196.64   213.1 2192.25   281.5  2170.7
     298 2164.34   309.9 2160.59   323.8 2154.39   335.7 2146.01   342.9 2142.45
   359.4  2139.9   377.12140.169   390.2 2138.53   394.9 2138.95   397.7 2140.37
   402.6 2142.09   428.3 2144.16   483.7 2142.55     507 2141.07   523.6 2141.52
   545.5 2143.93   572.6 2145.24   611.8 2151.01   633.2 2156.59     646 2160.84
   661.4 2167.74   690.4 2177.05   711.7 2185.59   723.3 2191.21   749.4 2208.74
#Mann= 7 ,-1 , 0
       0      .1       0      10    .035       0     290      .1       0
   377.1    .045       0   397.7      .1       0  410.21     .04       0
  550.21      .1       0
#XS Ineff= 2 , 0
                          430.87         2172.61
Permanent Ineff=
       F       F
Bank Sta=377.1,397.7
XS Rating Curve= 0 ,0
Exp/Cntr=0.3,0.1

Type RM Length L Ch R = 1 ,17040   ,181.5,185.2,190.4
XS GIS Cut Line= 3
     2179382.166      222949.024     2179495.184      222625.641
     2179675.906      222278.502
#Sta/Elev= 30
       0 2256.51    23.7 2248.35    48.4 2238.85   135.3 2211.92   161.7 2202.25
   239.5 2178.08   286.4 2166.03   305.6 2160.18   329.4 2148.94   350.3 2141.04
   355.72138.218   362.4 2134.91   364.9 2134.83   369.8 2135.59   378.42138.302
   399.4 2138.84   410.5 2140.35   423.3  2140.7   435.4  2140.3   447.4  2138.1
   458.5  2137.1   480.7 2138.17   525.1 2138.31   547.3  2139.4   606.5 2145.65
   647.2 2152.44   668.9 2160.16   715.2 2172.46   728.6 2177.11   733.9 2179.81
#Mann= 5 ,-1 , 0
       0      .1       0   355.7    .045       0   378.4      .1       0
  382.56     .04       0  552.56      .1       0
#XS Ineff= 2 , 0
                          431.32            2155
Permanent Ineff=
       F       F
Bank Sta=355.7,378.4
XS Rating Curve= 0 ,0
Exp/Cntr=0.3,0.1