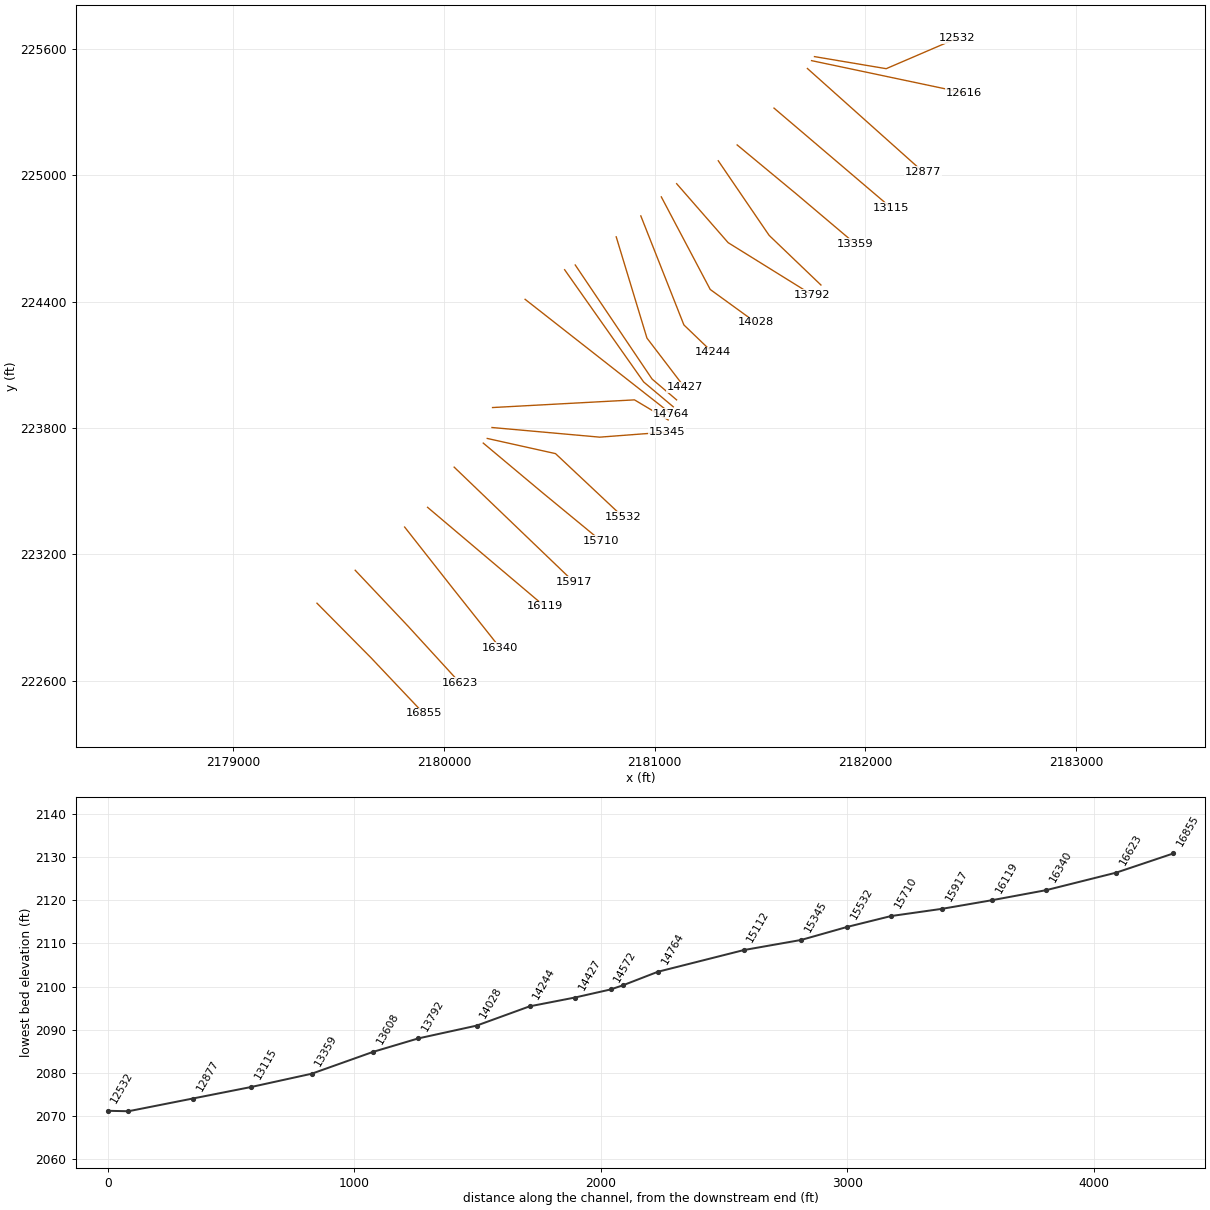
HEC-RAS study SWTSPRNGSCK.prj: SWTSPRNGSCK

--- SWTSPRNGSCK.g01 (geometry) --- (continued)

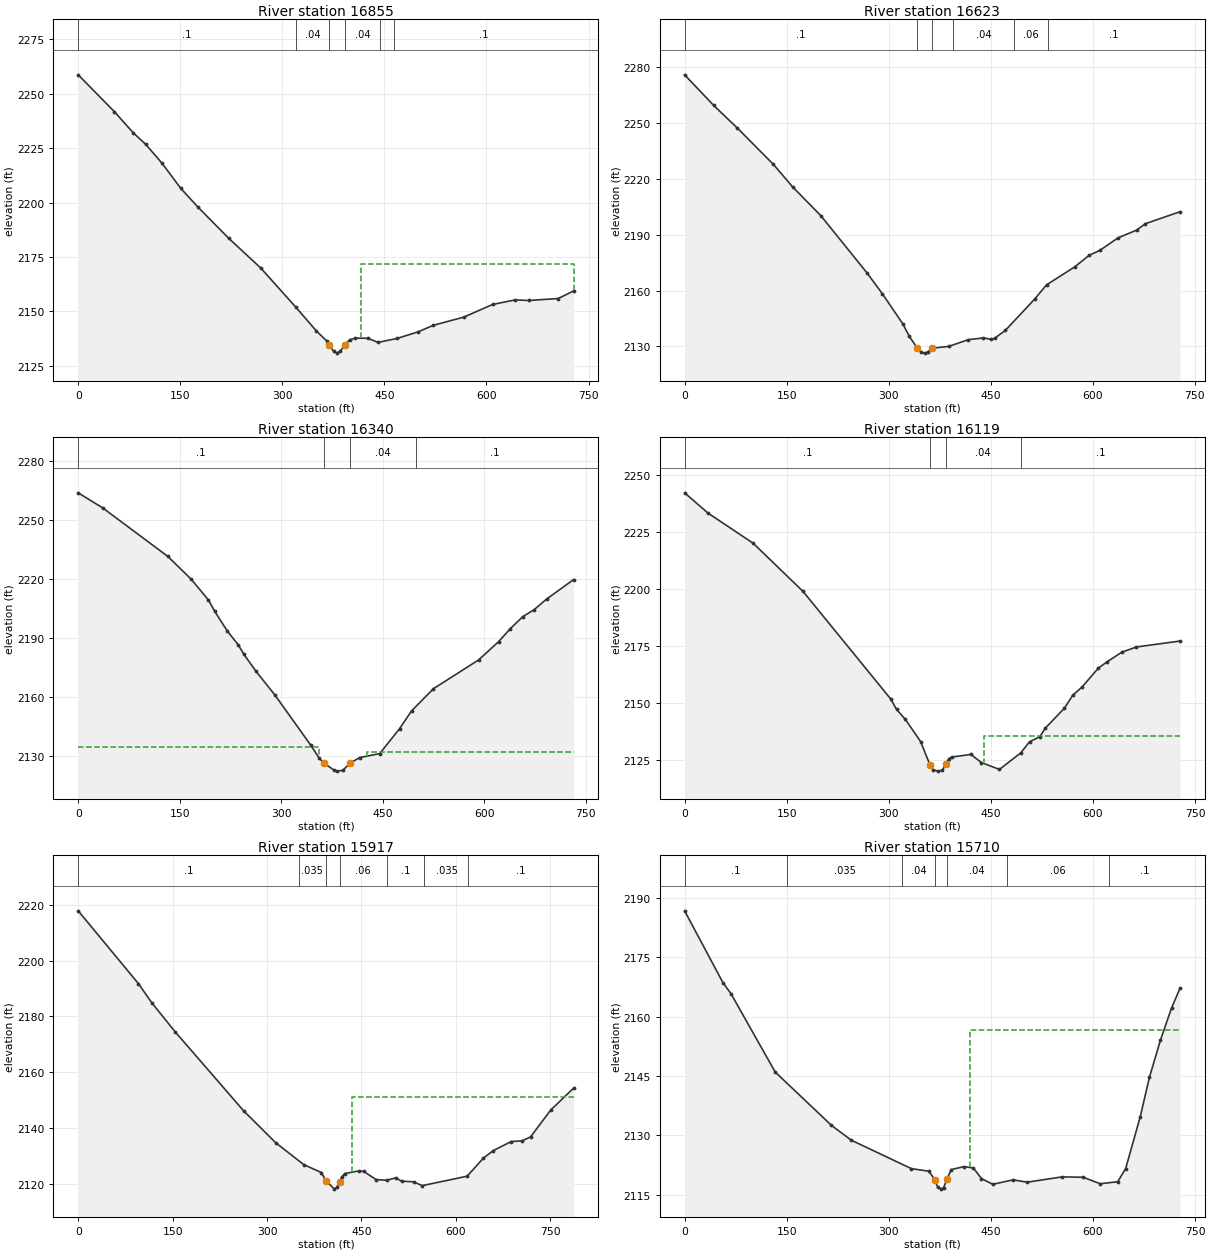
Type RM Length L Ch R = 1 ,16855   ,232,231.8,231.9
XS GIS Cut Line= 3
     2179397.968      222967.241     2179654.074      222708.422
     2179904.201      222444.001
#Sta/Elev= 30
       0 2258.67    53.2 2241.75      81 2232.01    99.1 2226.81   123.4    2218
   150.6 2206.59   176.1  2197.9   221.3 2183.58     268 2170.05     320 2151.91
   350.1 2141.04     366 2136.23   369.12134.531   375.5 2131.63   380.3 2130.88
   385.1 2131.78   392.32134.818   398.9 2137.01   407.4 2137.77   425.5 2137.71
   440.6 2135.81   468.5  2137.6   499.6 2140.67   521.9 2143.65   566.5  2147.4
   609.4 2153.27   642.3 2155.32     662 2155.05   705.5 2155.96   728.1 2159.45
#Mann= 6 ,-1 , 0
       0      .1       0     320     .04       0   369.1    .045       0
   392.3     .04       0  444.11     .06       0  464.11      .1       0
#XS Ineff= 2 , 0
                          415.64         2171.96
Permanent Ineff=
       F       F
Bank Sta=369.1,392.3
XS Rating Curve= 0 ,0
Exp/Cntr=0.3,0.1

Type RM Length L Ch R = 1 ,16623   ,282.5,283.8,280.3
XS GIS Cut Line= 3
     2179579.379      223123.715     2179829.648      222858.746
     2180075.437      222589.957
#Sta/Elev= 30
       0 2275.64    42.5 2259.34    77.5 2247.11   130.7 2227.58   158.7 2215.62
   200.3 2200.14   268.3 2169.41   290.9 2158.24   320.9 2142.11   330.4 2135.43
   341.72129.427   348.3  2126.8   353.5 2126.43   358.2 2127.18   364.5 2129.09
   388.5 2130.05   417.3 2133.65   439.4 2134.58     451 2133.81   456.2 2134.44
   471.9  2138.7   514.6 2155.32   532.3 2163.03   574.1 2172.76     595  2178.9
   610.8 2181.54   637.5 2188.25   664.7 2192.36   677.5  2195.8   728.7 2202.26
#Mann= 6 ,-1 , 0
       0      .1       0   341.7    .045       0   364.5      .1       0
  394.48     .04       0  484.48     .06       0  534.48      .1       0
Bank Sta=341.7,364.5
XS Rating Curve= 0 ,0
Exp/Cntr=0.3,0.1

Type RM Length L Ch R = 1 ,16340   ,217.1,220.6,225.1
XS GIS Cut Line= 3
     2179813.981      223328.961     2180042.075      223038.579
     2180267.725      222754.176
#Sta/Elev= 30
       0 2264.01    36.4  2256.3   132.4 2231.67   166.8 2220.13   192.5 2209.48
   201.8 2203.71   220.5 2193.62   236.7  2186.6     245 2181.76   262.6 2173.27
   290.9 2161.05   343.4 2135.73     356  2129.1   362.72126.582   378.6 2122.75
   382.7 2122.37   391.1 2122.77     402 2126.47   416.2 2129.28   445.6 2131.28
   474.9 2143.94   492.8 2153.06   525.1 2164.33   591.9 2178.99   621.5 2188.31
   638.2 2194.71   657.3 2201.06   673.6 2204.44   692.3 2209.95   732.3 2219.88
#Mann= 4 ,-1 , 0
       0      .1       0   362.7    .045       0     402     .04       0
  499.25      .1       0
#XS Ineff= 2 , 0
          355.19 2134.55  427.49         2132.12
Permanent Ineff=
       F       F
Bank Sta=362.7,402
XS Rating Curve= 0 ,0
Exp/Cntr=0.3,0.1

Type RM Length L Ch R = 1 ,16119   ,202.9,201.9,200.9
XS GIS Cut Line= 3
     2179922.869      223422.583     2180200.742       223187.46
     2180478.614      222952.337
#Sta/Elev= 30
       0 2242.12    34.3 2233.24   100.8 2219.99     174 2198.86   302.8 2151.69
   311.4 2147.09   324.3 2142.75   346.7 2133.02   360.72122.629   364.8 2120.69
   371.8 2120.03   378.8  2120.4   383.72123.074   388.1 2125.46   393.1 2126.23
   420.7 2127.35     436 2123.78   462.6 2120.78     494 2128.06   506.8 2132.92
     522 2135.12   530.1 2138.94   558.1 2147.64   570.2 2153.29   583.7 2156.86
   607.9 2165.21   620.8 2168.01   642.3 2172.19   663.8 2174.49     728 2177.11
#Mann= 4 ,-1 , 0
       0      .1       0   360.7    .045       0   383.7     .04       0
     494      .1       0
#XS Ineff= 2 , 0
                          439.86         2135.23
Permanent Ineff=
       F       F
Bank Sta=360.7,383.7
XS Rating Curve= 0 ,0
Exp/Cntr=0.3,0.1

Type RM Length L Ch R = 1 ,15917   ,205.1,207.3,207
XS GIS Cut Line= 2
     2180049.003      223613.488     2180616.711      223068.349
#Sta/Elev= 30
       0 2217.89    95.6  2191.8   117.1 2184.84   154.2 2174.45   262.7 2146.16
   313.9 2134.66   358.4 2126.83   386.3    2124   393.52121.019   407.1 2118.04
   411.8 2118.89  415.52 2120.73   418.7 2122.46   423.4 2123.62   445.8 2124.58
   453.6  2124.4   473.1 2121.48     490 2121.21   504.2 2122.06     514 2120.89
   532.7 2120.67   546.4 2119.29   617.9 2122.68   643.8 2129.19   659.6 2131.89
   687.9 2135.12   705.1 2135.35   718.7 2136.79   750.5 2146.38   787.1 2154.29
#Mann= 7 ,-1 , 0
       0      .1       0     350    .035       0   393.5    .045       0
  415.52     .06       0     490      .1       0     550    .035       0
     620      .1       0
#XS Ineff= 2 , 0
                          434.36         2151.23
Permanent Ineff=
       F       F
Bank Sta=393.5,415.52
XS Rating Curve= 0 ,0
Exp/Cntr=0.3,0.1

Type RM Length L Ch R = 1 ,15710   ,178.7,178,176.8
XS GIS Cut Line= 3
     2180187.161      223727.587     2180466.168      223493.825
     2180747.125      223262.317
#Sta/Elev= 30
       0 2186.73    56.2  2168.6    68.1 2165.78   133.1 2145.97   215.7 2132.49
   244.8 2128.74   333.2 2121.54     359 2120.89   367.32118.787   371.9 2116.83
   376.2 2116.36   380.4 2116.67  385.342118.807   391.6  2121.3   410.3 2122.04
   424.2 2121.73   436.1 2119.04   452.7 2117.58   482.4  2118.7   503.5 2118.12
   554.7 2119.46   585.7 2119.36   610.7 2117.72   636.3 2118.23     648 2121.54
   669.5 2134.69   682.9  2144.6   699.2 2154.06   715.5 2162.18     728  2167.2
#Mann= 7 ,-1 , 0
       0      .1       0     150    .035       0     320     .04       0
   367.3    .045       0  385.34     .04       0  473.99     .06       0
  623.99      .1       0
#XS Ineff= 2 , 0
                          418.66         2156.63
Permanent Ineff=
       F       F
Bank Sta=367.3,385.34
XS Rating Curve= 0 ,0
Exp/Cntr=0.3,0.1

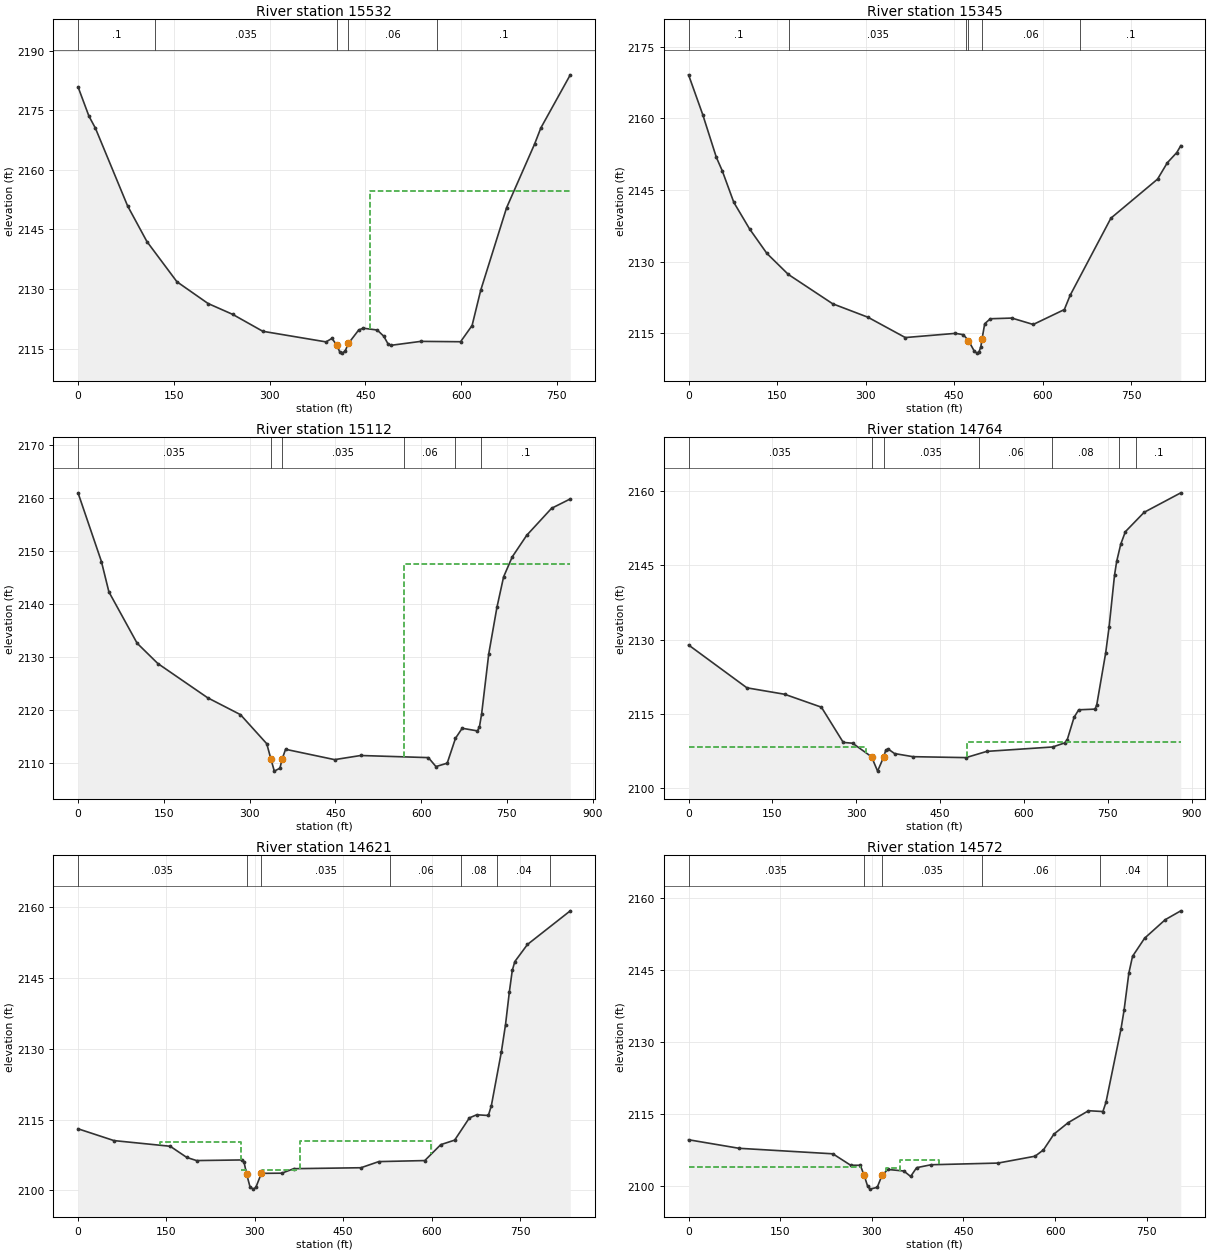
Type RM Length L Ch R = 1 ,15532   ,175.6,186.7,197.6
XS GIS Cut Line= 3
     2180206.198      223749.696     2180529.906      223677.724
     2180850.108      223376.901
#Sta/Elev= 30
       0 2180.88    17.1  2173.5    27.2 2170.49    77.6 2150.92   107.9 2141.93
   154.9 2131.81   203.7 2126.33   242.2  2123.6   289.4 2119.34   388.4 2116.67
   397.7 2117.55  404.912115.935   410.1 2114.09   413.9 2113.84   418.6 2114.43
   423.42116.265   439.5 2119.64   446.4 2120.12   468.6 2119.66   478.9 2118.09
   485.9 2116.06   489.9  2115.8   536.9  2116.8   599.2 2116.71   617.2 2120.79
   630.7 2129.66   671.2 2150.43   715.1 2166.48   724.9 2170.54     771 2183.91
#Mann= 5 ,-1 , 0
       0      .1       0     120    .035       0  404.91    .045       0
   423.4     .06       0  561.61      .1       0
#XS Ineff= 2 , 0
                          458.01         2154.59
Permanent Ineff=
       F       F
Bank Sta=404.91,423.4
XS Rating Curve= 0 ,0
Exp/Cntr=0.3,0.1

Type RM Length L Ch R = 1 ,15345   ,226.8,233,233.2
XS GIS Cut Line= 3
     2180228.522      223801.668     2180739.975      223755.849
      2181059.42      223780.155
#Sta/Elev= 30
       0 2169.09      24 2160.77    47.1 2151.81      57 2149.03    76.7 2142.38
   103.3 2136.84   132.7  2131.7     169  2127.3   244.2 2121.15     304 2118.33
   367.2 2114.08   452.2 2114.96   465.4 2114.68   474.2 2113.46     484 2111.24
   488.5 2110.82   491.8 2111.01   495.1 2112.12   497.22113.792   501.7 2116.97
   511.2 2118.02   547.7 2118.16   583.9 2116.82   636.6 2119.94   646.4 2122.92
   715.5 2139.08   794.5 2147.25     811 2150.67   827.1 2152.82   833.9 2154.26
#Mann= 6 ,-1 , 0
       0      .1       0     170    .035       0     470     .06       0
   474.2    .045       0   497.2     .06       0   663.5      .1       0
Bank Sta=474.2,497.2
XS Rating Curve= 0 ,0
Exp/Cntr=0.3,0.1

Type RM Length L Ch R = 1 ,15112   ,356,348.4,332.4
XS GIS Cut Line= 3
     2180231.295      223896.474     2180904.906      223932.932
     2181064.628      223837.446
#Sta/Elev= 30
       0 2160.99    40.9 2148.03      54 2142.29   103.3 2132.61   139.5 2128.78
   226.7 2122.31     284 2119.13     330 2113.64   337.12110.807   343.2 2108.47
     353 2109.02     3572110.788   362.9 2112.59   448.6 2110.64   494.3 2111.42
   612.6 2111.02   625.8 2109.33   645.5 2109.97     660 2114.67   671.7 2116.56
   698.4 2116.06   701.9 2116.85   705.7 2119.27   718.2 2130.64   732.4 2139.35
   744.1 2145.13   759.2  2148.9   784.5 2152.97     828 2158.07   860.7 2159.84
#Mann= 6 ,-1 , 0
       0    .035       0   337.1    .045       0     357    .035       0
     570     .06       0     660     .08       0   704.6      .1       0
#XS Ineff= 2 , 0
                          569.99          2147.5
Permanent Ineff=
       F       F
Bank Sta=337.1,357
XS Rating Curve= 0 ,0
Exp/Cntr=0.3,0.1

Type RM Length L Ch R = 1 ,14764   ,146.7,142.4,136.6
XS GIS Cut Line= 2
     2180385.809      224410.363     2181078.517       223866.96
#Sta/Elev= 30
       0 2128.93   104.4 2120.27   171.9 2118.97   237.6 2116.36   276.7 2109.24
   293.4 2109.08   327.32106.339   338.1 2103.44  348.762106.232   352.6 2107.63
   356.8 2107.93   368.4 2106.99   401.2 2106.36   496.2 2106.17   533.4 2107.43
   651.2 2108.32   672.8 2109.14   677.4 2109.82   689.5 2114.31   697.8 2115.83
     727 2115.97     730 2116.79     746 2127.29   752.1 2132.52   761.9 2143.07
   765.7 2145.81   772.9 2149.26   781.2 2151.81   814.8 2155.73   880.4 2159.67
#Mann= 7 ,-1 , 0
       0    .035       0   327.3    .045       0  348.76    .035       0
     520     .06       0     650     .08       0     770     .04       0
     800      .1       0
#XS Ineff= 2 , 0
          317.32 2108.35  498.88         2109.25
Permanent Ineff=
       F       F
Bank Sta=327.3,348.76
XS Rating Curve= 0 ,0
Exp/Cntr=0.5,0.3

Type RM Length L Ch R = 1 ,14621   ,49.7,49.5,50.5
XS GIS Cut Line= 3
     2180573.309      224550.988     2180948.309      224018.002
     2181088.934      223899.946
#Sta/Elev= 30
       0 2113.07      61 2110.57   156.4 2109.37   184.6    2107   201.1 2106.34
   277.6 2106.47   281.6 2106.07  286.14 2103.45   291.9 2100.74   297.6 2100.29
   301.7 2100.64   311.1 2103.63   345.8 2103.67   366.1 2104.62   480.1 2104.82
   510.3 2106.12   588.4 2106.34   615.5 2109.71   639.1 2110.67   664.1 2115.38
   676.5 2116.04   696.3 2115.89   701.4 2117.99   718.4 2129.39   725.4 2135.13
     732 2142.15   736.9 2146.63   741.2 2148.49   762.6 2152.11   835.3 2159.24
#Mann= 7 ,-1 , 0
       0    .035       0  286.14    .045       0   311.1    .035       0
     530     .06       0     650     .08       0  711.69     .04       0
  801.69      .1       0
#XS Ineff= 4 ,-1
  139.52  276.98 2110.32  276.98  285.422104.302   312.7  374.29 2104.32
  375.86   598.8 2110.56
Permanent Ineff=
       F       F       F       F
Bank Sta=286.14,311.1
XS Rating Curve= 0 ,0
Exp/Cntr=0.5,0.3

Type RM Length L Ch R = 1 ,14572   ,148.2,144.5,134.6
XS GIS Cut Line= 3
     2180623.656      224573.557     2180988.239      224031.891
     2181104.559      223932.932
#Sta/Elev= 30
       0 2109.63    82.6 2107.85   236.2  2106.7   265.3 2104.32   281.1 2104.31
   287.32102.261   292.9 2100.03   296.9 2099.34   308.8 2099.71   316.7 2102.23
   326.1 2103.44   352.3 2103.12   363.5 2101.98   373.3 2103.81     397 2104.42
   506.5 2104.77   567.2  2106.2   580.9 2107.52   597.9 2110.78   621.2 2113.18
   654.6 2115.68   678.2 2115.51   683.2 2117.43   707.8 2132.71   712.8  2136.6
   720.7 2144.38   726.7 2147.86   746.5 2151.64   780.3  2155.5   805.7 2157.34
#Mann= 6 ,-1 , 0
       0    .035       0   287.3    .045       0   316.7    .035       0
     480     .06       0  672.93     .04       0  782.93      .1       0
#XS Ineff= 3 ,-1
       0  282.23 2104.03  322.97     346 2103.74  346.58  409.44 2105.38
Permanent Ineff=
       F       F       F
Bank Sta=287.3,316.7
XS Rating Curve= 0 ,0
Exp/Cntr=0.5,0.3

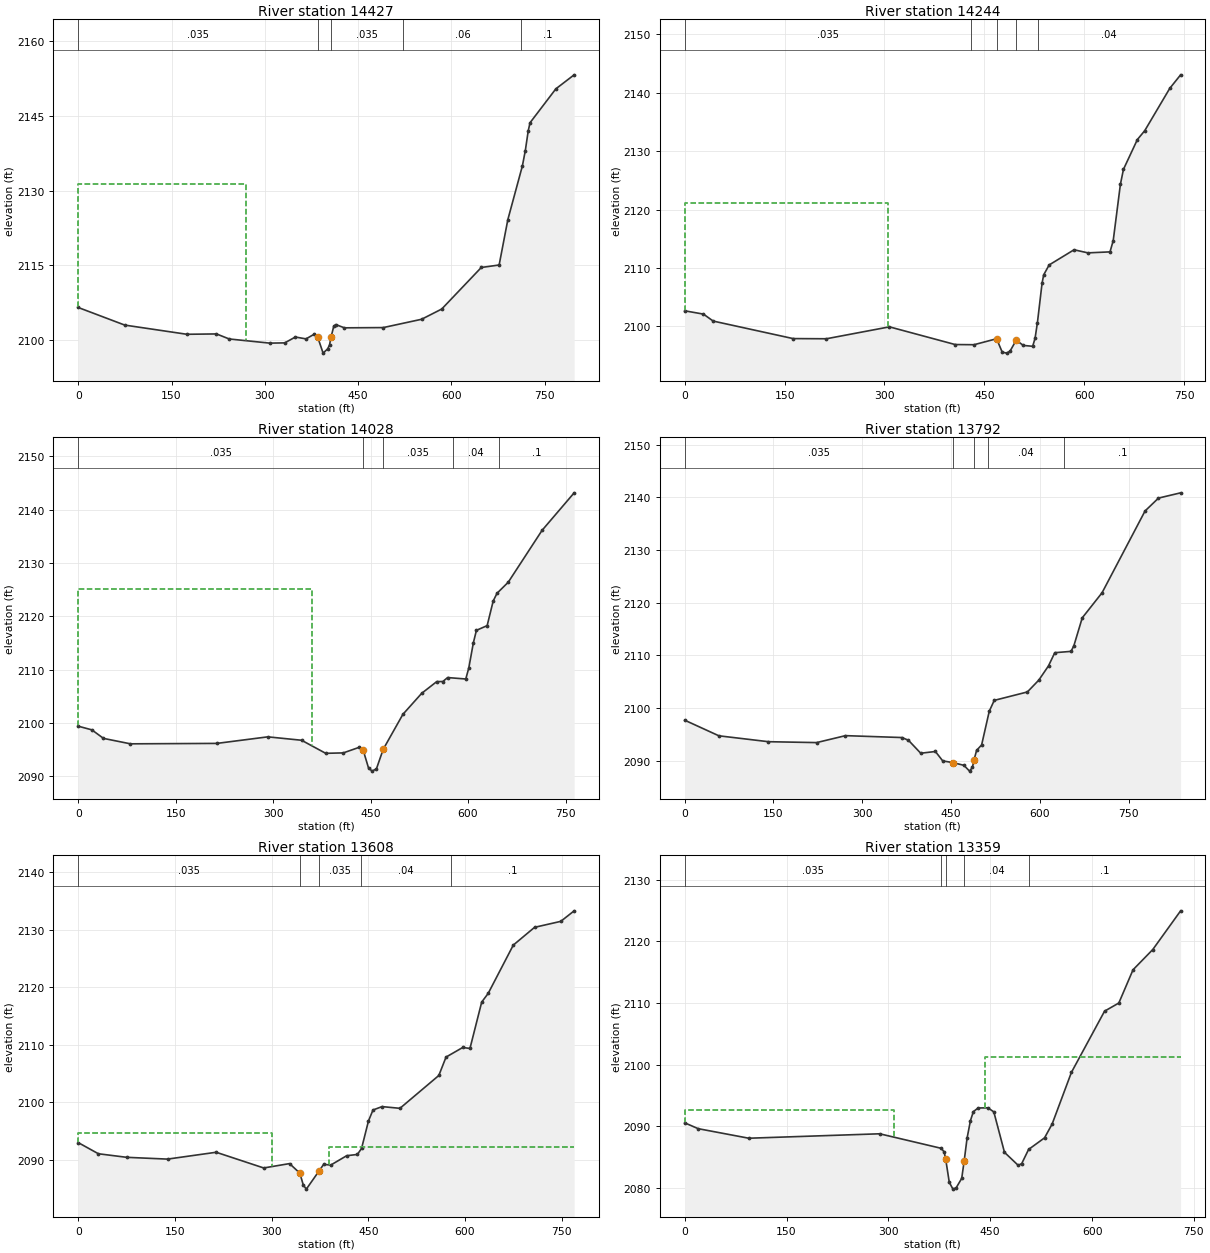
Type RM Length L Ch R = 1 ,14427   ,181.3,183.7,186
XS GIS Cut Line= 3
       2180818.1      224707.238     2180963.934      224226.335
     2181142.753       223991.96
#Sta/Elev= 30
       0  2106.6    74.8 2103.08   174.7 2101.24   222.3 2101.31   242.8  2100.3
     308 2099.47     332 2099.52   349.1 2100.69   366.2 2100.32   379.8 2101.28
     385 2100.67   393.7 2097.47     401 2098.32     404  2099.1  406.552100.708
   410.8 2102.83   414.1 2103.18     428 2102.53   490.4 2102.58     552 2104.24
   584.4 2106.29     648  2114.6   676.7  2115.1   690.7 2124.18   714.1 2134.93
   718.8 2137.99   723.5 2141.96   726.4 2143.56   767.9 2150.34   797.3 2153.14
#Mann= 5 ,-1 , 0
       0    .035       0     385    .045       0  406.55    .035       0
  522.53     .06       0  712.53      .1       0
#XS Ineff= 2 , 0
          269.36 2131.34
Permanent Ineff=
       F       F
Bank Sta=385,406.55
XS Rating Curve= 0 ,0
Exp/Cntr=0.3,0.1

Type RM Length L Ch R = 1 ,14244   ,207.6,215.6,211
XS GIS Cut Line= 3
     2180934.854      224806.703     2181139.281      224288.835
     2181274.697      224158.627
#Sta/Elev= 30
       0 2102.68    28.2 2102.11    42.8 2100.92   162.8 2097.92   212.8 2097.89
   307.4 2099.93   406.1  2096.9   434.4 2096.87   468.32097.892   476.7 2095.61
   483.4 2095.43   488.5 2095.77   497.8 2097.65   508.4 2096.75   522.5  2096.6
   526.1 2097.99   529.6 2100.65   536.6 2107.42     539 2108.83   547.2 2110.53
   584.6 2113.13   605.4  2112.6   638.6 2112.77   643.4 2114.69   654.2 2124.35
   658.8 2126.91   679.7 2132.01   690.7 2133.52   728.3 2140.77   744.6 2143.09
#Mann= 5 ,-1 , 0
       0    .035       0     430      .1       0   468.3    .045       0
   497.8      .1       0     530     .04       0
#XS Ineff= 2 , 0
          304.67 2121.07
Permanent Ineff=
       F       F
Bank Sta=468.3,497.8
XS Rating Curve= 0 ,0
Exp/Cntr=0.3,0.1

Type RM Length L Ch R = 1 ,14028   ,220.8,236.4,243.9
XS GIS Cut Line= 3
     2181032.076       224896.98     2181264.281      224457.238
     2181479.559      224300.988
#Sta/Elev= 30
       0 2099.38      21 2098.69    38.9 2097.09    80.4 2096.07   213.4 2096.15
   291.8 2097.38   343.8 2096.74   380.9 2094.29     408 2094.37   432.8 2095.43
   438.42094.961   446.8 2091.55   452.3 2090.95     459 2091.38  469.412095.045
   499.7  2101.6   528.7 2105.55   551.8 2107.74   561.2 2107.76   568.6  2108.5
   596.5 2108.23   601.2 2110.33   608.2 2115.04   612.9 2117.36   629.4 2118.24
   638.7 2122.86   644.6 2124.31   661.9 2126.39   713.9 2136.11   763.3 2143.15
#Mann= 5 ,-1 , 0
       0    .035       0   438.4    .045       0  469.41    .035       0
  577.28     .04       0  647.28      .1       0
#XS Ineff= 2 , 0
          360.15 2125.05
Permanent Ineff=
       F       F
Bank Sta=438.4,469.41
XS Rating Curve= 0 ,0
Exp/Cntr=0.3,0.1

Type RM Length L Ch R = 1 ,13792   ,176.4,183.3,165.8
XS GIS Cut Line= 3
     2181104.993       224959.48      2181349.35       224679.46
     2181745.358      224433.276
#Sta/Elev= 30
       0 2097.67    57.8  2094.7   141.5 2093.58   222.9 2093.41   271.7 2094.73
   367.1 2094.37   378.1 2093.85   398.8 2091.39   423.6 2091.72     436 2089.93
   453.22089.612   471.8 2089.09   481.3 2087.99   486.1  2088.7     4892090.158
   493.2 2091.93   501.7 2092.97   514.6 2099.37     523 2101.43     579 2103.03
   598.3 2105.28   614.7 2107.99   625.3 2110.49   652.8 2110.74   657.6 2111.83
   671.7 2117.11   705.2 2121.88   777.8 2137.41   800.5 2139.86   837.9 2140.86
#Mann= 5 ,-1 , 0
       0    .035       0   453.2    .045       0     489    .035       0
  511.65     .04       0  641.65      .1       0
Bank Sta=453.2,489
XS Rating Curve= 0 ,0
Exp/Cntr=0.3,0.1

Type RM Length L Ch R = 1 ,13608   ,243,249.4,251.3
XS GIS Cut Line= 3
     2181302.475      225068.349     2181543.795      224714.182
     2181789.701       224478.42
#Sta/Elev= 30
       0 2092.96    31.3 2091.02    75.2  2090.4   138.5 2090.09     214 2091.28
   287.7 2088.55   327.8 2089.31   343.8 2087.64   349.1 2085.58   353.8 2084.87
     373 2087.94   380.7 2089.18   391.6 2089.05   416.4 2090.68     433  2090.9
   439.5 2091.95   450.2 2096.73   457.2 2098.63   471.3 2099.22     499 2098.92
   559.3 2104.63   570.5 2107.83   596.4  2109.5   607.6 2109.33   625.8 2117.39
   635.9 2118.91   674.8  2127.3   707.8 2130.39   748.5 2131.43   769.2 2133.26
#Mann= 5 ,-1 , 0
       0    .035       0   343.8    .045       0     373    .035       0
  438.57     .04       0  578.57      .1       0
#XS Ineff= 2 , 0
          300.76 2094.61  389.15         2092.13
Permanent Ineff=
       F       F
Bank Sta=343.8,373
XS Rating Curve= 0 ,0
Exp/Cntr=0.3,0.1

Type RM Length L Ch R = 1 ,13359   ,243.2,244.1,242.8
XS GIS Cut Line= 3
      2181392.01      225143.684      2181674.46      224909.576
     2181951.949       224674.78
#Sta/Elev= 30
       0 2090.56    19.9 2089.61    94.4 2088.06   287.2 2088.78   377.9 2086.42
   382.2 2085.83  384.482084.618   389.7  2080.9   395.1  2079.8   399.9 2080.03
     408 2081.54  411.55  2084.3   415.9 2088.07   420.9 2090.93   425.2 2092.38
   432.2 2092.97   446.7 2092.99   455.3 2092.33     471 2085.77   491.3 2083.65
   496.4 2083.95   506.5 2086.24     530 2088.12   541.2 2090.37   569.6 2098.75
   618.4 2108.68   639.4    2110   660.3 2115.39   689.4 2118.68   730.4 2124.96
#Mann= 5 ,-1 , 0
       0    .035       0  376.86     .04       0  384.48    .045       0
  411.55     .04       0  506.86      .1       0
#XS Ineff= 2 , 0
          308.45 2092.69  442.88         2101.22
Permanent Ineff=
       F       F
Bank Sta=384.48,411.55
XS Rating Curve= 0 ,0
Exp/Cntr=0.3,0.1

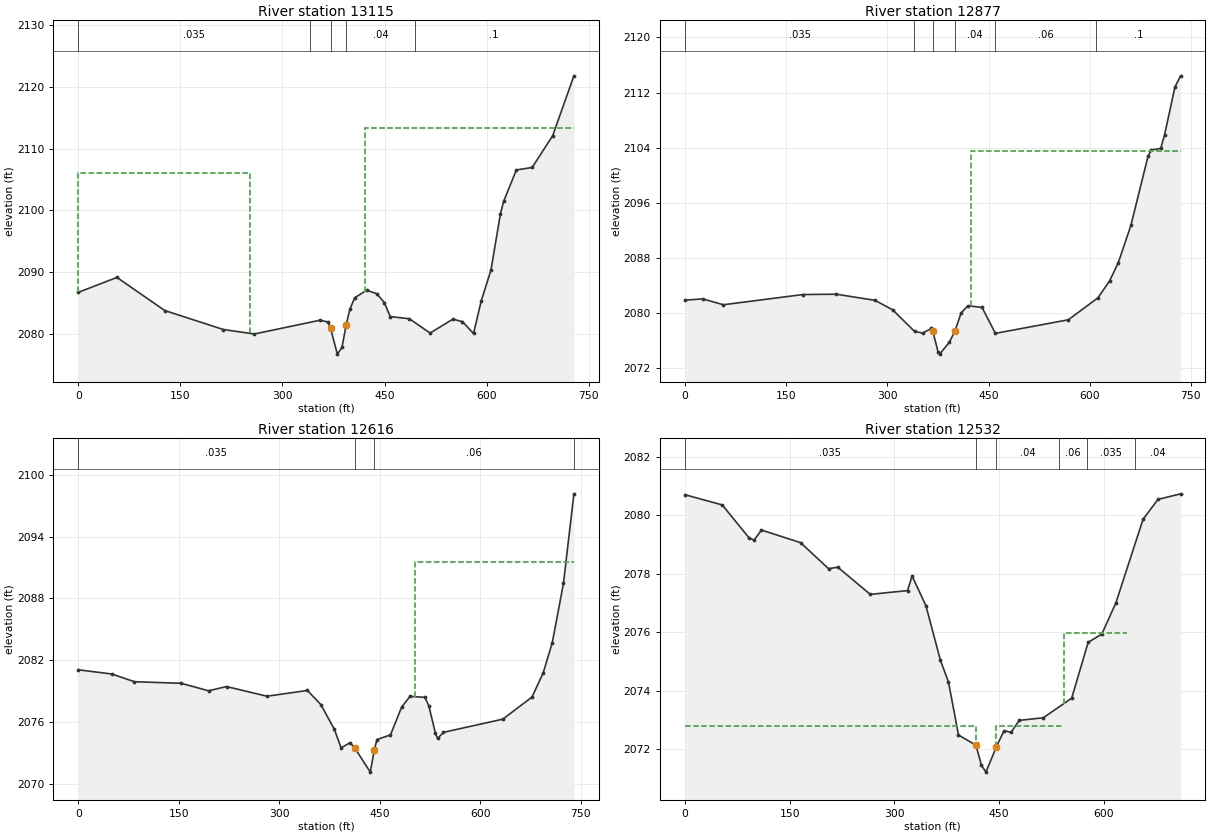
Type RM Length L Ch R = 1 ,13115   ,237.7,237.6,236.7
XS GIS Cut Line= 3
     2181567.044      225318.513     2181844.136      225082.471
     2182121.229      224846.429
#Sta/Elev= 30
       0 2086.73    56.9 2089.15   127.2 2083.79   213.2 2080.72   258.8    2080
   354.8 2082.22   366.5 2081.96   370.6 2080.93   380.6 2076.74   387.4 2077.83
   393.5 2081.45     399    2084     406 2085.85   423.7 2087.08   438.6 2086.51
   449.6 2085.08   458.2 2082.82   486.4 2082.46   516.8 2080.15   550.3  2082.4
   564.3 2081.99   580.6 2080.08   591.8 2085.31   606.2 2090.35   620.1 2099.44
   624.8 2101.45   643.5 2106.54   666.7 2106.94   696.9  2112.1     728 2121.77
#Mann= 5 ,-1 , 0
       0    .035       0     340     .04       0   370.6    .045       0
   393.5     .04       0     494      .1       0
#XS Ineff= 2 , 0
          252.21 2105.97  420.68         2113.32
Permanent Ineff=
       F       F
Bank Sta=370.6,393.5
XS Rating Curve= 0 ,0
Exp/Cntr=0.3,0.1

Type RM Length L Ch R = 1 ,12877   ,248.8,261.2,269.7
XS GIS Cut Line= 2
     2181725.563      225506.678     2182273.127      225016.819
#Sta/Elev= 30
       0 2081.89    26.4 2082.07    56.9 2081.22   174.7  2082.7   224.5 2082.75
   281.7 2081.86   307.8 2080.49   340.4 2077.35   352.2 2077.12   365.4 2077.78
   367.32077.421   375.2 2074.38   377.6 2074.06   391.8 2075.77   400.22077.402
   409.4 2080.04   419.4 2081.08   440.4 2080.83   460.1 2077.07   568.3 2079.04
   612.2 2082.23   629.5  2084.7   642.4 2087.34     661 2092.73   686.4 2102.76
   691.2 2103.67   705.2 2103.89     711  2105.9   726.3 2112.81   734.7 2114.42
#Mann= 6 ,-1 , 0
       0    .035       0     340     .04       0   367.3    .045       0
   400.2     .04       0     460     .06       0     610      .1       0
#XS Ineff= 2 , 0
                          423.71         2103.48
Permanent Ineff=
       F       F
Bank Sta=367.3,400.2
XS Rating Curve= 0 ,0
Exp/Cntr=0.3,0.1

Type RM Length L Ch R = 1 ,12616   ,73.8,84.4,97.4
XS GIS Cut Line= 2
     2181745.184      225544.043     2182469.142      225391.266
#Sta/Elev= 30
       0 2081.06    50.3 2080.65    83.9  2079.9   153.5 2079.75   194.5 2079.02
   221.4 2079.43   281.7 2078.49   342.1 2079.05   362.2 2077.68   382.3 2075.28
   392.4 2073.47   405.8 2073.97   412.52073.491     436 2071.11     442  2073.3
     446 2074.28   466.1 2074.73   482.9 2077.45   495.3 2078.48   517.5 2078.38
   523.3 2077.58   533.2 2074.88   536.5 2074.38   545.2 2074.98   633.8 2076.26
   677.4 2078.41   694.1 2080.77   707.6 2083.69   724.3 2089.46   739.9 2098.17
#Mann= 4 ,-1 , 0
       0    .035       0   412.5    .045       0     442     .06       0
   739.9    .035       0
#XS Ineff= 2 , 0
                           503.4         2091.51
Permanent Ineff=
       F       F
Bank Sta=412.5,442
XS Rating Curve= 0 ,0
Exp/Cntr=0.3,0.1

Type RM Length L Ch R = 1 ,12532   ,51.4,51.7,51.5
XS GIS Cut Line= 3
     2181759.072      225563.141      2182099.35      225505.849
      2182434.42      225649.946
#Sta/Elev= 30
       0  2080.7    53.5 2080.35    92.3 2079.21    99.1 2079.15   109.6 2079.49
   165.6 2079.06   205.6 2078.17   218.9 2078.22   265.4 2077.29   318.7 2077.42
   325.3 2077.92   345.1  2076.9   365.8 2075.04   377.4 2074.29   391.7 2072.48
   416.7 2072.13   424.5 2071.45     431 2071.21     446 2072.08     457 2072.63
     467 2072.57   478.6 2072.98   513.2 2073.07   553.8 2073.74   577.4 2075.65
   596.9 2075.93   617.1    2077     656 2079.86   677.4 2080.54   709.8 2080.73
#Mann= 6 ,-1 , 0
       0    .035       0   416.7    .045       0     446     .04       0
  535.07     .06       0  575.07    .035       0  645.07     .04       0
#XS Ineff= 3 ,-1
       0   416.7  2072.8     446     540  2072.8  542.13   633.4 2075.98
Permanent Ineff=
       F       F       F
Bank Sta=416.7,446
XS Rating Curve= 0 ,0
Exp/Cntr=0.3,0.1