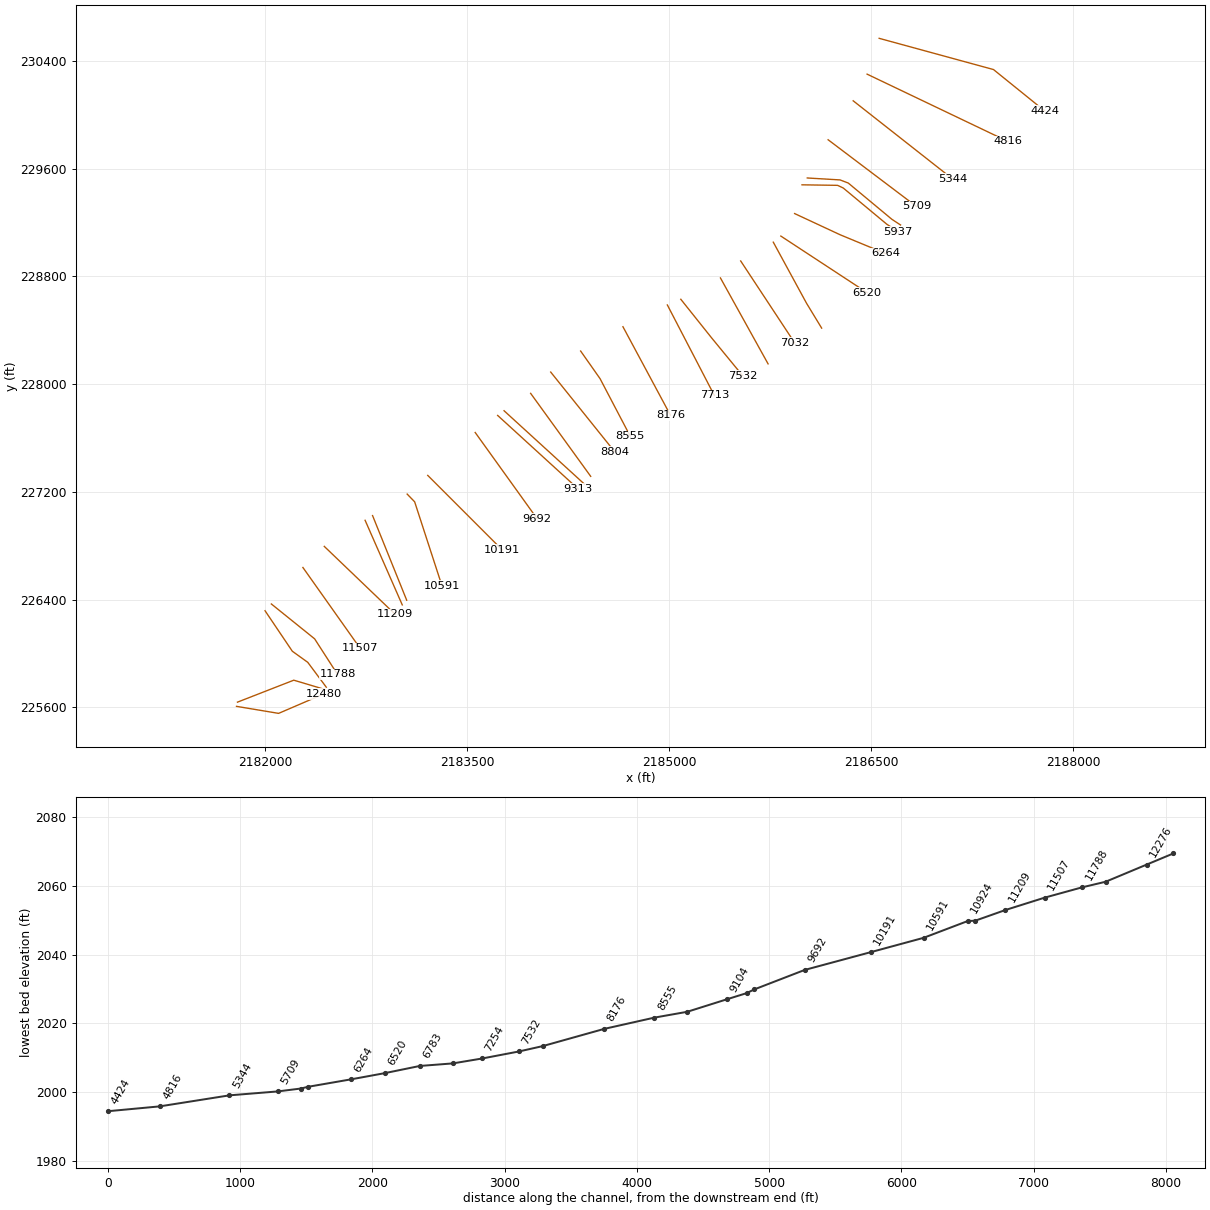
HEC-RAS study SWTSPRNGSCK.prj: SWTSPRNGSCK

--- SWTSPRNGSCK.g01 (geometry) --- (continued)

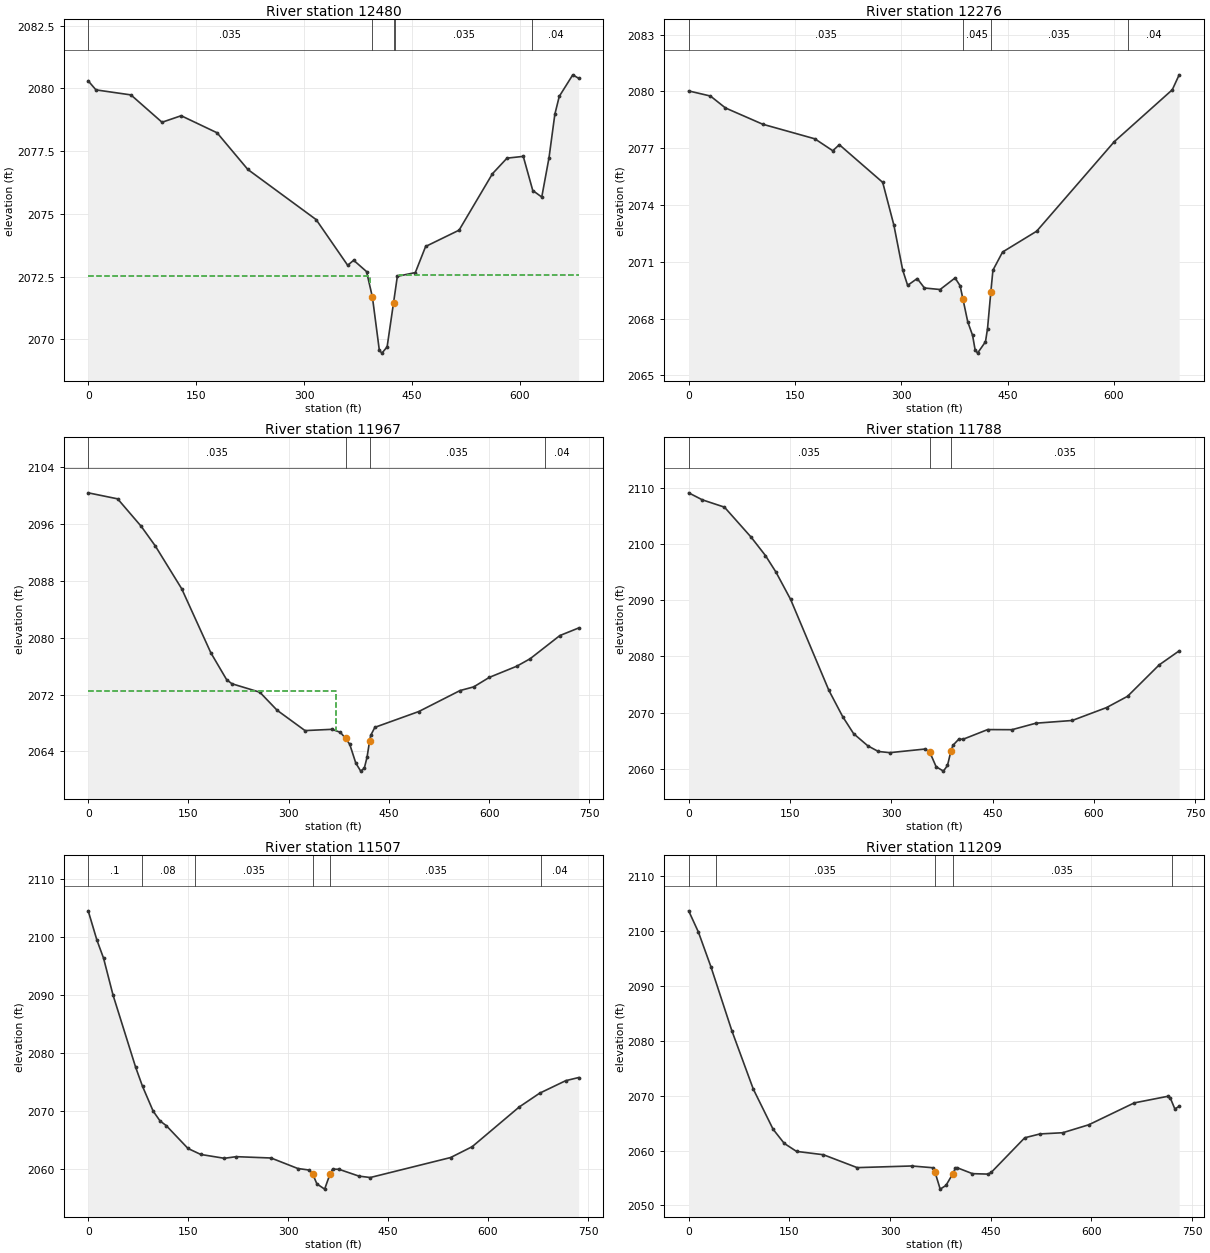
Type RM Length L Ch R = 1 ,12480   ,198.1,203.6,199.8
XS GIS Cut Line= 3
     2181785.114      225606.543     2182097.614       225554.46
     2182432.684      225698.557
#Sta/Elev= 30
       0  2080.3    10.8 2079.94    59.4 2079.74   102.6 2078.65   129.2 2078.91
   179.1 2078.23   221.8 2076.77   316.8 2074.77   360.6 2072.95   368.9 2073.15
   386.8  2072.7     3952071.677   404.6 2069.56   408.2 2069.45   415.4  2069.7
   424.3 2071.45   429.6 2072.51   454.6 2072.66   468.9  2073.7   515.4 2074.35
   561.8  2076.6     582 2077.22   604.6 2077.29   617.8 2075.93   630.3 2075.67
   640.4 2077.24   648.5 2078.97   654.6 2079.68   673.4 2080.54   681.6  2080.4
#Mann= 5 ,-1 , 0
       0    .035       0     395    .045       0   424.3     .04       0
  426.81    .035       0  616.81     .04       0
#XS Ineff= 2 , 0
          391.21 2072.54  431.76         2072.55
Permanent Ineff=
       F       F
Bank Sta=395,424.3
XS Rating Curve= 0 ,0
Exp/Cntr=0.3,0.1

Type RM Length L Ch R = 1 ,12276   ,333.4,309,291
XS GIS Cut Line= 3
     2181792.059      225637.793     2182210.461      225800.988
       2182443.1      225731.543
#Sta/Elev= 30
       0 2080.03    30.7 2079.76    51.9 2079.13   104.5 2078.27     178  2077.5
   203.3 2076.87   212.5 2077.19   273.7  2075.2   289.5 2072.94   301.9 2070.57
   308.9 2069.76   322.4 2070.12   332.6 2069.62   354.7 2069.54   375.8 2070.15
   382.9 2069.74   386.82069.055   393.7 2067.83   400.5 2067.12     404 2066.37
   407.5 2066.18   418.7 2066.78   421.6 2067.48   426.22069.393   429.2 2070.56
   442.8 2071.52   490.9 2072.62   600.4 2077.35   682.2 2080.09   691.9 2080.88
#Mann= 4 ,-1 , 0
       0    .035       0   386.8    .045       0   426.2    .035       0
   619.1     .04       0
Bank Sta=386.8,426.2
XS Rating Curve= 0 ,0
Exp/Cntr=0.3,0.1

Type RM Length L Ch R = 1 ,11967   ,179.5,179.3,176.2
XS GIS Cut Line= 4
      2181996.92      226316.613 2182199.5674414226015.932402548
2182314.23314853225933.477544126     2182451.781      225748.905
#Sta/Elev= 30
       0 2100.42    44.1 2099.57    79.5 2095.68   100.4 2092.94   139.9 2086.91
   183.5 2077.89   207.2 2074.09   215.1 2073.52   256.8 2072.33   282.8 2069.78
   324.5 2066.92   364.7  2067.1   377.3 2066.68   385.2 2065.83   391.4 2064.99
   400.4 2062.36   407.8 2061.21   413.2 2061.62   417.3 2063.17   421.22065.508
   422.8 2066.25     429 2067.38   494.8 2069.61   556.4 2072.56   576.9 2073.08
   600.3 2074.42   641.3 2075.99   661.3 2077.04   705.8 2080.31     734 2081.38
#Mann= 4 ,-1 , 0
       0    .035       0   385.2    .045       0   421.2    .035       0
  683.83     .04       0
#XS Ineff= 2 , 0
          371.25 2072.56
Permanent Ineff=
       F       F
Bank Sta=385.2,421.2
XS Rating Curve= 0 ,0
Exp/Cntr=0.3,0.1

Type RM Length L Ch R = 1 ,11788   ,283.2,281.2,274
XS GIS Cut Line= 3
     2182043.795       226366.96     2182364.975       226108.28
     2182535.114      225844.391
#Sta/Elev= 30
       0 2109.14    20.3 2107.89      53 2106.59    92.6 2101.23   113.7 2097.97
   129.3 2095.02     151 2090.15   207.7 2073.95     228  2069.3   244.3 2066.24
   265.3 2064.08   280.9 2063.07     298 2062.86   349.6  2063.5   356.82063.033
   366.5 2060.35   377.3 2059.57   383.3 2060.58  388.392063.125   391.3 2064.16
   400.2 2065.28   406.5 2065.25   442.8 2066.97   478.8 2066.95   514.4 2068.11
     568 2068.59   618.9 2070.89     650  2072.9   696.8 2078.49   726.4 2080.99
#Mann= 3 ,-1 , 0
       0    .035       0   356.8    .045       0  388.39    .035       0
Bank Sta=356.8,388.39
XS Rating Curve= 0 ,0
Exp/Cntr=0.3,0.1

Type RM Length L Ch R = 1 ,11507   ,292.9,297.8,299.1
XS GIS Cut Line= 2
      2182278.17      226637.793     2182703.517      226037.099
#Sta/Elev= 30
       0 2104.52    13.1 2099.47    23.1 2096.35    37.2 2090.04    71.3 2077.55
    81.5  2074.3    97.5 2070.02   107.8 2068.34   117.3 2067.51   149.8 2063.59
     169 2062.56   204.3  2061.9   222.2 2062.18   274.4 2061.95   314.6 2060.14
   331.4 2059.88   336.92059.184   343.2 2057.49   354.8 2056.59   363.12059.265
   366.7 2060.03   376.2 2060.01   406.3 2058.83   423.3 2058.59   543.8 2062.03
   576.2  2063.9   646.8 2070.74   677.4 2073.11   716.6 2075.27     736 2075.81
#Mann= 6 ,-1 , 0
       0      .1       0      80     .08       0     160    .035       0
   336.9    .045       0   363.1    .035       0     680     .04       0
Bank Sta=336.9,363.1
XS Rating Curve= 0 ,0
Exp/Cntr=0.3,0.1

Type RM Length L Ch R = 1 ,11209   ,231.2,227,217.2
XS GIS Cut Line= 2
      2182436.86      226794.548     2182964.521        226288.8
#Sta/Elev= 30
       0 2103.71    14.5 2099.84    33.4 2093.43    64.5  2081.8    96.3 2071.22
   125.8  2063.9   142.4 2061.32   160.7 2059.86   200.8 2059.25   251.1  2056.9
   332.4  2057.2   364.8 2056.87   367.12056.078   374.8 2052.98   383.4 2053.65
   393.32055.712   397.3 2056.75   399.7  2056.9   422.9  2055.8   445.9 2055.72
   450.8 2056.02   500.8 2062.34   523.5 2063.04   557.4 2063.26   596.2 2064.71
     664  2068.7   714.4 2069.91   717.6 2069.62   724.5  2067.6   730.9 2068.07
#Mann= 5 ,-1 , 0
       0     .08       0      40    .035       0   367.1    .045       0
   393.3    .035       0     720     .04       0
Bank Sta=367.1,393.3
XS Rating Curve= 0 ,0
Exp/Cntr=0.3,0.1

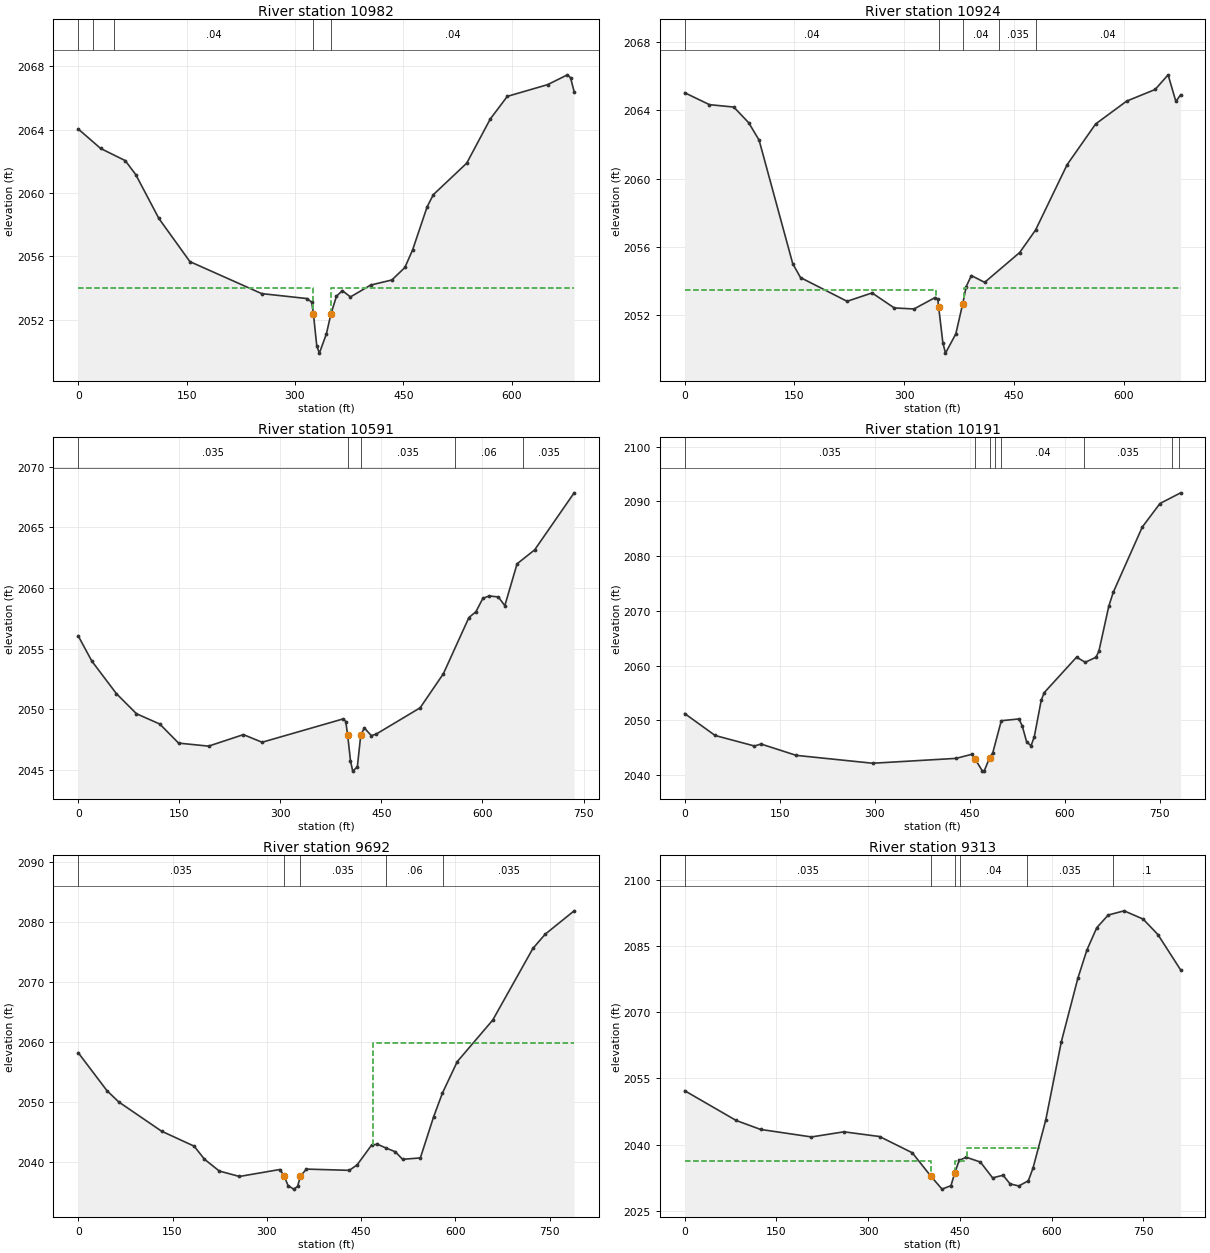
Type RM Length L Ch R = 1 ,10982   ,56.8,58.1,56.9
XS GIS Cut Line= 2
     2182739.975      226988.488     2183016.017      226360.016
#Sta/Elev= 30
       0 2064.05      31 2062.82    65.1 2062.05    79.6 2061.17   111.6  2058.4
   154.6 2055.67   253.9 2053.65   316.1 2053.34   323.1 2053.12   325.52052.386
   330.2 2050.34   333.8 2049.89   343.5 2051.11   349.82052.367   357.4 2053.48
   365.5 2053.84   376.8 2053.44   404.8 2054.19   434.1 2054.51   452.1  2055.3
   462.8 2056.41   482.9 2059.13   491.5  2059.9   537.7 2061.89   570.3 2064.68
   593.9 2066.11   649.7 2066.85   677.1 2067.47   681.4 2067.29   686.4  2066.4
#Mann= 5 ,-1 , 0
       0     .04       0      20    .035       0      50     .04       0
   325.5    .045       0   349.8     .04       0
#XS Ineff= 2 , 0
           325.5    2054   349.8            2054
Permanent Ineff=
       F       F
Bank Sta=325.5,349.8
XS Rating Curve= 0 ,0
Exp/Cntr=0.3,0.1

Type RM Length L Ch R = 1 ,10924   ,332,332.8,329.8
XS GIS Cut Line= 2
     2182795.531       227023.21     2183049.003      226394.738
#Sta/Elev= 30
       0 2065.04    33.9 2064.34    67.1  2064.2    87.5 2063.28   101.7 2062.26
   147.7 2055.01   158.3  2054.2   221.9 2052.81   256.1  2053.3   286.4 2052.42
   313.4 2052.36   342.2 2053.03   345.8 2052.92     3472052.496   352.8 2050.38
   356.4 2049.77   370.5  2050.9   379.82052.638   384.7 2053.67   391.7 2054.32
   409.9 2053.92   457.8 2055.67   479.5 2056.99   522.6 2060.82   561.6 2063.21
     604 2064.55   642.9 2065.23   660.6 2066.09   671.2 2064.53   677.7 2064.92
#Mann= 5 ,-1 , 0
       0     .04       0     347    .045       0   379.8     .04       0
     430    .035       0     480     .04       0
#XS Ineff= 2 , 0
          343.89 2053.48  381.42         2053.56
Permanent Ineff=
       F       F
Bank Sta=347,379.8
XS Rating Curve= 0 ,0
Exp/Cntr=0.3,0.1

Type RM Length L Ch R = 1 ,10591   ,391.2,399.6,405.7
XS GIS Cut Line= 3
     2183052.475      227182.932     2183108.031      227125.641
     2183311.006      226501.565
#Sta/Elev= 30
       0 2056.05    20.2 2053.97    56.8 2051.28    86.5 2049.63   121.1 2048.78
     149 2047.21   193.5 2046.96   245.2 2047.91   272.9 2047.28   393.6 2049.21
   397.1 2048.99   399.82047.919   404.1 2045.77   407.4  2044.9   414.3 2045.25
   419.42047.884   424.7 2048.46     435 2047.83   441.9 2047.94   507.5 2050.12
     542 2052.93   579.9 2057.56   590.3 2058.04   600.6 2059.14   609.8 2059.34
   623.5 2059.26   633.2 2058.54   651.4 2061.99   677.5 2063.14   736.1 2067.84
#Mann= 5 ,-1 , 0
       0    .035       0   399.8    .045       0   419.4    .035       0
   559.8     .06       0   659.8    .035       0
Bank Sta=399.8,419.4
XS Rating Curve= 0 ,0
Exp/Cntr=0.3,0.1

Type RM Length L Ch R = 1 ,10191   ,500.7,499.3,493.6
XS GIS Cut Line= 2
     2183205.253      227321.821     2183759.072      226768.002
#Sta/Elev= 30
       0 2051.25    48.1 2047.24   110.2 2045.32   120.6 2045.68   176.2 2043.61
   296.9 2042.17   428.6 2043.06   453.6 2043.81   458.82042.898   470.3 2040.73
   473.2 2040.82   481.72043.206   486.6 2044.09     500 2049.94   527.8 2050.26
     533 2049.03   539.9 2046.13   546.9 2045.34   552.1    2047   563.1  2053.7
   567.8 2055.07   618.8 2061.54   632.7 2060.62   649.5 2061.53   654.1 2062.63
   669.8 2070.87   676.8  2073.4   722.7 2085.33   750.5 2089.61   783.2 2091.57
#Mann= 8 ,-1 , 0
       0    .035       0   458.8    .045       0   481.7    .035       0
     490     .06       0     500     .04       0     630    .035       0
     770      .1       0     780    .035       0
Bank Sta=458.8,481.7
XS Rating Curve= 0 ,0
Exp/Cntr=0.3,0.1

Type RM Length L Ch R = 1 ,9692    ,358,379.6,380.7
XS GIS Cut Line= 2
     2183557.684      227640.398     2184017.753      226999.773
#Sta/Elev= 30
       0  2058.3    45.7 2051.97    64.5 2050.09   132.5 2045.22   184.4 2042.72
   200.8 2040.54   224.3 2038.58   256.3 2037.67   320.7 2038.83   327.32037.787
   333.8 2036.13   342.8 2035.56   348.9    2036   353.42037.739     363  2038.9
   431.2 2038.69   443.7 2039.62   466.5 2042.89   475.6 2043.05     490 2042.39
   504.3 2041.79   515.8 2040.53   544.1 2040.76   565.2 2047.61   579.3 2051.59
   602.8 2056.81   659.2 2063.73   723.1 2075.67   742.6 2078.04   788.7 2081.94
#Mann= 5 ,-1 , 0
       0    .035       0   327.3    .045       0   353.4    .035       0
     490     .06       0     580    .035       0
#XS Ineff= 2 , 0
                           468.1         2059.85
Permanent Ineff=
       F       F
Bank Sta=327.3,353.4
XS Rating Curve= 0 ,0
Exp/Cntr=0.3,0.1

Type RM Length L Ch R = 1 ,9313    ,69.7,59.6,59.1
XS GIS Cut Line= 2
      2183724.35      227767.206     2184323.309      227220.331
#Sta/Elev= 30
       0 2052.21    84.2 2045.47   124.1 2043.44   207.3 2041.74   260.4  2042.9
   318.8 2041.83   372.3 2038.15   402.32032.906   420.9 2029.92   435.5 2030.71
   441.5 2033.49   448.8 2036.41   460.4 2037.15   483.7 2036.05   503.6 2032.47
   520.8 2033.07   532.1 2031.12   546.4 2030.63     562 2031.81   569.6 2034.64
   590.5 2045.55     616 2063.29   643.1 2077.71   657.8 2084.06   673.9 2089.12
   692.7    2092   718.7 2092.95   749.8 2091.08     774 2087.57   811.1 2079.57
#Mann= 6 ,-1 , 0
       0    .035       0   402.3    .045       0   441.5     .06       0
     450     .04       0     560    .035       0     700      .1       0
#XS Ineff= 3 ,-1
       0   402.3  2036.2   441.5     460  2036.2  460.94   581.3 2039.25
Permanent Ineff=
       F       F       F
Bank Sta=402.3,441.5
XS Rating Curve= 0 ,0
Exp/Cntr=0.3,0.1

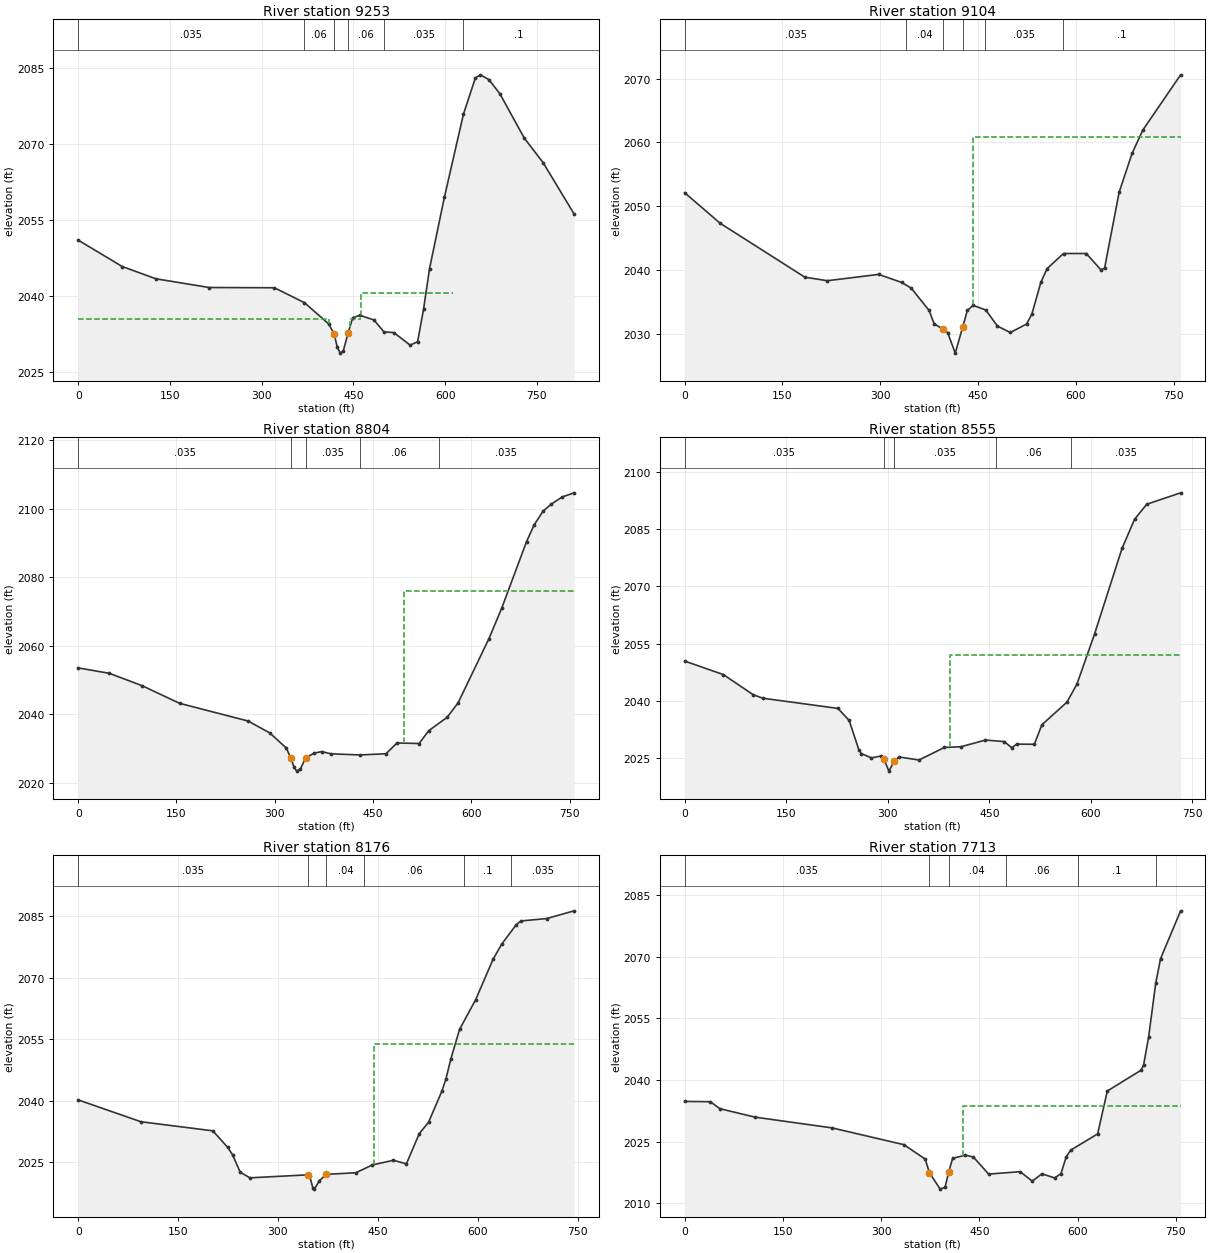
Type RM Length L Ch R = 1 ,9253    ,152.2,148.6,145.2
XS GIS Cut Line= 2
     2183772.093      227801.928     2184371.052      227255.053
#Sta/Elev= 30
       0 2051.09      72 2045.89     127 2043.47   214.2 2041.75   320.8  2041.7
     370 2038.76   409.7 2034.57   418.6  2032.6   423.8 2029.92   428.6 2028.81
   433.5 2029.24   441.5 2032.82   448.9 2035.78   460.5 2036.27   483.7 2035.35
     500    2033   516.2 2032.87   542.9 2030.38   555.1 2031.06   564.9 2037.55
   574.6 2045.48   598.9 2059.56     630 2075.91   649.6 2083.09   657.9 2083.69
   671.8 2082.73   689.6 2079.96   729.5 2071.23   760.6 2066.32   811.1 2056.24
#Mann= 6 ,-1 , 0
       0    .035       0     370     .06       0   418.6    .045       0
   441.5     .06       0     500    .035       0     630      .1       0
#XS Ineff= 3 ,-1
       0  410.15 2035.54  444.42     462 2035.56  462.54  613.06 2040.68
Permanent Ineff=
       F       F       F
Bank Sta=418.6,441.5
XS Rating Curve= 0 ,0
Exp/Cntr=0.3,0.1

Type RM Length L Ch R = 1 ,9104    ,292.5,300.1,298.2
XS GIS Cut Line= 2
     2183969.422      227931.189     2184415.322      227314.877
#Sta/Elev= 30
       0 2052.13    54.6 2047.34   184.2 2038.92   218.7 2038.36   297.6 2039.35
   332.6  2038.1   347.4 2037.21   374.9 2033.71   382.6 2031.62   396.82030.754
   403.4 2030.24     415 2027.03   426.32031.065   433.6 2033.72   442.5  2034.5
   461.8 2033.78   479.8 2031.26   499.4 2030.26   524.4 2031.58   532.5 2033.13
   546.4 2038.13   555.8 2040.25   581.1 2042.62     616 2042.62   638.4 2040.07
     644 2040.29   666.4 2052.21   686.3  2058.3   702.5  2061.9   760.7 2070.58
#Mann= 6 ,-1 , 0
       0    .035       0     340     .04       0   396.8    .045       0
   426.3     .04       0     460    .035       0     580      .1       0
#XS Ineff= 2 , 0
                          442.88         2060.87
Permanent Ineff=
       F       F
Bank Sta=396.8,426.3
XS Rating Curve= 0 ,0
Exp/Cntr=0.3,0.1

Type RM Length L Ch R = 1 ,8804    ,250.2,248.9,246.2
XS GIS Cut Line= 2
     2184118.447      228089.182     2184592.406      227498.905
#Sta/Elev= 30
       0 2053.51    47.4 2051.94    97.7 2048.31   154.7 2043.18   259.4 2038.01
   292.4 2034.53   317.8  2030.1   324.4  2027.2   329.7 2024.46   333.5 2023.39
   339.1 2024.04   347.42027.315   360.4 2028.67   371.7 2029.08   385.6 2028.45
   430.1 2028.11   469.8 2028.46   486.6 2031.61   520.3 2031.45   535.1 2035.21
   563.1 2039.09   579.8  2043.3     627 2062.08   646.5 2070.98   684.3 2090.36
   696.1 2095.31   709.6 2099.27   722.2 2101.34     739 2103.43     757 2104.61
#Mann= 5 ,-1 , 0
       0    .035       0   324.4    .045       0   347.4    .035       0
     430     .06       0     550    .035       0
#XS Ineff= 2 , 0
                          497.35         2075.99
Permanent Ineff=
       F       F
Bank Sta=324.4,347.4
XS Rating Curve= 0 ,0
Exp/Cntr=0.3,0.1

Type RM Length L Ch R = 1 ,8555    ,377.6,379.6,377.9
XS GIS Cut Line= 3
      2184340.67      228245.432     2184484.767      228040.571
     2184708.725      227613.488
#Sta/Elev= 30
       0 2050.46    57.2 2046.92   101.4 2041.64   115.8 2040.74   226.5 2038.08
     243 2034.94   257.3 2027.28   260.9 2026.29   275.8 2025.14   290.6 2025.67
  294.322024.839   301.7 2021.69   309.52024.239   316.5  2025.4   346.2 2024.59
   383.7 2027.88     408 2028.06   444.4 2029.81   472.1 2029.41   483.2  2027.8
   490.6 2028.75   516.6 2028.71   527.7  2033.8   564.7 2039.71   579.5 2044.42
   605.5  2057.5   646.1 2079.89   664.7 2087.51   682.6 2091.44   732.7 2094.43
#Mann= 5 ,-1 , 0
       0    .035       0  294.32    .045       0   309.5    .035       0
  460.46     .06       0  570.46    .035       0
#XS Ineff= 2 , 0
                          392.43         2052.14
Permanent Ineff=
       F       F
Bank Sta=294.32,309.5
XS Rating Curve= 0 ,0
Exp/Cntr=0.3,0.1

Type RM Length L Ch R = 1 ,8176    ,452.3,463,450.2
XS GIS Cut Line= 2
     2184654.906      228425.988     2185007.336      227769.738
#Sta/Elev= 30
       0 2040.19    94.2 2034.86   202.2 2032.64   224.6 2028.59     232 2026.76
   243.3 2022.54   257.9 2021.17   345.72021.905   347.5 2021.72   352.4 2018.73
   354.8 2018.41   362.1 2020.43   372.42022.011     417 2022.41     442 2024.33
   473.5 2025.45   492.9 2024.58   512.3 2031.98   526.2 2034.73   546.2 2042.32
   552.3 2045.31   559.7 2050.19   572.8 2057.41   597.1  2064.7     623 2074.49
   635.8 2078.16   657.6  2082.9   664.9 2083.87   703.7 2084.47   744.9 2086.35
#Mann= 6 ,-1 , 0
       0    .035       0   345.7    .045       0   372.4     .04       0
     430     .06       0     580      .1       0     650    .035       0
#XS Ineff= 2 , 0
                          443.88         2053.88
Permanent Ineff=
       F       F
Bank Sta=345.7,372.4
XS Rating Curve= 0 ,0
Exp/Cntr=0.3,0.1

Type RM Length L Ch R = 1 ,7713    ,176,180.6,184
XS GIS Cut Line= 2
     2184984.767      228587.446     2185333.725      227915.571
#Sta/Elev= 30
       0 2034.76    39.2  2034.7    53.7    2033   107.3 2030.94   224.8 2028.33
   334.6 2024.24   367.2 2020.73   373.6 2017.42   390.1 2013.42   397.5 2013.89
   403.1 2017.57     409  2020.9   428.5 2021.69   440.7 2021.24     464 2017.08
   512.1 2017.67   530.6 2015.36   545.4 2017.15   564.8 2016.15   574.5  2017.2
   582.3 2021.22   589.1 2022.89   630.4 2026.86   645.2  2037.3   696.9 2042.38
   700.6 2043.66   708.3  2050.5   719.1 2063.54   726.5 2069.53   757.1 2081.15
#Mann= 6 ,-1 , 0
       0    .035       0   373.6    .045       0   403.1     .04       0
     490     .06       0     600      .1       0     720    .035       0
#XS Ineff= 2 , 0
                          425.02         2033.64
Permanent Ineff=
       F       F
Bank Sta=373.6,403.1
XS Rating Curve= 0 ,0
Exp/Cntr=0.3,0.1

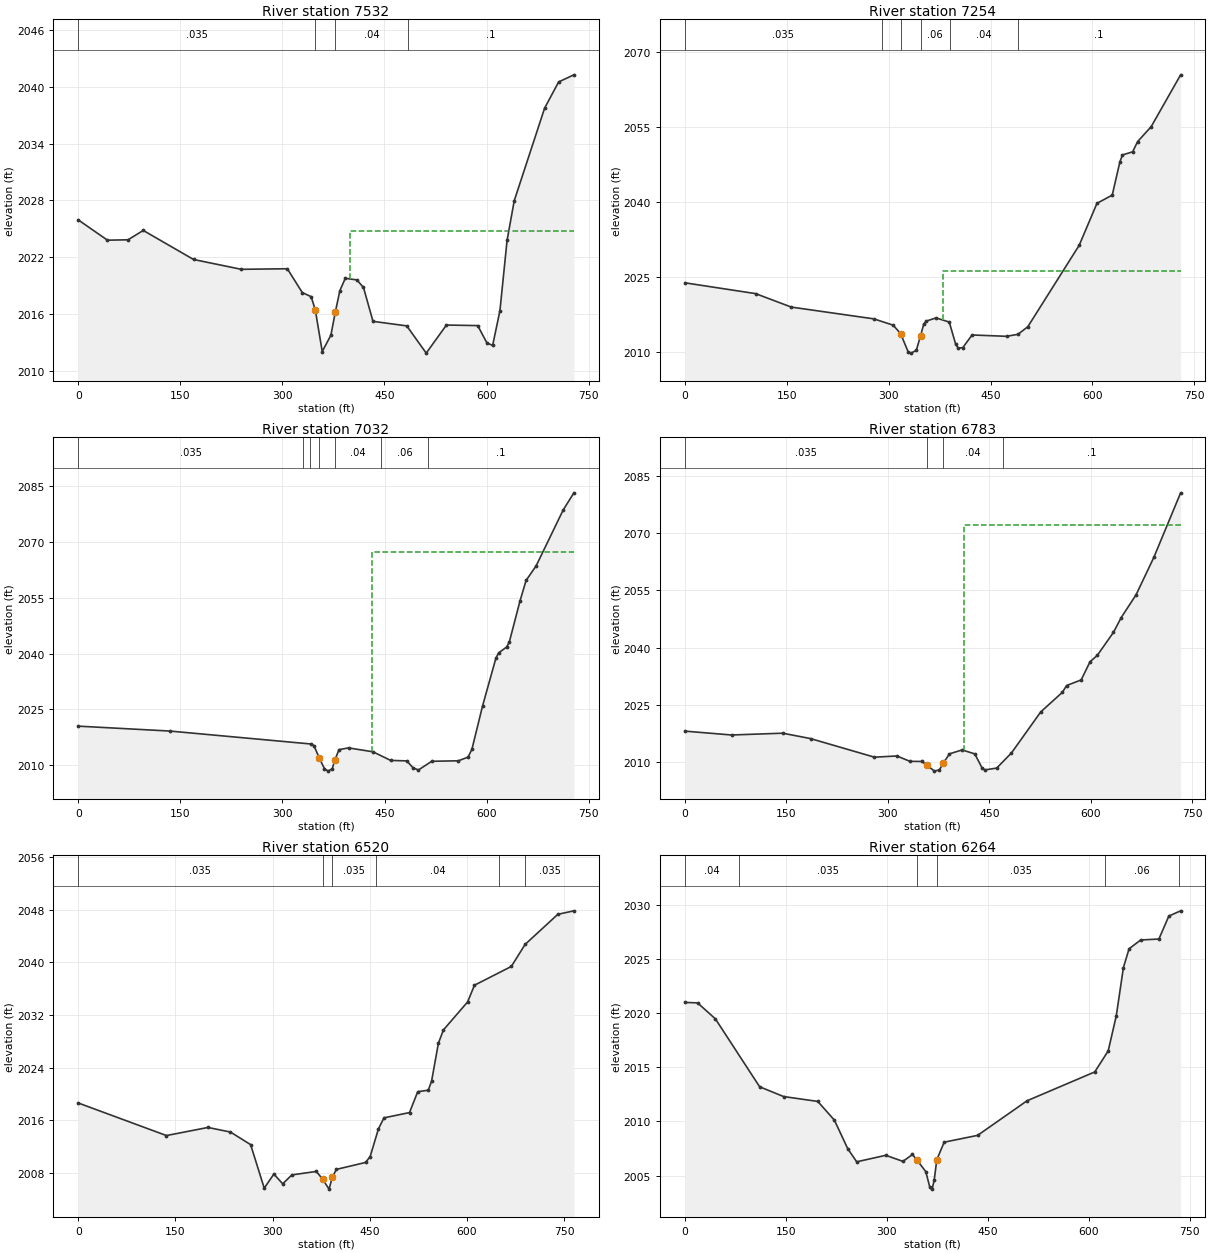
Type RM Length L Ch R = 1 ,7532    ,280.8,278,273
XS GIS Cut Line= 3
     2185084.579      228629.874     2185312.014      228344.837
     2185542.758      228063.674
#Sta/Elev= 30
       0 2025.94      43 2023.79    73.2 2023.83    95.6 2024.82   169.5 2021.75
   239.6 2020.71   307.3 2020.77   329.3 2018.25   342.3 2017.82   348.42016.415
   358.6 2012.02   371.3 2013.74   377.82016.179   384.5 2018.46   392.5 2019.76
   409.5 2019.59   419.2 2018.79   433.2 2015.21   482.8 2014.73   511.4 2011.85
   541.1 2014.82   587.1 2014.76   600.5 2012.94     609 2012.66   619.7 2016.33
   630.2 2023.76   640.7 2027.95   685.4 2037.75     706 2040.52   728.4 2041.27
#Mann= 4 ,-1 , 0
       0    .035       0   348.4    .045       0   377.8     .04       0
  484.65      .1       0
#XS Ineff= 2 , 0
                          399.73         2024.77
Permanent Ineff=
       F       F
Bank Sta=348.4,377.8
XS Rating Curve= 0 ,0
Exp/Cntr=0.3,0.1

Type RM Length L Ch R = 1 ,7254    ,220.1,222,222.9
XS GIS Cut Line= 2
     2185378.902        228788.3     2185732.823      228149.953
#Sta/Elev= 30
       0 2023.86   104.1  2021.7   156.6 2019.01     278 2016.66   306.6  2015.4
   317.52013.725   328.7 2010.07   332.9 2009.81   340.7 2010.36     3472013.319
   351.6 2015.58   355.2  2016.2   369.7 2016.85   389.2 2016.02   398.7 2011.58
   402.3 2010.81   409.1  2010.9   422.8 2013.44   473.5 2013.17   490.4 2013.57
   504.9 2015.09   580.5 2031.35   606.7 2039.74   629.2 2041.39   640.5 2048.05
   644.3 2049.41   659.3 2050.04   666.5 2052.07   686.5 2055.06   729.9 2065.42
#Mann= 6 ,-1 , 0
       0    .035       0     290     .06       0   317.5    .045       0
     347     .06       0     390     .04       0     490      .1       0
#XS Ineff= 2 , 0
                          379.38         2026.25
Permanent Ineff=
       F       F
Bank Sta=317.5,347
XS Rating Curve= 0 ,0
Exp/Cntr=0.3,0.1

Type RM Length L Ch R = 1 ,7032    ,250.2,249.1,247.4
XS GIS Cut Line= 3
     2185529.389      228914.296     2185729.703      228610.371
     2185930.016      228306.446
#Sta/Elev= 30
       0 2020.48   134.7 2019.16   342.4 2015.67   346.3 2015.22   354.2 2011.83
   361.7 2009.04   367.2 2008.38   373.1 2009.04   377.12011.445     383 2014.15
     397 2014.63   432.9 2013.58   458.8 2011.27   482.5 2011.13   491.7 2009.29
   499.6 2008.68   519.2 2011.03   558.3 2011.16   572.5 2012.14   578.2 2014.23
   593.8 2025.87   613.5 2038.79   617.5  2040.2   629.3 2041.77   633.2 2043.15
   648.9 2054.18   657.8 2059.68   672.5 2063.58   712.2  2078.6     728 2083.24
#Mann= 7 ,-1 , 0
       0    .035       0     330     .06       0     340     .04       0
   354.2    .045       0   377.1     .04       0     444     .06       0
     514      .1       0
#XS Ineff= 2 , 0
                          430.77         2067.27
Permanent Ineff=
       F       F
Bank Sta=354.2,377.1
XS Rating Curve= 0 ,0
Exp/Cntr=0.3,0.1

Type RM Length L Ch R = 1 ,6783    ,257.8,263.5,269.8
XS GIS Cut Line= 3
      2185771.44      229053.868     2186017.753      228601.335
       2186130.6      228415.571
#Sta/Elev= 30
       0 2018.11    68.9  2017.1   144.5 2017.57   185.6 2016.16   280.1 2011.29
   313.2 2011.61   332.6  2010.2   349.9 2010.17   358.32009.149   368.6 2007.64
   376.1 2007.97   381.52009.653     391 2012.17   409.7 2013.19   428.4 2012.15
     439 2008.52   443.3 2007.96   460.8 2008.44   482.6 2012.41   525.9 2023.15
   557.8 2028.27   564.1 2030.05   585.6 2031.51   598.7 2036.27   609.5 2037.96
   633.3 2043.96   644.8 2047.85   666.8 2053.81   693.1 2063.63   732.6 2080.49
#Mann= 4 ,-1 , 0
       0    .035       0   358.3    .045       0   381.5     .04       0
     470      .1       0
#XS Ineff= 2 , 0
                          412.61         2072.09
Permanent Ineff=
       F       F
Bank Sta=358.3,381.5
XS Rating Curve= 0 ,0
Exp/Cntr=0.3,0.1

Type RM Length L Ch R = 1 ,6520    ,252.5,255.9,258.3
XS GIS Cut Line= 2
     2185827.515      229099.223     2186467.406       228679.46
#Sta/Elev= 30
       0 2018.65   136.2  2013.7   200.4 2014.93   235.1 2014.23   266.2 2012.32
   287.2 2005.71   302.1 2007.85   315.7 2006.37   329.9 2007.72   367.7 2008.25
   377.22007.084   387.3 2005.56   392.22007.333   398.6 2008.56   443.6 2009.61
   450.7  2010.5   463.6 2014.73   472.1 2016.39   511.5 2017.19   524.2 2020.36
   540.4 2020.59   545.5 2021.92   556.1 2027.72   563.9 2029.75   601.2    2034
   611.8 2036.54   668.7 2039.39     690 2042.74   740.5 2047.31   765.3 2047.84
#Mann= 6 ,-1 , 0
       0    .035       0   377.2    .045       0   392.2    .035       0
     460     .04       0     650     .06       0     690    .035       0
Bank Sta=377.2,392.2
XS Rating Curve= 0 ,0
Exp/Cntr=0.3,0.1

Type RM Length L Ch R = 1 ,6264    ,327,326.6,316.4
XS GIS Cut Line= 3
     2185929.901      229266.246     2186269.286      229108.332
     2186603.946      228969.855
#Sta/Elev= 30
       0 2020.97    18.8 2020.93    45.3 2019.45     111 2013.19   146.6 2012.29
   197.4 2011.84   222.1 2010.11   241.8 2007.49   255.2 2006.27   298.4 2006.87
   323.9 2006.31   338.1 2006.95     3452006.413   357.9 2005.36   363.7 2003.96
   367.3 2003.75   370.3 2004.56   374.32006.481   385.2 2008.08   434.9 2008.71
   508.3  2011.9   608.9 2014.56   628.9  2016.5   640.9 2019.74   651.5 2024.19
   659.9 2025.92   677.1 2026.73   704.2 2026.82     719 2028.94   736.5 2029.42
#Mann= 6 ,-1 , 0
       0     .04       0      80    .035       0     345    .045       0
   374.3    .035       0  624.32     .06       0  734.32     .08       0
Bank Sta=345,374.3
XS Rating Curve= 0 ,0
Exp/Cntr=0.3,0.1

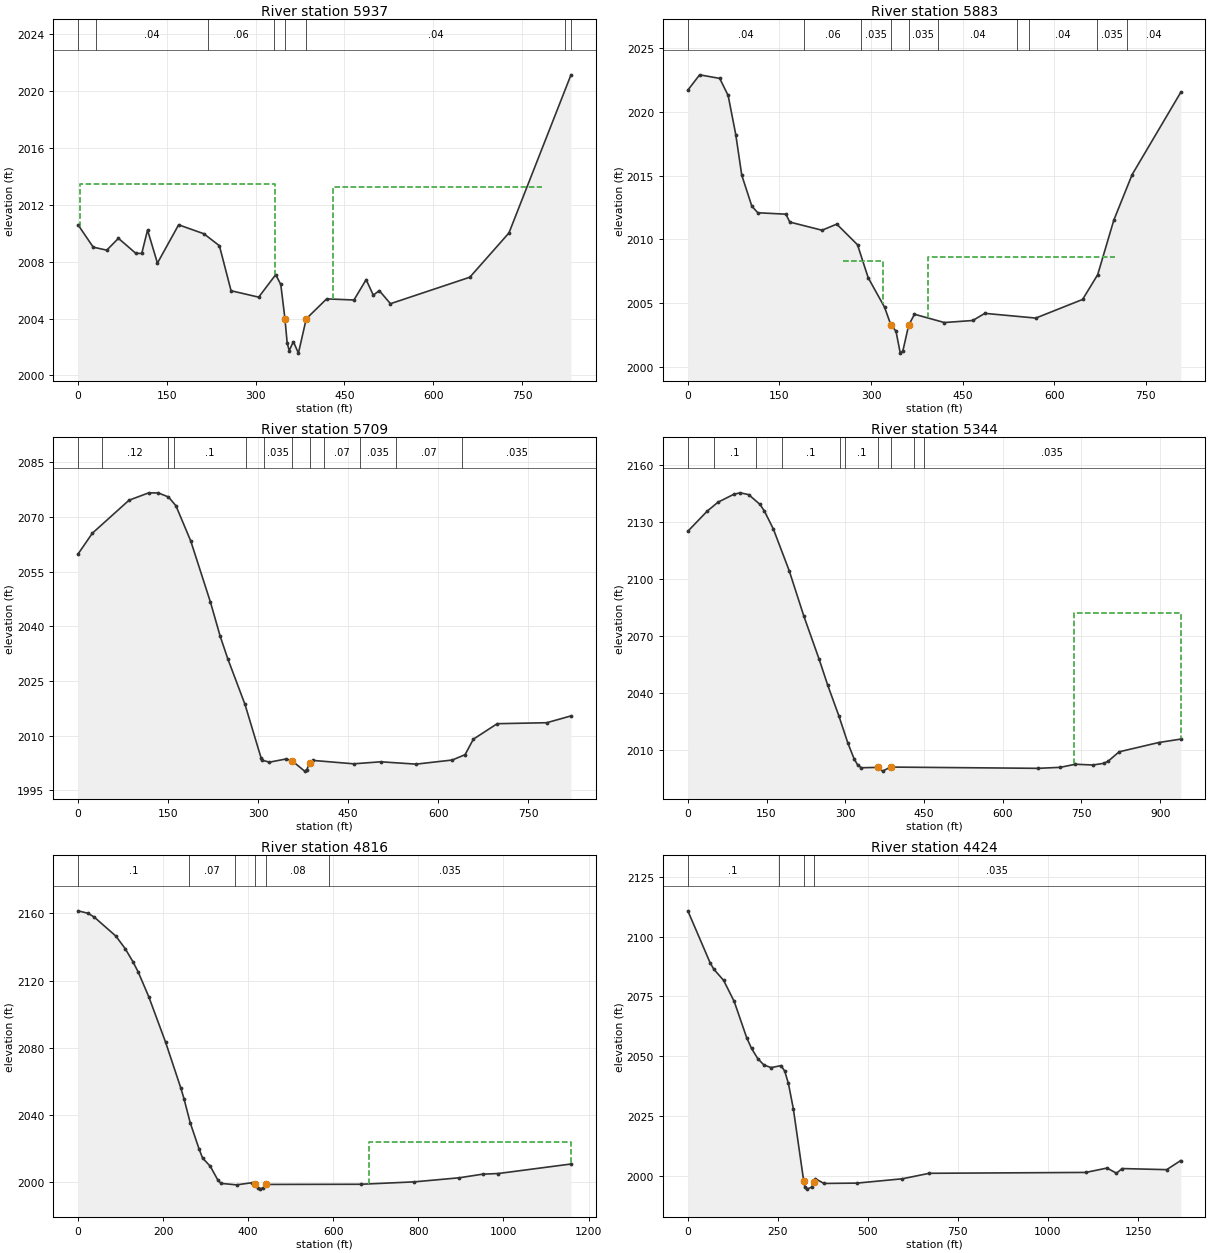
Type RM Length L Ch R = 1 ,5937    ,53.4,54.2,55.3
XS GIS Cut Line= 5
     2185984.767      229479.807      2186249.09      229475.901
     2186290.757       229456.37     2186614.975      229186.839
     2186699.611      229132.151
#Sta/Elev= 30
       0 2010.58    25.6 2009.01    48.5  2008.8    68.2 2009.63    97.5 2008.58
   107.6 2008.57   117.4 2010.21   134.1 2007.89   169.9 2010.58   212.6 2009.95
   238.8 2009.11   258.5 2005.95   305.2  2005.5   333.9 2007.08   342.5 2006.39
   349.62003.965   353.3 2002.28   356.7 2001.75   363.8 2002.37   372.3 2001.57
   385.52003.979     420 2005.38   466.1  2005.3   486.7 2006.73   498.8 2005.64
   508.9 2005.96   527.8 2005.04   661.9  2006.9     728 2010.01   832.8 2021.11
#Mann= 8 ,-1 , 0
       0     .06       0      30     .04       0     220     .06       0
  330.37    .035       0   349.6    .045       0   385.5     .04       0
  821.99     .06       0  831.99     .08       0
#XS Ineff= 2 ,-1
    2.75  332.65 2013.47  430.93  783.51 2013.23
Permanent Ineff=
       F       F
Bank Sta=349.6,385.5
XS Rating Curve= 0 ,0
Exp/Cntr=0.3,0.1

Type RM Length L Ch R = 1 ,5883    ,172.4,174.6,174.6
XS GIS Cut Line= 5
     2186023.829      229530.589     2186267.319      229516.266
     2186328.517      229492.828     2186652.736      229223.297
     2186716.538       229181.63
#Sta/Elev= 30
       0  2021.7    19.3  2022.9    52.2 2022.62      66 2021.28    78.5 2018.21
    88.3 2015.03   104.8  2012.6   114.6 2012.08   160.6 2011.97     167 2011.35
   219.8 2010.71   243.9 2011.19   277.9 2009.57   295.4 2006.98   322.2 2004.67
   332.32003.313   340.9 2002.79   347.9 2001.07   352.2 2001.25   361.72003.264
   371.2 2004.12   420.1 2003.47   466.7 2003.63   486.4 2004.19   569.8 2003.82
   646.5 2005.28   671.2 2007.22   697.7 2011.51   727.6 2015.07   807.3 2021.53
#Mann= 10 ,-1 , 0
       0     .04       0     190     .06       0  283.91    .035       0
   332.3    .045       0   361.7    .035       0  409.44     .04       0
  539.44    .035       0  559.44     .04       0  669.44    .035       0
  719.44     .04       0
#XS Ineff= 2 ,-1
   254.3  319.59 2008.28  393.81  698.97 2008.64
Permanent Ineff=
       F       F
Bank Sta=332.3,361.7
XS Rating Curve= 0 ,0
Exp/Cntr=0.3,0.1

Type RM Length L Ch R = 1 ,5709    ,362,364.8,361.9
XS GIS Cut Line= 2
     2186178.777      229814.443     2186834.159      229319.217
#Sta/Elev= 30
       0 2059.84    23.8 2065.54    84.9  2074.6   117.8 2076.63   133.9 2076.59
   150.7 2075.49   163.1 2073.08   187.8 2063.39   220.6 2046.62   236.9 2037.22
   249.4 2031.12   278.2 2018.53   304.9 2003.89     307 2003.22   318.9 2002.69
     347 2003.58   356.72003.064   377.5 2000.23     381 2000.61   386.22002.517
   391.5 2003.17   459.1 2002.24   504.4 2002.79   563.3 2002.15   623.6 2003.28
   644.9 2004.75   658.7    2009   698.4 2013.25     781 2013.52   821.4 2015.39
#Mann= 12 ,-1 , 0
       0    .035       0      40     .12       0     150    .035       0
     160      .1       0     280     .07       0     310    .035       0
   356.7    .045       0   386.2    .035       0     410     .07       0
     470    .035       0     530     .07       0     640    .035       0
Bank Sta=356.7,386.2
XS Rating Curve= 0 ,0
Exp/Cntr=0.3,0.1

Type RM Length L Ch R = 1 ,5344    ,512.9,527.8,511.3
XS GIS Cut Line= 2
     2186364.943      230103.728     2187103.257       229523.21
#Sta/Elev= 30
       0 2125.09    37.2 2135.73    57.5 2140.35    87.8 2144.53    99.8 2145.27
   115.9 2144.33   137.4 2139.21   145.7 2135.77   162.9  2126.3     193 2104.47
   221.2 2080.38     250    2058   266.7 2044.11   287.6 2028.24   305.1 2013.67
   316.8 2005.57   323.8  2002.2   330.8 2000.87   363.22001.069   371.1 1999.09
   386.22001.225   667.4 2000.56   709.6 2001.08   738.3 2002.71   771.7 2002.31
   792.6  2003.2   800.9 2004.32   821.8 2009.24   896.9  2014.1   939.2 2015.92
#Mann= 10 ,-1 , 0
       0     .12       0      50      .1       0     130     .12       0
     180      .1       0     290     .07       0     300      .1       0
   363.2    .045       0   386.2      .1       0     430     .07       0
     450    .035       0
#XS Ineff= 2 , 0
                          736.44         2082.17
Permanent Ineff=
       F       F
Bank Sta=363.2,386.2
XS Rating Curve= 0 ,0
Exp/Cntr=0.3,0.1

Type RM Length L Ch R = 1 ,4816    ,383.9,391.9,390.4
XS GIS Cut Line= 2
     2186468.112      230301.729     2187513.557      229802.073
#Sta/Elev= 30
       0 2161.53    23.5 2160.04      38 2157.82      89 2146.46   110.8 2139.01
     129 2131.23   141.5 2125.05   166.1 2110.46   205.7 2083.37   241.7 2055.92
     249 2049.71   263.5 2035.49   284.2 2019.96   292.6 2014.42   310.8 2009.48
     329 2001.09   336.2 1999.29   372.6 1998.43     409  1999.7   415.71999.053
   421.9 1996.54   427.1 1995.88   434.4 1996.58   441.9 1998.68   665.5 1998.78
   790.8 2000.21   896.2 2002.64   950.9 2004.78   987.8 2005.17  1158.7 2010.83
#Mann= 6 ,-1 , 0
       0      .1       0     260     .07       0     370     .08       0
   415.7    .045       0   441.9     .08       0     590    .035       0
#XS Ineff= 2 , 0
                          683.49         2023.97
Permanent Ineff=
       F       F
Bank Sta=415.7,441.9
XS Rating Curve= 0 ,0
Exp/Cntr=0.3,0.1

Type RM Length L Ch R = 1 ,4424    ,286.1,279.6,270.9
XS GIS Cut Line= 3
     2186557.828      230567.698     2187406.787      230335.927
     2187786.995      230028.635
#Sta/Elev= 30
       0 2110.81    61.6 2089.18    71.8 2086.47    99.4 2081.73   128.8 2072.91
   163.5 2057.74   176.9 2053.29   194.3 2049.02   211.6 2046.32   231.7 2045.28
   258.9 2046.11   269.1 2043.79   279.3 2038.63   292.9 2028.14  321.911997.712
   325.1 1995.18   330.3 1994.47   343.9  1995.3     3501997.429   354.1 1998.84
   377.9 1996.85   469.7 1996.99   595.6 1998.79   670.4 2001.09  1105.1 2001.45
  1164.2 2003.28  1190.4 2001.11    1206 2003.07  1329.8 2002.61  1368.9 2006.43
#Mann= 4 ,-1 , 0
       0      .1       0   251.9     .08       0  321.91    .045       0
     350    .035       0
Bank Sta=321.91,350
XS Rating Curve= 0 ,0
Exp/Cntr=0.3,0.1