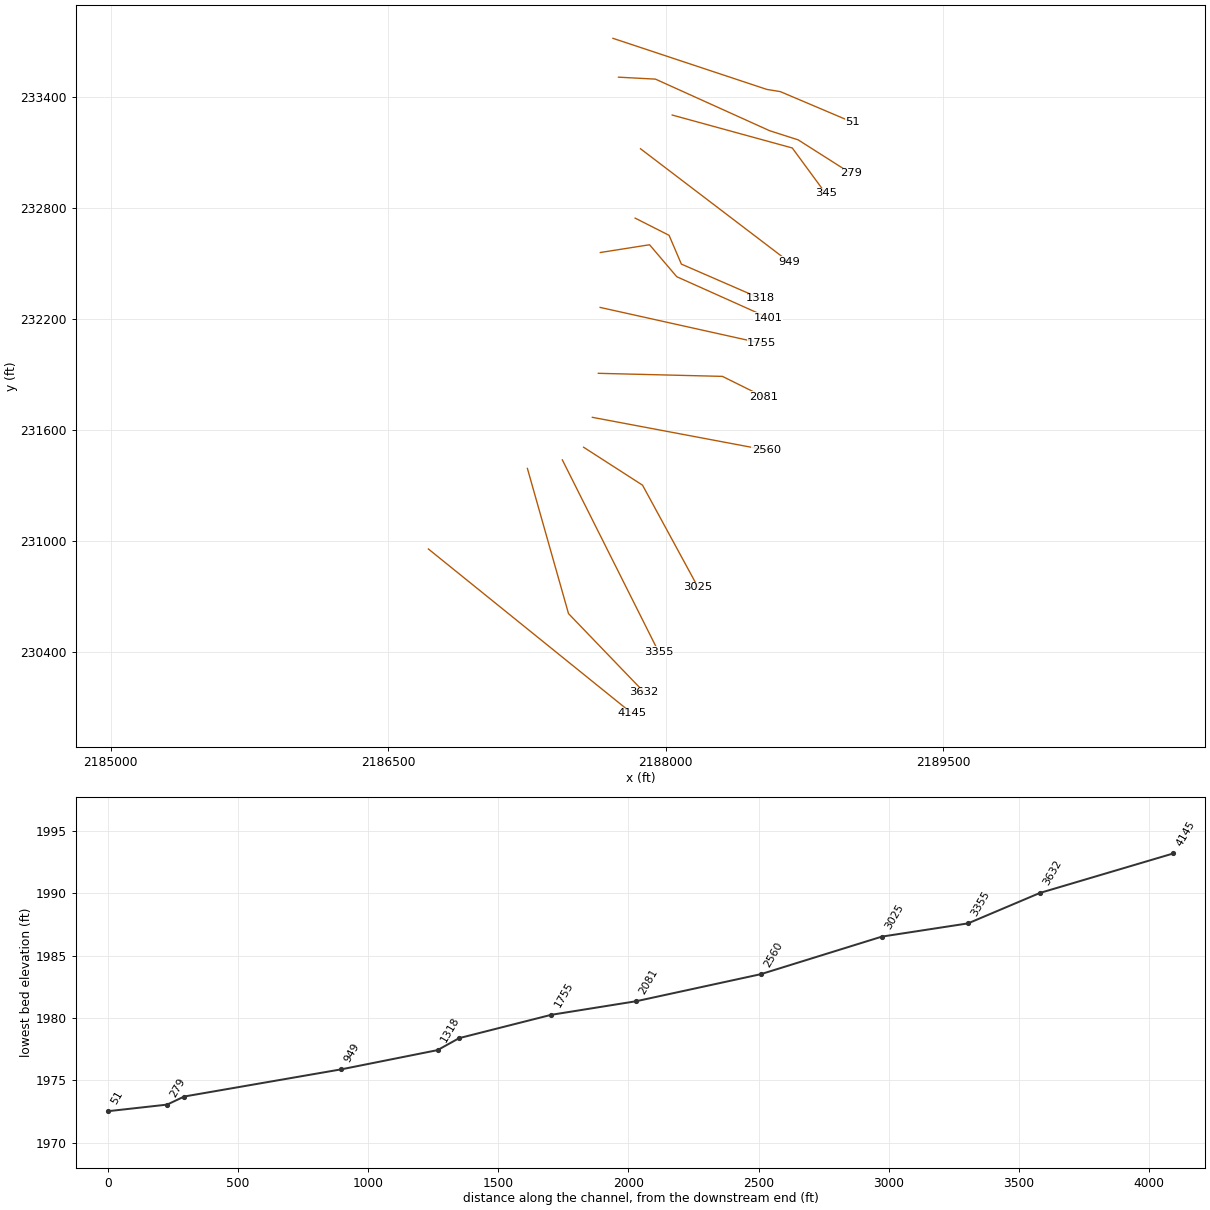
HEC-RAS study SWTSPRNGSCK.prj: SWTSPRNGSCK

--- SWTSPRNGSCK.g01 (geometry) --- (continued)

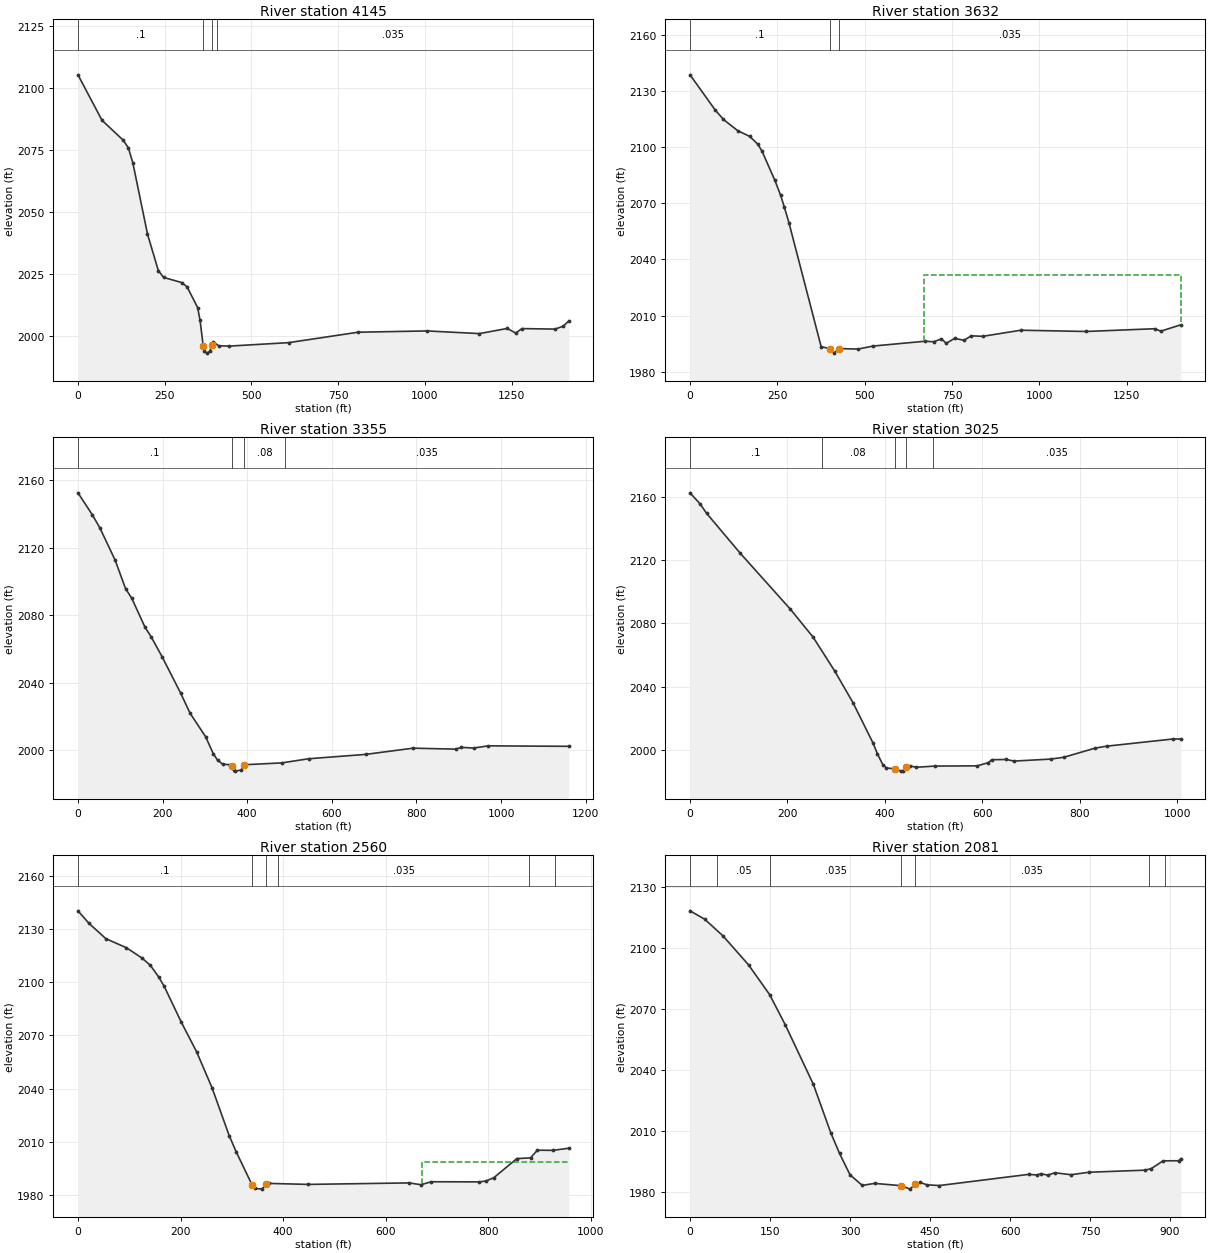
Type RM Length L Ch R = 1 ,4145    ,518.7,512.9,497.8
XS GIS Cut Line= 2
     2186717.352      230958.926     2187818.245      230070.302
#Sta/Elev= 30
       0 2105.26    69.5 2086.91   130.3 2078.96   145.4 2075.83   158.3 2069.76
   200.3 2041.23   231.6 2026.44   246.9 2023.68   299.5 2021.59   314.6 2019.85
   344.9 2011.54   351.8 2006.53  361.111996.063   364.7 1993.94   372.7 1993.19
   379.9 1993.87   386.4 1996.61     390 1997.68   405.6 1996.15   436.4 1996.02
   607.7 1997.42   807.4 2001.61  1005.6 2002.13  1157.3 2001.06  1237.5 2003.13
  1261.8 2001.27  1279.6 2003.07  1375.6 2002.87  1399.5 2004.09  1414.8 2006.18
#Mann= 4 ,-1 , 0
       0      .1       0  361.11    .045       0   386.4      .1       0
     400    .035       0
Bank Sta=361.11,386.4
XS Rating Curve= 0 ,0
Exp/Cntr=0.3,0.1

Type RM Length L Ch R = 1 ,3632    ,271.1,276.1,277.8
XS GIS Cut Line= 3
     2187252.562      231394.376     2187474.784      230609.654
     2187883.349      230184.885
#Sta/Elev= 30
       0 2138.52    71.9 2119.78    95.7  2114.7   136.6  2108.7   170.7 2105.68
   193.7 2101.56   205.8 2097.89     243 2082.14   259.4 2074.19   269.8 2068.01
   283.3 2059.46   375.3 1993.47   399.61992.451   412.8 1990.02   425.81992.441
     481 1992.19   524.7 1993.81     672 1996.36   697.4 1996.09   719.7 1997.62
   733.4 1995.28   757.2 1997.86   784.5  1996.9     805 1999.25   837.8 1998.99
   947.1 2002.25  1133.7 2001.57  1329.7 2003.04  1347.7 2001.75  1404.9 2005.15
#Mann= 3 ,-1 , 0
       0      .1       0   399.6    .045       0   425.8    .035       0
#XS Ineff= 2 , 0
                          669.86         2031.63
Permanent Ineff=
       F       F
Bank Sta=399.6,425.8
XS Rating Curve= 0 ,0
Exp/Cntr=0.3,0.1

Type RM Length L Ch R = 1 ,3355    ,329.9,330.8,330.4
XS GIS Cut Line= 2
     2187441.395      231440.695     2187961.474      230403.635
#Sta/Elev= 30
       0 2152.68    33.7 2139.76    52.1 2131.73      88 2112.68   112.4 2095.91
   127.1 2090.15   158.5 2072.95   173.2 2067.18   198.9 2055.43   242.9 2033.77
     265 2021.94   301.7 2008.01     320 1997.88     330 1994.07   342.2  1991.7
   360.4 1991.37   363.61990.565   367.7 1988.38   371.5 1987.58   386.1 1988.27
   393.3 1991.37   481.6 1992.46   545.1 1994.92   679.7  1997.5     792  2001.2
   892.6 2000.62   906.1 2001.68   935.4 2001.27   969.7 2002.58  1160.2  2002.3
#Mann= 4 ,-1 , 0
       0      .1       0   363.6    .045       0   393.3     .08       0
     490    .035       0
Bank Sta=363.6,393.3
XS Rating Curve= 0 ,0
Exp/Cntr=0.3,0.1

Type RM Length L Ch R = 1 ,3025    ,445.4,464.6,465
XS GIS Cut Line= 3
       2187556.5      231508.978     2187874.958      231304.026
     2188175.305      230751.509
#Sta/Elev= 30
       0 2162.64    20.7 2155.61      34 2149.69   103.1  2124.4   205.9 2089.04
   252.5 2071.38   297.1 2049.83   334.5 2029.86   375.9 2004.16   384.4 1997.64
   395.6  1990.7   403.1 1988.54   420.21987.927     433 1986.52   436.7 1986.73
   444.2 1989.25   451.7 1989.89   463.8 1988.95   502.5 1989.71   589.8 1989.86
   612.2 1991.91   619.7 1993.75   649.6 1993.88   664.9 1992.88   740.4 1994.14
   767.9 1995.33   831.6 2001.09   855.7 2002.33   991.2 2006.85  1007.6 2006.86
#Mann= 5 ,-1 , 0
       0      .1       0     270     .08       0   420.2    .045       0
   444.2     .08       0  498.71    .035       0
Bank Sta=420.2,444.2
XS Rating Curve= 0 ,0
Exp/Cntr=0.3,0.1

Type RM Length L Ch R = 1 ,2560    ,448.1,478.9,462.3
XS GIS Cut Line= 2
     2187603.691       231670.78     2188544.229      231493.696
#Sta/Elev= 30
       0 2140.18    21.2 2133.22    54.5 2124.48    94.6  2119.4   125.5 2113.48
   141.3 2109.46     158 2102.69   168.1 2097.73   201.4 2077.54   231.5 2060.74
   261.5 2040.54   294.9 2013.62   308.5 2004.54  339.281986.025     345 1983.97
   358.3 1983.51   367.11986.143   371.7 1986.74   448.6 1986.17   645.8 1987.01
   668.8 1985.99   688.9 1987.66   782.3 1987.59   795.7 1988.07     811 1989.96
   855.8  2000.7   882.5 2001.12   895.8 2005.43   925.9 2005.34   957.1 2006.53
#Mann= 6 ,-1 , 0
       0      .1       0  339.28    .045       0   367.1      .1       0
     390    .035       0     880     .06       0     930    .035       0
#XS Ineff= 2 , 0
                          671.55         1998.77
Permanent Ineff=
       F       F
Bank Sta=339.28,367.1
XS Rating Curve= 0 ,0
Exp/Cntr=0.3,0.1

Type RM Length L Ch R = 1 ,2081    ,323.1,326.4,318.7
XS GIS Cut Line= 3
     2187636.217      231908.662     2188306.816      231892.134
      2188530.34      231781.457
#Sta/Elev= 30
       0 2118.36    27.6 2114.23    61.7 2106.03   109.7 2091.76   149.1 2077.16
   178.6 2062.22   231.1 2033.01   263.9 2009.05   280.3 1998.92     300 1988.35
     323 1983.18     346 1984.16   395.91983.049   412.5 1981.34   422.11983.863
   431.3 1984.65   444.4 1983.45   467.4 1983.11   634.8 1988.61   651.2 1988.29
   657.8 1988.94   670.8 1988.21     684  1989.4   714.4 1988.43   747.8 1989.65
   853.8 1990.69   864.9 1991.49   886.9 1995.26   916.2 1995.32   920.2 1996.35
#Mann= 7 ,-1 , 0
       0     .08       0      50     .05       0     150    .035       0
   395.9    .045       0   422.1    .035       0   860.8     .04       0
   890.8     .06       0
Bank Sta=395.9,422.1
XS Rating Curve= 0 ,0
Exp/Cntr=0.3,0.1

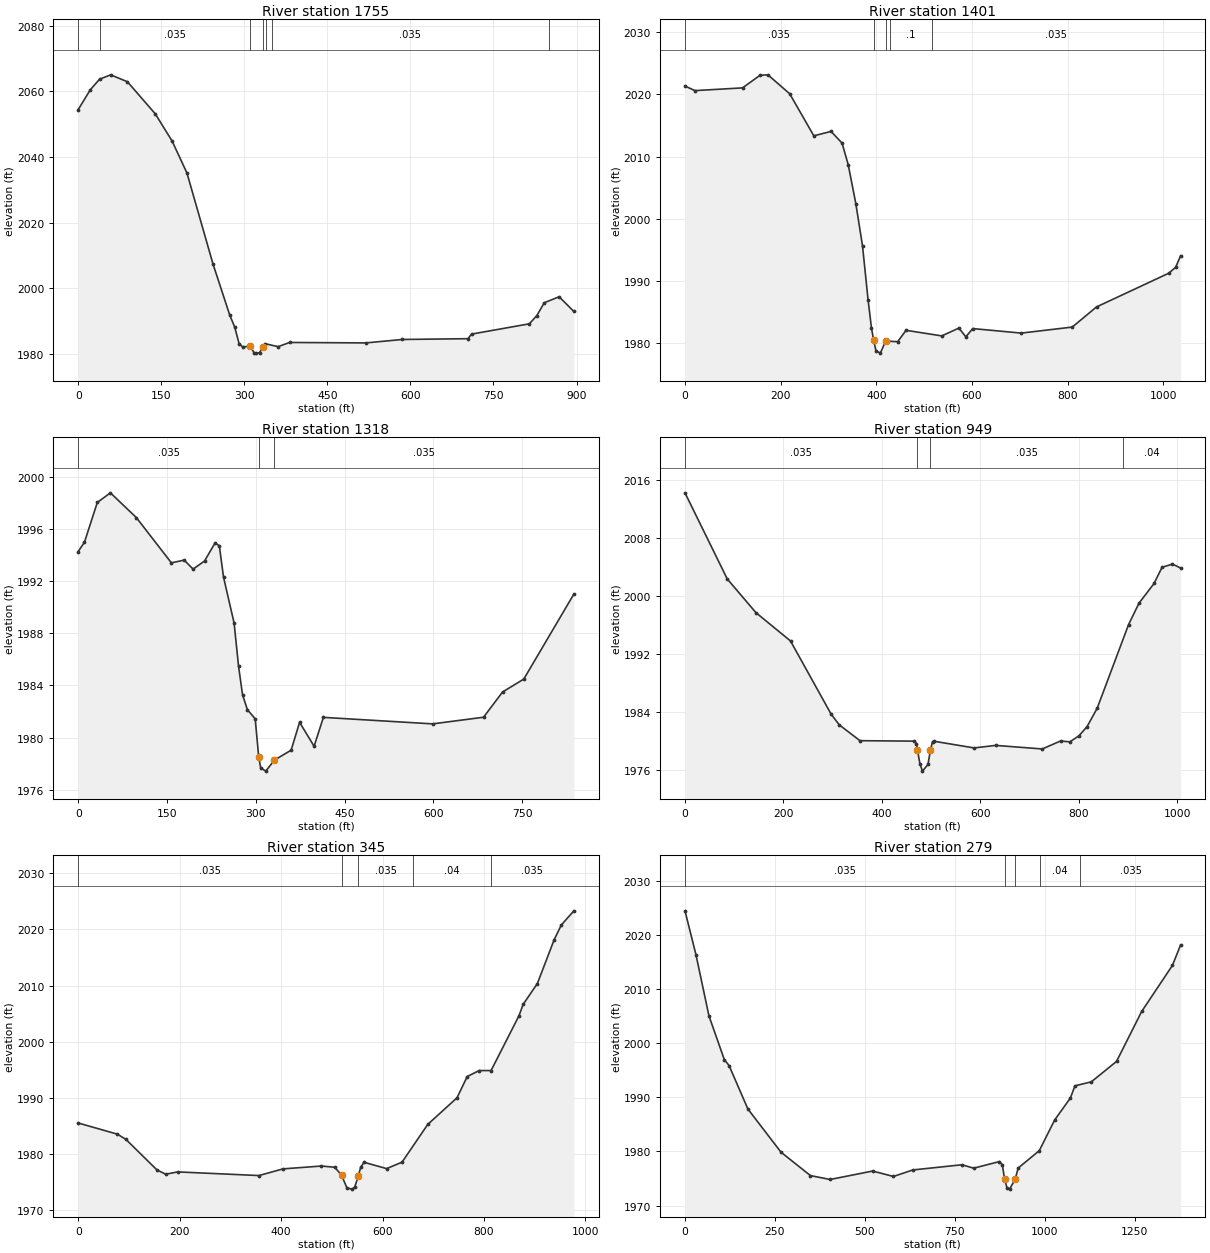
Type RM Length L Ch R = 1 ,1755    ,359.2,353.7,332
XS GIS Cut Line= 2
2187646.00131567232264.8807456082188519.84817779232070.692554025
#Sta/Elev= 30
       0 2054.45    21.7 2060.46    38.5  2063.7    58.6 2065.05    88.9 2062.94
   139.3 2053.14   169.5  2044.9   196.4 2035.14   243.5 2007.39   273.7 1991.84
   282.8 1988.14   290.5 1983.18   297.2 1982.12   310.7 1982.42   317.4 1980.41
   320.8 1980.25   327.5 1980.38   332.91981.982   337.6 1983.12   361.1 1982.22
   381.8  1983.5   519.3 1983.36   585.3 1984.41   703.9 1984.65   710.6 1986.05
   814.8 1989.18   828.3 1991.68   841.7 1995.59   868.6 1997.43   895.2 1992.95
#Mann= 7 ,-1 , 0
       0     .05       0      40    .035       0   310.7    .045       0
   332.9    .035       0     340      .1       0     350    .035       0
     850     .04       0
Bank Sta=310.7,332.9
XS Rating Curve= 0 ,0
Exp/Cntr(USF)=0,0
Exp/Cntr=0.3,0.1

Type RM Length L Ch R = 1 ,1401    ,86.8,82.9,75.5
XS GIS Cut Line= 4
2187646.73041701232561.7783592722187912.89142608232603.701450773
2188059.94189538232430.9280577882188552.70556811232210.070133313
#Sta/Elev= 30
       0 2021.34    20.7  2020.6   120.3 2021.04   156.8 2023.06   173.4 2023.14
     219 2020.09   269.4 2013.33   305.4 2014.04   328.4 2012.16   341.3 2008.69
   357.3 2002.39   371.2 1995.62   382.9  1986.9   389.9 1982.43 394.5851980.426
   399.2 1978.77   408.5 1978.38   419.51980.315   444.7 1980.22   462.3 1982.05
   536.9 1981.15   572.8 1982.41   587.2    1981   601.6 1982.33   703.1  1981.6
   809.8 1982.57   860.4 1985.81  1011.4 1991.23  1025.9 1992.19  1036.3 1994.05
#Mann= 5 ,-1 , 0
       0    .035       0 394.585    .045       0   419.5    .035       0
  429.44      .1       0  516.32    .035       0
Bank Sta=394.585,419.5
XS Rating Curve= 0 ,0
Exp/Cntr(USF)=0,0
Exp/Cntr=0.3,0.1

Type RM Length L Ch R = 1 ,1318    ,356.3,369.5,369.9
XS GIS Cut Line= 4
2187835.17551172232747.6305519562188018.42447209232654.750941905
2188084.94635497232499.1148385772188509.18024952232314.610748342
#Sta/Elev= 30
       0 1994.29    10.6 1995.01    32.3 1998.06    54.4  1998.8    98.4 1996.89
   157.4 1993.42     179 1993.63   194.1 1992.94   213.4 1993.56   231.3 1994.96
   238.4 1994.73   245.5 1992.32   263.4 1988.79   270.8 1985.51   277.6 1983.29
   285.8 1982.14     299 1981.44     305 1978.47   308.3 1977.67   316.9 1977.42
   331.41978.265   359.7 1979.03     374 1981.17   398.5 1979.33   414.2 1981.55
   598.8 1981.05   684.7 1981.56   716.9  1983.5   752.7 1984.49   837.3 1991.02
#Mann= 3 ,-1 , 0
       0    .035       0     305    .045       0   331.4    .035       0
Bank Sta=305,331.4
XS Rating Curve= 0 ,0
Exp/Cntr(USF)=0,0
Exp/Cntr=0.3,0.1

Type RM Length L Ch R = 1 ,949     ,603.4,603.4,603.4
XS GIS Cut Line= 2
     2187864.107      233122.603     2188664.888      232512.793
#Sta/Elev= 30
       0 2014.28    85.8  2002.4   144.2 1997.74   214.3 1993.84   296.8 1983.74
   313.2 1982.27   355.4 1980.08   465.8 1980.02     470 1979.68   472.11978.807
   477.1 1976.88   482.3 1975.88   493.5 1976.81   498.41978.777   502.7 1979.94
   505.2 1980.01   587.1 1979.08   630.8 1979.43   725.6 1978.94   762.7 1980.04
   781.4 1979.92   799.9 1980.74   816.6 1982.03     837 1984.55   900.8  1996.1
   921.9 1999.05   952.5 2001.77   968.7    2004   989.8 2004.45  1006.5  2003.9
#Mann= 4 ,-1 , 0
       0    .035       0   472.1    .045       0   498.4    .035       0
     890     .04       0
Bank Sta=472.1,498.4
XS Rating Curve= 0 ,0
Exp/Cntr=0.3,0.1

Type RM Length L Ch R = 1 ,345     ,64,66,59.1
XS GIS Cut Line= 3
     2188035.548      233304.894      2188684.42      233126.943
     2188864.541      232881.717
#Sta/Elev= 30
       0 1985.49    77.3  1983.5    94.3 1982.55   155.5  1977.1   172.5 1976.36
   196.3 1976.77   356.2 1976.12   403.8 1977.31   479.6 1977.82   505.9  1977.6
   519.31976.154   529.7 1973.92   539.6  1973.7   544.9 1974.01     5521975.986
   556.9 1977.61   563.6 1978.48     608 1977.36   638.4 1978.51   689.1 1985.24
   746.8 1989.99   766.9 1993.78   790.4 1994.84   813.9 1994.84   868.9 2004.61
   877.2 2006.65   905.2 2010.36   938.2 2018.15   952.3 2020.78   977.1 2023.32
#Mann= 5 ,-1 , 0
       0    .035       0   519.3    .045       0     552    .035       0
     660     .04       0  812.83    .035       0
Bank Sta=519.3,552
XS Rating Curve= 0 ,0
Exp/Cntr=0.3,0.1

Type RM Length L Ch R = 1 ,279     ,222.6,228.2,228.2
XS GIS Cut Line= 5
2187744.97426469233509.6619629442187944.80056964233499.131360703
2188561.72968779233220.3898437622188716.29320892233170.798031968
2189001.93917705232989.162088708
#Sta/Elev= 30
       0 2024.45    30.5 2016.36    66.6 2005.06   109.3 1996.98   122.5 1995.88
     175 1987.84     267 1979.87   348.8 1975.55   403.4 1974.83   521.8 1976.39
   579.4 1975.39   633.4 1976.59   769.9 1977.55   802.6 1976.92   874.2 1978.14
   882.2 1977.56   888.5 1974.91   895.3 1973.27   902.3 1973.05  917.64 1974.83
   926.4 1976.95     985 1980.16  1027.7 1985.82  1071.4 1989.87    1084 1992.12
  1129.7 1992.87  1199.7 1996.64  1269.6 2005.86  1355.2 2014.38  1377.9 2018.17
#Mann= 5 ,-1 , 0
       0    .035       0   888.5    .045       0  917.64    .035       0
  987.08     .04       0 1099.41    .035       0
Bank Sta=888.5,917.64
XS Rating Curve= 0 ,0
Exp/Cntr(USF)=0,0
Exp/Cntr=0.3,0.1

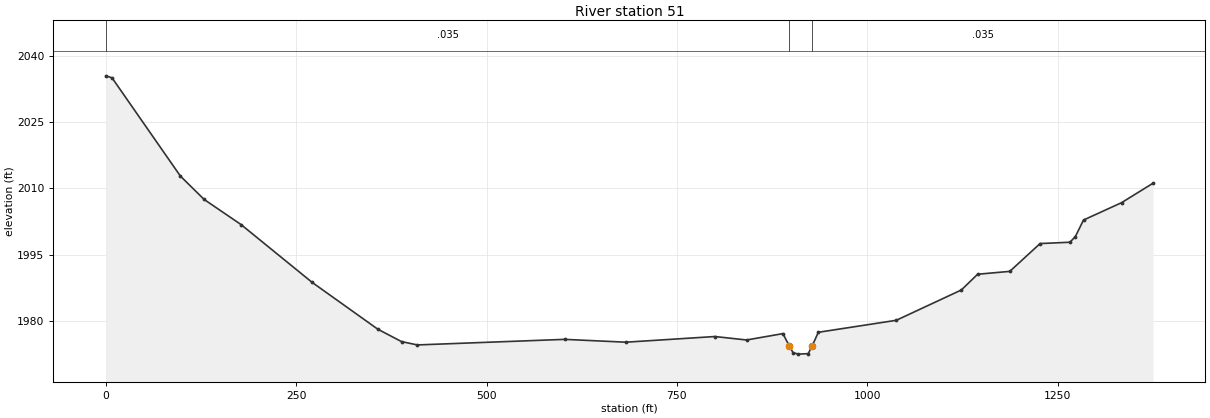
Type RM Length L Ch R = 1 ,51      ,,,
XS GIS Cut Line= 4
 2187715.1639184233719.6404856512188546.89738988233443.525300619
2188619.73759206233431.6675932862189011.04193404233265.659690629
#Sta/Elev= 30
       0 2035.47     8.2 2035.02      98 2012.79   129.2  2007.5   177.6 2001.83
   270.9 1988.76   357.3 1978.15   388.4 1975.35   409.2  1974.6   602.6 1975.86
     683 1975.22   799.8  1976.5   841.5 1975.72   889.2 1977.16  897.34 1974.43
   902.5 1972.86   909.3 1972.52   922.4 1972.63  927.73 1974.43   935.7 1977.46
    1038 1980.17  1123.5 1987.03  1144.9 1990.59  1187.1 1991.24  1226.9 1997.53
  1266.1 1997.83  1273.2 1999.11  1283.9 2002.85  1333.8 2006.771375.229 2011.18
#Mann= 3 , 0 , 0
       0    .035       0  897.34    .045       0  927.73    .035       0
Bank Sta=897.34,927.73
XS Rating Curve= 0 ,0
Exp/Cntr(USF)=0,0
Exp/Cntr=0.3,0.1
LCMann Table=0

Chan Stop Cuts=-1
Use User Specified Reach Order=0
Composite Channel Slope=5